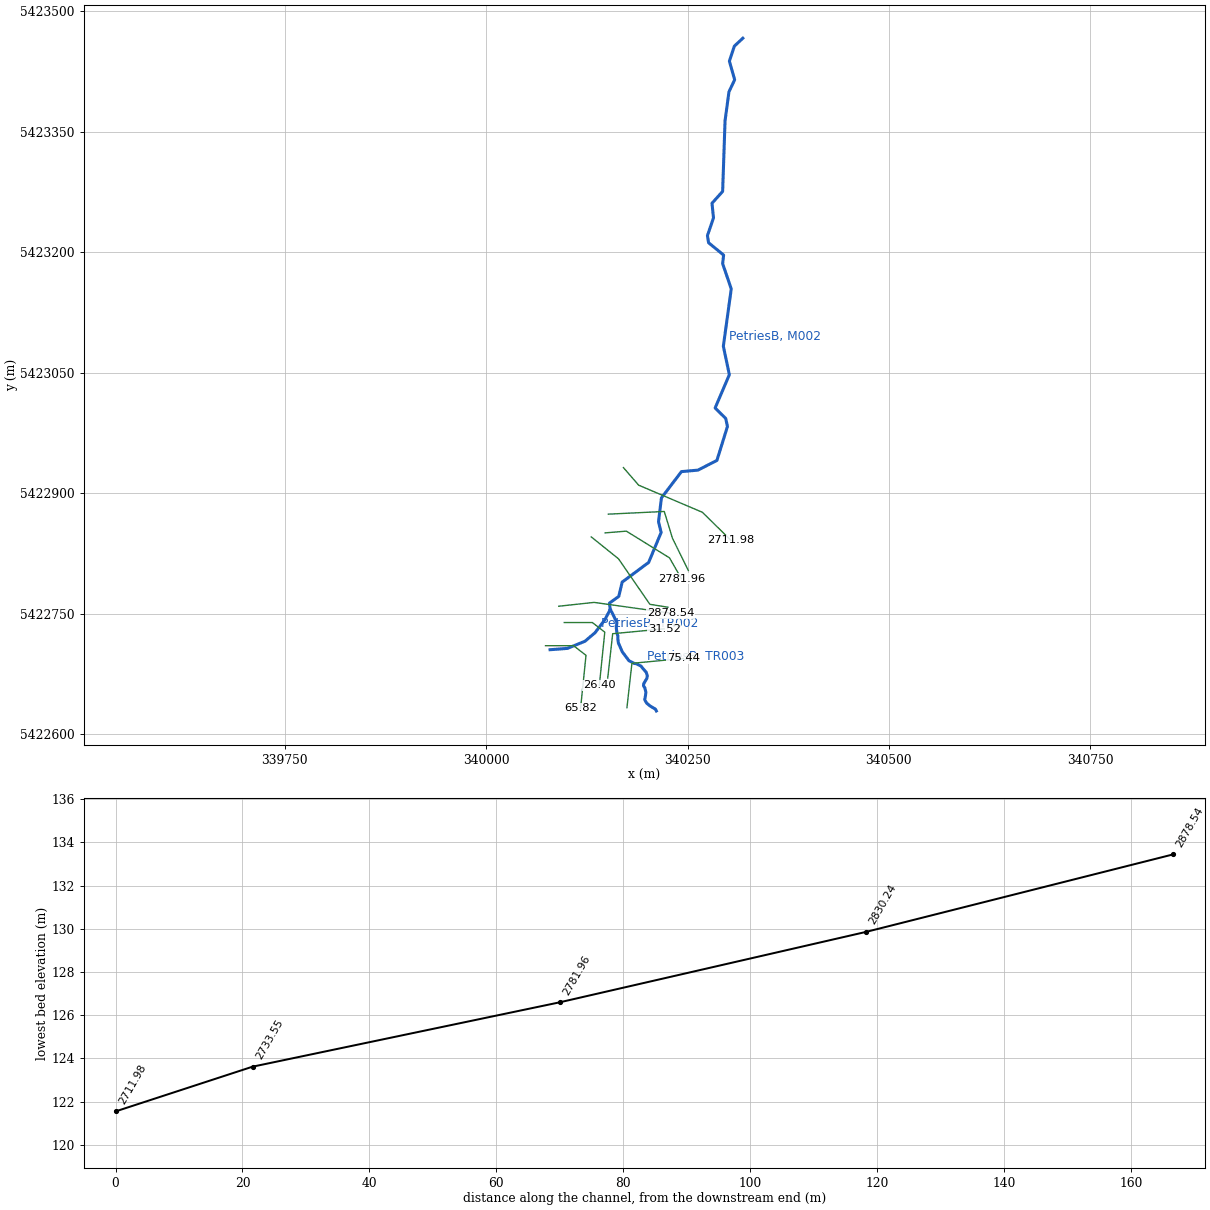
--- PetriesBrk_v001.prj (project) ---

Proj Title=Petries_Brook
Current Plan=p24
Default Exp/Contr=0.3,0.1
SI Units
Geom File=g02
Geom File=g01
Flow File=f02
Flow File=f03
Plan File=p23
Plan File=p24
Y Axis Title=Elevation
X Axis Title(PF)=Main Channel Distance
X Axis Title(XS)=Station
BEGIN DESCRIPTION:
END DESCRIPTION:
DSS Export Rating Curves= 0
DSS Export Rating Curve Sorted= 0
DSS Export Volume Flow Curves= 0
DXF Filename=PetriesBrook.
DXF OffsetX= 0
DXF OffsetY= 0
DXF ScaleX= 1
DXF ScaleY= 10

--- PetriesBrk_v001.p24 (plan) ---

Plan Title=Plan 24
Program Version=4.10
Short Identifier=Plan 24
Geom File=g01
Flow File=f03
Mixed Flow
K Sum by GR= 0
Std Step Tol= 0.01
Critical Tol= 0.01
Num of Std Step Trials= 20
Max Error Tol= 0.3
Flow Tol Ratio= 0.001
Split Flow NTrial= 30
Split Flow Tol= 0.02
Split Flow Ratio= 0.02
Log Output Level= 0
Friction Slope Method= 1
Unsteady Friction Slope Method= 2
Unsteady Bridges Friction Slope Method= 1
Parabolic Critical Depth
Global Vel Dist= 0 , 0 , 0
Global Log Level= 0
CheckData=True
Encroach Param=-1 ,0,0, 0
Computation Interval=1HOUR
Output Interval=1HOUR
Run HTab= 0
Run UNet= 0
Run PostProcess= 0
Run WQNet= 0
UNET Theta= 1
UNET Theta Warmup= 1
UNET ZTol= 0.02
UNET ZSATol= 0.05
UNET MxIter= 20
UNET MaxInSteps= 0
UNET DtIC= 0
UNET DtMin= 0
UNET MaxCRTS= 20
UNET WFStab= 2
UNET SFStab= 1
UNET WFX= 1
UNET SFX= 1
UNET DSS MLevel= 4
UNET DZMax Abort= 100
UNET Convert EG Bridges= 0
UNET Use Existing IB Tables=-1
UNET Froude Reduction=False
UNET Froude Limit= 1
UNET Froude Power= 10
UNET Time Slicing=0,0, 5
UNET Junction Losses=0
Instantaneous Interval=1HOUR
Write IC File= 0
Write IC File at Sim End=0
Echo Input=False
Echo Parameters=False
Echo Output=False
Write Detailed= 0
WQ AD Non Conservative
WQ ULTIMATE=-1
WQ Max Comp Step=1HOUR
WQ Output Interval=15MIN
WQ Output Selected Increments= 0
WQ Output face flow=0
WQ Output face velocity=0
WQ Output face area=0
WQ Output face dispersion=0
WQ Output cell volume=0
WQ Output cell surface area=0
WQ Output cell continuity=0
WQ Output cumulative cell continuity=0
WQ Output face conc=0
WQ Output face dconc_dx=0
WQ Output face courant=0
WQ Output face peclet=0
WQ Output face adv mass=0
WQ Output face disp mass=0
WQ Output cell mass=0
WQ Output cell source sink temp=0
WQ Output cell source sink nsm=0
WQ Output MaxMinRange=-1
WQ Daily Max Min Mean=-1
WQ Daily Range=0
WQ Daily Time=0
WQ Create Restart=0
WQ Fixed Restart=0
WQ System Summary=0
WQ Use Fixed Temperature=0
Sorting and Armoring Iterations= 10
XS Update Threshold= 0.02
Hydraulics Update Threshold= 0.02
Energy Slope Method= 1
Volume Change Method= 0
XS Weighting Method= 0
Number of US Weighted Cross Sections= 1
Number of DS Weighted Cross Sections= 1
Upstream XS Weight=0.25
Main XS Weight=0.5
Downstream XS Weight=0.25
Number of DS XS's Weighted with US Boundary= 1
Upstream Boundary Weight= 1
Weight of XSs Associated with US Boundary= 0
Number of US XS's Weighted with DS Boundary= 1
Downstream Boundary Weight= 0.5
Weight of XSs Associated with DS Boundary= 0.5
Sediment Output Level= 4
Mass or Volume Output= 0
Output Increment Type= 1
Profile and TS Output Increment= 10
XS Output Flag= 0
XS Output Increment= 10
Disregard all LS=0
Disregard all Conn=0
Disregard all Breaches=0
Disregard all Pumps=0

--- PetriesBrk_v001.p23 (plan) ---

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Plan Title=Plan 23
Short Identifier=Plan 23
Geom File=g01
Flow File=f02

--- PetriesBrk_v001.f03 (steady flow) ---

Flow Title=Petries-Flow-100yr
Program Version=4.10
Number of Profiles= 21
Profile Names=100Year-Existing,AMEC-100yr-2020-90%,AMEC-100yr-2020-Max,AMEC-100yr-2050-90%,AMEC-100yr-2050-Max,AMEC-100yr-2080-90%,AMEC-100yr-2080-Max,FINIIS-100yr-2050-90%,FINIIS-100yr-2050-Max,CGCM2-100yr-2020-90%,CGCM2-100yr-2020-Max,CGCM2-100yr-2050-90%,CGCM2-100yr-2050-Max,CGCM2-100yr-2080-90%,CGCM2-100yr-2080-Max,HADCM3-100yr-2020-90%,HADCM3-100yr-2020-Max,HADCM3-100yr-2050-90%,HADCM3-100yr-2050-Max,HADCM3-100yr-2080-90%,HADCM3-100yr-2080-Max
River Rch & RM=PetriesB,TR002           ,65.82
       4     4.8       5     4.9     5.1     5.2     5.4    11.3    11.1     7.6
     7.5     7.8     7.7     9.3     9.5     6.2     6.1    10.9    10.7     7.1
     7.3
River Rch & RM=PetriesB,TR003           ,75.44
     2.8       3     3.2     3.1     3.2     3.2     3.4     7.3     7.1     4.9
     4.8       5     4.9     5.9     6.1       4     3.9       7     6.9     4.5
     4.6
River Rch & RM=PetriesB,M002            ,2878.54
       9     9.8    10.2      10    10.4    10.5      11    23.5    23.1    15.7
    15.4    16.1    15.8    19.3    19.7    12.8    12.6    22.7    22.2    14.6
    14.9
River Rch & RM=PetriesB,M002            ,2636.80
     9.6    10.4    10.8    10.6    10.9    11.1    11.7    24.3    23.9    16.4
    16.2    16.9    16.6    20.1    20.5    13.4    13.2    23.5    23.1    15.2
    15.7
River Rch & RM=PetriesB,TR001           ,194.22
       7     7.5     7.8     7.7     7.9       8     8.4      17    16.7    11.7
    11.5      12    11.7    14.1    14.5     9.6     9.5    16.4    16.1    10.9
    11.2
River Rch & RM=PetriesB,M001            ,2036.68
    16.3    17.7    18.3      18    18.6    18.9    19.8    41.2    40.5    27.9
    27.4    28.6    28.1    34.1    34.8    22.8    22.5    39.7      39    25.9
    26.7
River Rch & RM=PetriesB,M001            ,1790.83
    18.7    20.3      21    20.6    21.4    21.7    22.8    47.3    46.5      32
    31.5    32.9    32.3    39.1      40    26.2    25.8    45.6    44.9    29.8
    30.7
River Rch & RM=PetriesB,M001            ,1418.45
    19.3      21    21.8    21.3    22.2    22.5    23.6      50    49.2    33.5
    33.1    34.4    33.8    41.2    42.2    27.4    26.9    48.2    47.4    31.2
    32.1
River Rch & RM=PetriesB,M001            ,1131.36
    19.2      21    21.8    21.3    22.1    22.4    23.6    50.1    49.2    33.5
    33.1    34.4    33.8    41.2    42.2    27.3    26.9    48.3    47.4    31.2
    32.1
River Rch & RM=PetriesB,M001            ,1036.63
    20.4    22.1      23    22.5    23.3    23.6    24.9    52.8    51.9    35.1
    34.7    36.1    35.5    43.3    44.4    28.6    28.1    50.8      50    32.8
    33.7
River Rch & RM=PetriesB,M001            ,599.17
    20.4    22.1      23    22.5    23.3    23.7    24.9    52.4    51.5    34.8
    34.3    35.7    35.1    42.9      44    28.6    28.2    50.4    49.6    32.6
    33.5
River Rch & RM=PetriesB,M001            ,399.97
    22.1    24.1      25    24.4    25.4    25.8    27.1    57.5    56.5    38.2
    37.7    39.2    38.6    47.2    48.3    31.1    30.7    55.3    54.4    35.6
    36.6
River Rch & RM=PetriesB,M001            ,200
    22.4    24.5    25.4    24.8    25.8    26.2    27.6    57.6    56.7    38.9
    38.4    39.9    39.3    47.7    48.9    31.8    31.3    55.5    54.7    36.4
    37.4
Boundary for River Rch & Prof#=PetriesB,TR002           , 1
Up Type= 3
Up Slope=0.028
Dn Type= 0
Boundary for River Rch & Prof#=PetriesB,TR002           , 2
Up Type= 3
Up Slope=0.028
Dn Type= 0
Boundary for River Rch & Prof#=PetriesB,TR002           , 3
Up Type= 3
Up Slope=0.028
Dn Type= 0
Boundary for River Rch & Prof#=PetriesB,TR002           , 4
Up Type= 3
Up Slope=0.028
Dn Type= 0
Boundary for River Rch & Prof#=PetriesB,TR002           , 5
Up Type= 3
Up Slope=0.028
Dn Type= 0
Boundary for River Rch & Prof#=PetriesB,TR002           , 6
Up Type= 3
Up Slope=0.028
Dn Type= 0
Boundary for River Rch & Prof#=PetriesB,TR002           , 7
Up Type= 3
Up Slope=0.028
Dn Type= 0
Boundary for River Rch & Prof#=PetriesB,TR002           , 8
Up Type= 3
Up Slope=0.028
Dn Type= 0
Boundary for River Rch & Prof#=PetriesB,TR002           , 9
Up Type= 3
Up Slope=0.028
Dn Type= 0
Boundary for River Rch & Prof#=PetriesB,TR002           , 10
Up Type= 3
Up Slope=0.028
Dn Type= 0
Boundary for River Rch & Prof#=PetriesB,TR002           , 11
Up Type= 3
Up Slope=0.028
Dn Type= 0
Boundary for River Rch & Prof#=PetriesB,TR002           , 12
Up Type= 3
Up Slope=0.028
Dn Type= 0
Boundary for River Rch & Prof#=PetriesB,TR002           , 13
Up Type= 3
Up Slope=0.028
Dn Type= 0
Boundary for River Rch & Prof#=PetriesB,TR002           , 14
Up Type= 3
Up Slope=0.028
Dn Type= 0
Boundary for River Rch & Prof#=PetriesB,TR002           , 15
Up Type= 3
Up Slope=0.028
Dn Type= 0
Boundary for River Rch & Prof#=PetriesB,TR002           , 16
Up Type= 3
Up Slope=0.028
Dn Type= 0
Boundary for River Rch & Prof#=PetriesB,TR002           , 17
Up Type= 3
Up Slope=0.028
Dn Type= 0
Boundary for River Rch & Prof#=PetriesB,TR002           , 18
Up Type= 3
Up Slope=0.028
Dn Type= 0
Boundary for River Rch & Prof#=PetriesB,TR002           , 19
Up Type= 3
Up Slope=0.028
Dn Type= 0
Boundary for River Rch & Prof#=PetriesB,TR002           , 20
Up Type= 3
Up Slope=0.028
Dn Type= 0
Boundary for River Rch & Prof#=PetriesB,TR002           , 21
Up Type= 3
Up Slope=0.028
Dn Type= 0
Boundary for River Rch & Prof#=PetriesB,TR003           , 1
Up Type= 3
Up Slope=0.018
Dn Type= 0
Boundary for River Rch & Prof#=PetriesB,TR003           , 2
Up Type= 3
Up Slope=0.018
Dn Type= 0
Boundary for River Rch & Prof#=PetriesB,TR003           , 3
Up Type= 3
Up Slope=0.018
Dn Type= 0
Boundary for River Rch & Prof#=PetriesB,TR003           , 4
Up Type= 3
Up Slope=0.018
Dn Type= 0
Boundary for River Rch & Prof#=PetriesB,TR003           , 5
Up Type= 3
Up Slope=0.018
Dn Type= 0
Boundary for River Rch & Prof#=PetriesB,TR003           , 6
Up Type= 3
Up Slope=0.018
Dn Type= 0
Boundary for River Rch & Prof#=PetriesB,TR003           , 7
Up Type= 3
Up Slope=0.018
Dn Type= 0
Boundary for River Rch & Prof#=PetriesB,TR003           , 8
Up Type= 3
Up Slope=0.018
Dn Type= 0
Boundary for River Rch & Prof#=PetriesB,TR003           , 9
Up Type= 3
Up Slope=0.018
Dn Type= 0
Boundary for River Rch & Prof#=PetriesB,TR003           , 10
Up Type= 3
Up Slope=0.018
Dn Type= 0
Boundary for River Rch & Prof#=PetriesB,TR003           , 11
Up Type= 3
Up Slope=0.018
Dn Type= 0
Boundary for River Rch & Prof#=PetriesB,TR003           , 12
Up Type= 3
Up Slope=0.018
Dn Type= 0
Boundary for River Rch & Prof#=PetriesB,TR003           , 13
Up Type= 3
Up Slope=0.018
Dn Type= 0
Boundary for River Rch & Prof#=PetriesB,TR003           , 14
Up Type= 3
Up Slope=0.018
Dn Type= 0
Boundary for River Rch & Prof#=PetriesB,TR003           , 15
Up Type= 3
Up Slope=0.018
Dn Type= 0
Boundary for River Rch & Prof#=PetriesB,TR003           , 16
Up Type= 3
Up Slope=0.018
Dn Type= 0
Boundary for River Rch & Prof#=PetriesB,TR003           , 17
Up Type= 3
Up Slope=0.018
Dn Type= 0
Boundary for River Rch & Prof#=PetriesB,TR003           , 18
Up Type= 3
Up Slope=0.018
Dn Type= 0
Boundary for River Rch & Prof#=PetriesB,TR003           , 19
Up Type= 3
Up Slope=0.018
Dn Type= 0
Boundary for River Rch & Prof#=PetriesB,TR003           , 20
Up Type= 3
Up Slope=0.018
Dn Type= 0
Boundary for River Rch & Prof#=PetriesB,TR003           , 21
Up Type= 3
Up Slope=0.018
Dn Type= 0
Boundary for River Rch & Prof#=PetriesB,M002            , 1
Up Type= 0
Dn Type= 0
Boundary for River Rch & Prof#=PetriesB,M002            , 2
Up Type= 0
Dn Type= 0
Boundary for River Rch & Prof#=PetriesB,M002            , 3
Up Type= 0
Dn Type= 0
Boundary for River Rch & Prof#=PetriesB,M002            , 4
Up Type= 0
Dn Type= 0
Boundary for River Rch & Prof#=PetriesB,M002            , 5
Up Type= 0
Dn Type= 0
Boundary for River Rch & Prof#=PetriesB,M002            , 6
Up Type= 0
Dn Type= 0
Boundary for River Rch & Prof#=PetriesB,M002            , 7
Up Type= 0
Dn Type= 0
Boundary for River Rch & Prof#=PetriesB,M002            , 8
Up Type= 0
Dn Type= 0
Boundary for River Rch & Prof#=PetriesB,M002            , 9
Up Type= 0
Dn Type= 0
Boundary for River Rch & Prof#=PetriesB,M002            , 10
Up Type= 0
Dn Type= 0
Boundary for River Rch & Prof#=PetriesB,M002            , 11
Up Type= 0
Dn Type= 0
Boundary for River Rch & Prof#=PetriesB,M002            , 12
Up Type= 0
Dn Type= 0
Boundary for River Rch & Prof#=PetriesB,M002            , 13
Up Type= 0
Dn Type= 0
Boundary for River Rch & Prof#=PetriesB,M002            , 14
Up Type= 0
Dn Type= 0
Boundary for River Rch & Prof#=PetriesB,M002            , 15
Up Type= 0
Dn Type= 0
Boundary for River Rch & Prof#=PetriesB,M002            , 16
Up Type= 0
Dn Type= 0
Boundary for River Rch & Prof#=PetriesB,M002            , 17
Up Type= 0
Dn Type= 0
Boundary for River Rch & Prof#=PetriesB,M002            , 18
Up Type= 0
Dn Type= 0
Boundary for River Rch & Prof#=PetriesB,M002            , 19
Up Type= 0
Dn Type= 0
Boundary for River Rch & Prof#=PetriesB,M002            , 20
Up Type= 0
Dn Type= 0
Boundary for River Rch & Prof#=PetriesB,M002            , 21
Up Type= 0
Dn Type= 0
Boundary for River Rch & Prof#=PetriesB,TR001           , 1
Up Type= 3
Up Slope=0.015
Dn Type= 0
Boundary for River Rch & Prof#=PetriesB,TR001           , 2
Up Type= 3
Up Slope=0.015
Dn Type= 0
Boundary for River Rch & Prof#=PetriesB,TR001           , 3
Up Type= 3
Up Slope=0.015
Dn Type= 0
Boundary for River Rch & Prof#=PetriesB,TR001           , 4
Up Type= 3
Up Slope=0.015
Dn Type= 0
Boundary for River Rch & Prof#=PetriesB,TR001           , 5
Up Type= 3
Up Slope=0.015
Dn Type= 0
Boundary for River Rch & Prof#=PetriesB,TR001           , 6
Up Type= 3
Up Slope=0.015
Dn Type= 0
Boundary for River Rch & Prof#=PetriesB,TR001           , 7
Up Type= 3
Up Slope=0.015
Dn Type= 0
Boundary for River Rch & Prof#=PetriesB,TR001           , 8
Up Type= 3
Up Slope=0.015
Dn Type= 0
Boundary for River Rch & Prof#=PetriesB,TR001           , 9
Up Type= 3
Up Slope=0.015
Dn Type= 0
Boundary for River Rch & Prof#=PetriesB,TR001           , 10
Up Type= 3
Up Slope=0.015
Dn Type= 0
Boundary for River Rch & Prof#=PetriesB,TR001           , 11
Up Type= 3
Up Slope=0.015
Dn Type= 0
Boundary for River Rch & Prof#=PetriesB,TR001           , 12
Up Type= 3
Up Slope=0.015
Dn Type= 0
Boundary for River Rch & Prof#=PetriesB,TR001           , 13
Up Type= 3
Up Slope=0.015
Dn Type= 0
Boundary for River Rch & Prof#=PetriesB,TR001           , 14
Up Type= 3
Up Slope=0.015
Dn Type= 0
Boundary for River Rch & Prof#=PetriesB,TR001           , 15
Up Type= 3
Up Slope=0.015
Dn Type= 0
Boundary for River Rch & Prof#=PetriesB,TR001           , 16
Up Type= 3
Up Slope=0.015
Dn Type= 0
Boundary for River Rch & Prof#=PetriesB,TR001           , 17
Up Type= 3
Up Slope=0.015
Dn Type= 0
Boundary for River Rch & Prof#=PetriesB,TR001           , 18
Up Type= 3
Up Slope=0.015
Dn Type= 0
Boundary for River Rch & Prof#=PetriesB,TR001           , 19
Up Type= 3
Up Slope=0.015
Dn Type= 0
Boundary for River Rch & Prof#=PetriesB,TR001           , 20
Up Type= 3
Up Slope=0.015
Dn Type= 0
Boundary for River Rch & Prof#=PetriesB,TR001           , 21
Up Type= 3
Up Slope=0.015
Dn Type= 0
Boundary for River Rch & Prof#=PetriesB,M001            , 1
Up Type= 0
Dn Type= 1
Dn Known WS=2.8
Boundary for River Rch & Prof#=PetriesB,M001            , 2
Up Type= 0
Dn Type= 1
Dn Known WS=2.85
Boundary for River Rch & Prof#=PetriesB,M001            , 3
Up Type= 0
Dn Type= 1
Dn Known WS=2.85
Boundary for River Rch & Prof#=PetriesB,M001            , 4
Up Type= 0
Dn Type= 1
Dn Known WS=3.03
Boundary for River Rch & Prof#=PetriesB,M001            , 5
Up Type= 0
Dn Type= 1
Dn Known WS=3.03
Boundary for River Rch & Prof#=PetriesB,M001            , 6
Up Type= 0
Dn Type= 1
Dn Known WS=3.36
Boundary for River Rch & Prof#=PetriesB,M001            , 7
Up Type= 0
Dn Type= 1
Dn Known WS=3.36
Boundary for River Rch & Prof#=PetriesB,M001            , 8
Up Type= 0
Dn Type= 1
Dn Known WS=3.03
Boundary for River Rch & Prof#=PetriesB,M001            , 9
Up Type= 0
Dn Type= 1
Dn Known WS=3.03
Boundary for River Rch & Prof#=PetriesB,M001            , 10
Up Type= 0
Dn Type= 1
Dn Known WS=2.85
Boundary for River Rch & Prof#=PetriesB,M001            , 11
Up Type= 0
Dn Type= 1
Dn Known WS=2.85
Boundary for River Rch & Prof#=PetriesB,M001            , 12
Up Type= 0
Dn Type= 1
Dn Known WS=3.03
Boundary for River Rch & Prof#=PetriesB,M001            , 13
Up Type= 0
Dn Type= 1
Dn Known WS=3.03
Boundary for River Rch & Prof#=PetriesB,M001            , 14
Up Type= 0
Dn Type= 1
Dn Known WS=3.36
Boundary for River Rch & Prof#=PetriesB,M001            , 15
Up Type= 0
Dn Type= 1
Dn Known WS=3.36
Boundary for River Rch & Prof#=PetriesB,M001            , 16
Up Type= 0
Dn Type= 1
Dn Known WS=2.85
Boundary for River Rch & Prof#=PetriesB,M001            , 17
Up Type= 0
Dn Type= 1
Dn Known WS=2.85
Boundary for River Rch & Prof#=PetriesB,M001            , 18
Up Type= 0
Dn Type= 1
Dn Known WS=3.03
Boundary for River Rch & Prof#=PetriesB,M001            , 19
Up Type= 0
Dn Type= 1
Dn Known WS=3.03
Boundary for River Rch & Prof#=PetriesB,M001            , 20
Up Type= 0
Dn Type= 1
Dn Known WS=3.36
Boundary for River Rch & Prof#=PetriesB,M001            , 21
Up Type= 0
Dn Type= 1
Dn Known WS=3.36
DSS Import GetInterval= 0
DSS Import GetPeak= 0
DSS Import FillOption= 0

--- PetriesBrk_v001.f02 (steady flow) ---

Flow Title=Petries-Flow-20yr
Program Version=4.10
Number of Profiles= 21
Profile Names=20Year-Existing,FINIIS-20yr-2050-90%,FINIIS-20yr-2050-Max,AMEC-20yr-2020-90%,AMEC-20yr-2020-Max,AMEC-20yr-2050-90%,AMEC-20yr-2050-Max,AMEC-20yr-2080-90%,AMEC-20yr-2080-Max,CGCM2-20yr-2020-90%,CGCM2-20yr-2020-Max,CGCM2-20yr-2050-90%,CGCM2-20yr-2050-Max,CGCM2-20yr-2080-90%,CGCM2-20yr-2080-Max,HADCM3-20yr-2020-90%,HADCM3-20yr-2020-Max,HADCM3-20yr-2050-90%,HADCM3-20yr-2050-Max,HADCM3-20yr-2080-90%,HADCM3-20yr-2080-Max
River Rch & RM=PetriesB,TR002           ,65.82
     3.1     7.6     7.4     3.4     3.7     3.6     3.7     3.7       4     5.2
       5     5.4     5.3     6.5     6.5     4.2       4     6.9     6.7     4.9
     4.9
River Rch & RM=PetriesB,TR003           ,75.44
     1.9     4.8     4.7     2.1     2.3     2.2     2.3     2.3     2.5     3.3
     3.1     3.4     3.3     4.1     4.1     2.6     2.5     4.4     4.3     3.1
     3.1
River Rch & RM=PetriesB,M002            ,2878.54
     6.2    15.6    15.3     6.9     7.4     7.2     7.5     7.4       8    10.7
    10.2      11    10.8    13.3    13.3     8.5     8.1    14.1    13.8     9.9
     9.9
River Rch & RM=PetriesB,M002            ,2636.80
     6.6    16.2    16.1     7.4       8     7.7       8     7.9     8.6    11.3
    10.8    11.7    11.5      14    13.9     9.1     8.7    14.7    14.4    10.4
    10.6
River Rch & RM=PetriesB,TR001           ,194.22
     4.9    11.6    11.4     5.4     5.8     5.7     5.9     5.9     6.3     8.2
     7.8     8.4     8.3      10    10.1     6.6     6.3    10.6    10.4     7.6
     7.7
River Rch & RM=PetriesB,M001            ,2036.68
    11.3    27.6    27.2    12.5    13.5    13.1    13.6    13.5    14.6    19.2
    18.3    19.9    19.5    23.7    23.7    15.5    14.8      25    24.5    17.8
    17.9
River Rch & RM=PetriesB,M001            ,1790.83
    12.9    31.8    31.3    14.4    15.5      15    15.7    15.6    16.8    22.1
    21.1    22.8    22.4    27.3    27.3    17.8      17    28.8    28.2    20.5
    20.6
River Rch & RM=PetriesB,M001            ,1418.45
    13.4    33.4    32.8    14.9    16.1    15.6    16.3    16.1    17.4    22.9
    21.9    23.7    23.3    28.5    28.7    18.3    17.5    30.3    29.6    21.2
    21.4
River Rch & RM=PetriesB,M001            ,1131.36
    13.5    33.4    32.8      15    16.1    15.6    16.3    16.2    17.5    22.9
    21.9    23.7    23.2    28.5    28.6    18.4    17.6    30.2    29.6    21.2
    21.4
River Rch & RM=PetriesB,M001            ,1036.63
    14.1    35.1    34.4    15.8      17    16.4    17.2    17.1    18.5    24.1
    23.1      25    24.5    29.8      30    19.5    18.6    31.7      31    22.5
    22.7
River Rch & RM=PetriesB,M001            ,599.17
    14.1    34.8    34.2    15.7      17    16.4    17.2      17    18.4    24.2
    23.1      25    24.5    29.9    30.1    19.4    18.6    31.6      31    22.5
    22.6
River Rch & RM=PetriesB,M001            ,399.97
    15.3    38.2    37.4    17.1    18.5    17.8    18.7    18.5      20    26.3
    25.2    27.2    26.7    32.6    32.8    21.2    20.3    34.5    33.8    24.5
    24.7
River Rch & RM=PetriesB,M001            ,200
    15.3    38.9    38.2    17.2    18.6    17.9    18.9    18.7    20.2    26.8
    25.6    27.7    27.2    33.3    33.5    21.4    20.5    35.3    34.6    24.8
      25
Boundary for River Rch & Prof#=PetriesB,TR002           , 1
Up Type= 3
Up Slope=0.028
Dn Type= 0
Boundary for River Rch & Prof#=PetriesB,TR002           , 2
Up Type= 3
Up Slope=0.028
Dn Type= 0
Boundary for River Rch & Prof#=PetriesB,TR002           , 3
Up Type= 3
Up Slope=0.028
Dn Type= 0
Boundary for River Rch & Prof#=PetriesB,TR002           , 4
Up Type= 3
Up Slope=0.028
Dn Type= 0
Boundary for River Rch & Prof#=PetriesB,TR002           , 5
Up Type= 3
Up Slope=0.028
Dn Type= 0
Boundary for River Rch & Prof#=PetriesB,TR002           , 6
Up Type= 3
Up Slope=0.028
Dn Type= 0
Boundary for River Rch & Prof#=PetriesB,TR002           , 7
Up Type= 3
Up Slope=0.028
Dn Type= 0
Boundary for River Rch & Prof#=PetriesB,TR002           , 8
Up Type= 3
Up Slope=0.028
Dn Type= 0
Boundary for River Rch & Prof#=PetriesB,TR002           , 9
Up Type= 3
Up Slope=0.028
Dn Type= 0
Boundary for River Rch & Prof#=PetriesB,TR002           , 10
Up Type= 3
Up Slope=0.028
Dn Type= 0
Boundary for River Rch & Prof#=PetriesB,TR002           , 11
Up Type= 3
Up Slope=0.028
Dn Type= 0
Boundary for River Rch & Prof#=PetriesB,TR002           , 12
Up Type= 3
Up Slope=0.028
Dn Type= 0
Boundary for River Rch & Prof#=PetriesB,TR002           , 13
Up Type= 3
Up Slope=0.028
Dn Type= 0
Boundary for River Rch & Prof#=PetriesB,TR002           , 14
Up Type= 3
Up Slope=0.028
Dn Type= 0
Boundary for River Rch & Prof#=PetriesB,TR002           , 15
Up Type= 3
Up Slope=0.028
Dn Type= 0
Boundary for River Rch & Prof#=PetriesB,TR002           , 16
Up Type= 3
Up Slope=0.028
Dn Type= 0
Boundary for River Rch & Prof#=PetriesB,TR002           , 17
Up Type= 3
Up Slope=0.028
Dn Type= 0
Boundary for River Rch & Prof#=PetriesB,TR002           , 18
Up Type= 3
Up Slope=0.028
Dn Type= 0
Boundary for River Rch & Prof#=PetriesB,TR002           , 19
Up Type= 3
Up Slope=0.028
Dn Type= 0
Boundary for River Rch & Prof#=PetriesB,TR002           , 20
Up Type= 3
Up Slope=0.028
Dn Type= 0
Boundary for River Rch & Prof#=PetriesB,TR002           , 21
Up Type= 3
Up Slope=0.028
Dn Type= 0
Boundary for River Rch & Prof#=PetriesB,TR003           , 1
Up Type= 3
Up Slope=0.018
Dn Type= 0
Boundary for River Rch & Prof#=PetriesB,TR003           , 2
Up Type= 3
Up Slope=0.018
Dn Type= 0
Boundary for River Rch & Prof#=PetriesB,TR003           , 3
Up Type= 3
Up Slope=0.018
Dn Type= 0
Boundary for River Rch & Prof#=PetriesB,TR003           , 4
Up Type= 3
Up Slope=0.018
Dn Type= 0
Boundary for River Rch & Prof#=PetriesB,TR003           , 5
Up Type= 3
Up Slope=0.018
Dn Type= 0
Boundary for River Rch & Prof#=PetriesB,TR003           , 6
Up Type= 3
Up Slope=0.018
Dn Type= 0
Boundary for River Rch & Prof#=PetriesB,TR003           , 7
Up Type= 3
Up Slope=0.018
Dn Type= 0
Boundary for River Rch & Prof#=PetriesB,TR003           , 8
Up Type= 3
Up Slope=0.018
Dn Type= 0
Boundary for River Rch & Prof#=PetriesB,TR003           , 9
Up Type= 3
Up Slope=0.018
Dn Type= 0
Boundary for River Rch & Prof#=PetriesB,TR003           , 10
Up Type= 3
Up Slope=0.018
Dn Type= 0
Boundary for River Rch & Prof#=PetriesB,TR003           , 11
Up Type= 3
Up Slope=0.018
Dn Type= 0
Boundary for River Rch & Prof#=PetriesB,TR003           , 12
Up Type= 3
Up Slope=0.018
Dn Type= 0
Boundary for River Rch & Prof#=PetriesB,TR003           , 13
Up Type= 3
Up Slope=0.018
Dn Type= 0
Boundary for River Rch & Prof#=PetriesB,TR003           , 14
Up Type= 3
Up Slope=0.018
Dn Type= 0
Boundary for River Rch & Prof#=PetriesB,TR003           , 15
Up Type= 3
Up Slope=0.018
Dn Type= 0
Boundary for River Rch & Prof#=PetriesB,TR003           , 16
Up Type= 3
Up Slope=0.018
Dn Type= 0
Boundary for River Rch & Prof#=PetriesB,TR003           , 17
Up Type= 3
Up Slope=0.018
Dn Type= 0
Boundary for River Rch & Prof#=PetriesB,TR003           , 18
Up Type= 3
Up Slope=0.018
Dn Type= 0
Boundary for River Rch & Prof#=PetriesB,TR003           , 19
Up Type= 3
Up Slope=0.018
Dn Type= 0
Boundary for River Rch & Prof#=PetriesB,TR003           , 20
Up Type= 3
Up Slope=0.018
Dn Type= 0
Boundary for River Rch & Prof#=PetriesB,TR003           , 21
Up Type= 3
Up Slope=0.018
Dn Type= 0
Boundary for River Rch & Prof#=PetriesB,M002            , 1
Up Type= 0
Dn Type= 0
Boundary for River Rch & Prof#=PetriesB,M002            , 2
Up Type= 0
Dn Type= 0
Boundary for River Rch & Prof#=PetriesB,M002            , 3
Up Type= 0
Dn Type= 0
Boundary for River Rch & Prof#=PetriesB,M002            , 4
Up Type= 0
Dn Type= 0
Boundary for River Rch & Prof#=PetriesB,M002            , 5
Up Type= 0
Dn Type= 0
Boundary for River Rch & Prof#=PetriesB,M002            , 6
Up Type= 0
Dn Type= 0
Boundary for River Rch & Prof#=PetriesB,M002            , 7
Up Type= 0
Dn Type= 0
Boundary for River Rch & Prof#=PetriesB,M002            , 8
Up Type= 0
Dn Type= 0
Boundary for River Rch & Prof#=PetriesB,M002            , 9
Up Type= 0
Dn Type= 0
Boundary for River Rch & Prof#=PetriesB,M002            , 10
Up Type= 0
Dn Type= 0
Boundary for River Rch & Prof#=PetriesB,M002            , 11
Up Type= 0
Dn Type= 0
Boundary for River Rch & Prof#=PetriesB,M002            , 12
Up Type= 0
Dn Type= 0
Boundary for River Rch & Prof#=PetriesB,M002            , 13
Up Type= 0
Dn Type= 0
Boundary for River Rch & Prof#=PetriesB,M002            , 14
Up Type= 0
Dn Type= 0
Boundary for River Rch & Prof#=PetriesB,M002            , 15
Up Type= 0
Dn Type= 0
Boundary for River Rch & Prof#=PetriesB,M002            , 16
Up Type= 0
Dn Type= 0
Boundary for River Rch & Prof#=PetriesB,M002            , 17
Up Type= 0
Dn Type= 0
Boundary for River Rch & Prof#=PetriesB,M002            , 18
Up Type= 0
Dn Type= 0
Boundary for River Rch & Prof#=PetriesB,M002            , 19
Up Type= 0
Dn Type= 0
Boundary for River Rch & Prof#=PetriesB,M002            , 20
Up Type= 0
Dn Type= 0
Boundary for River Rch & Prof#=PetriesB,M002            , 21
Up Type= 0
Dn Type= 0
Boundary for River Rch & Prof#=PetriesB,TR001           , 1
Up Type= 3
Up Slope=0.015
Dn Type= 0
Boundary for River Rch & Prof#=PetriesB,TR001           , 2
Up Type= 3
Up Slope=0.015
Dn Type= 0
Boundary for River Rch & Prof#=PetriesB,TR001           , 3
Up Type= 3
Up Slope=0.015
Dn Type= 0
Boundary for River Rch & Prof#=PetriesB,TR001           , 4
Up Type= 3
Up Slope=0.015
Dn Type= 0
Boundary for River Rch & Prof#=PetriesB,TR001           , 5
Up Type= 3
Up Slope=0.015
Dn Type= 0
Boundary for River Rch & Prof#=PetriesB,TR001           , 6
Up Type= 3
Up Slope=0.015
Dn Type= 0
Boundary for River Rch & Prof#=PetriesB,TR001           , 7
Up Type= 3
Up Slope=0.015
Dn Type= 0
Boundary for River Rch & Prof#=PetriesB,TR001           , 8
Up Type= 3
Up Slope=0.015
Dn Type= 0
Boundary for River Rch & Prof#=PetriesB,TR001           , 9
Up Type= 3
Up Slope=0.015
Dn Type= 0
Boundary for River Rch & Prof#=PetriesB,TR001           , 10
Up Type= 3
Up Slope=0.015
Dn Type= 0
Boundary for River Rch & Prof#=PetriesB,TR001           , 11
Up Type= 3
Up Slope=0.015
Dn Type= 0
Boundary for River Rch & Prof#=PetriesB,TR001           , 12
Up Type= 3
Up Slope=0.015
Dn Type= 0
Boundary for River Rch & Prof#=PetriesB,TR001           , 13
Up Type= 3
Up Slope=0.015
Dn Type= 0
Boundary for River Rch & Prof#=PetriesB,TR001           , 14
Up Type= 3
Up Slope=0.015
Dn Type= 0
Boundary for River Rch & Prof#=PetriesB,TR001           , 15
Up Type= 3
Up Slope=0.015
Dn Type= 0
Boundary for River Rch & Prof#=PetriesB,TR001           , 16
Up Type= 3
Up Slope=0.015
Dn Type= 0
Boundary for River Rch & Prof#=PetriesB,TR001           , 17
Up Type= 3
Up Slope=0.015
Dn Type= 0
Boundary for River Rch & Prof#=PetriesB,TR001           , 18
Up Type= 3
Up Slope=0.015
Dn Type= 0
Boundary for River Rch & Prof#=PetriesB,TR001           , 19
Up Type= 3
Up Slope=0.015
Dn Type= 0
Boundary for River Rch & Prof#=PetriesB,TR001           , 20
Up Type= 3
Up Slope=0.015
Dn Type= 0
Boundary for River Rch & Prof#=PetriesB,TR001           , 21
Up Type= 3
Up Slope=0.015
Dn Type= 0
Boundary for River Rch & Prof#=PetriesB,M001            , 1
Up Type= 0
Dn Type= 1
Dn Known WS=2.8
Boundary for River Rch & Prof#=PetriesB,M001            , 2
Up Type= 0
Dn Type= 1
Dn Known WS=3.03
Boundary for River Rch & Prof#=PetriesB,M001            , 3
Up Type= 0
Dn Type= 1
Dn Known WS=3.03
Boundary for River Rch & Prof#=PetriesB,M001            , 4
Up Type= 0
Dn Type= 1
Dn Known WS=2.85
Boundary for River Rch & Prof#=PetriesB,M001            , 5
Up Type= 0
Dn Type= 1
Dn Known WS=2.85
Boundary for River Rch & Prof#=PetriesB,M001            , 6
Up Type= 0
Dn Type= 1
Dn Known WS=3.03
Boundary for River Rch & Prof#=PetriesB,M001            , 7
Up Type= 0
Dn Type= 1
Dn Known WS=3.03
Boundary for River Rch & Prof#=PetriesB,M001            , 8
Up Type= 0
Dn Type= 1
Dn Known WS=3.36
Boundary for River Rch & Prof#=PetriesB,M001            , 9
Up Type= 0
Dn Type= 1
Dn Known WS=3.36
Boundary for River Rch & Prof#=PetriesB,M001            , 10
Up Type= 0
Dn Type= 1
Dn Known WS=2.85
Boundary for River Rch & Prof#=PetriesB,M001            , 11
Up Type= 0
Dn Type= 1
Dn Known WS=2.85
Boundary for River Rch & Prof#=PetriesB,M001            , 12
Up Type= 0
Dn Type= 1
Dn Known WS=3.03
Boundary for River Rch & Prof#=PetriesB,M001            , 13
Up Type= 0
Dn Type= 1
Dn Known WS=3.03
Boundary for River Rch & Prof#=PetriesB,M001            , 14
Up Type= 0
Dn Type= 1
Dn Known WS=3.36
Boundary for River Rch & Prof#=PetriesB,M001            , 15
Up Type= 0
Dn Type= 1
Dn Known WS=3.36
Boundary for River Rch & Prof#=PetriesB,M001            , 16
Up Type= 0
Dn Type= 1
Dn Known WS=2.85
Boundary for River Rch & Prof#=PetriesB,M001            , 17
Up Type= 0
Dn Type= 1
Dn Known WS=2.85
Boundary for River Rch & Prof#=PetriesB,M001            , 18
Up Type= 0
Dn Type= 1
Dn Known WS=3.03
Boundary for River Rch & Prof#=PetriesB,M001            , 19
Up Type= 0
Dn Type= 1
Dn Known WS=3.03
Boundary for River Rch & Prof#=PetriesB,M001            , 20
Up Type= 0
Dn Type= 1
Dn Known WS=3.36
Boundary for River Rch & Prof#=PetriesB,M001            , 21
Up Type= 0
Dn Type= 1
Dn Known WS=3.36
DSS Import GetInterval= 0
DSS Import GetPeak= 0
DSS Import FillOption= 0

--- PetriesBrk_v001.g01 (geometry) ---

Geom Title=PetriesBrook-with below waterline
Program Version=4.10

Junct Name=1
Junct Desc=, 0 , 0 ,-1 ,0
Up River,Reach=PetriesB        ,M002
Up River,Reach=PetriesB        ,TR001
Dn River,Reach=PetriesB        ,M001
Junc L&A=48.96,0
Junc L&A=50,0

Junct Name=4
Junct Desc=, 0 , 0 ,-1 ,0
Up River,Reach=PetriesB        ,TR003
Up River,Reach=PetriesB        ,TR002
Dn River,Reach=PetriesB        ,M002
Junc L&A=31.52,0
Junc L&A=26.4,0

River Reach=PetriesB        ,TR002
Reach XY= 7
340079.3427124025422705.46368408340100.8936767585422707.10247803
340122.6793212895422715.99969482340135.0947265635422726.53570557
340147.1550903325422742.42529297 340152.191284185422752.03527832
340154.0706787115422755.21411133

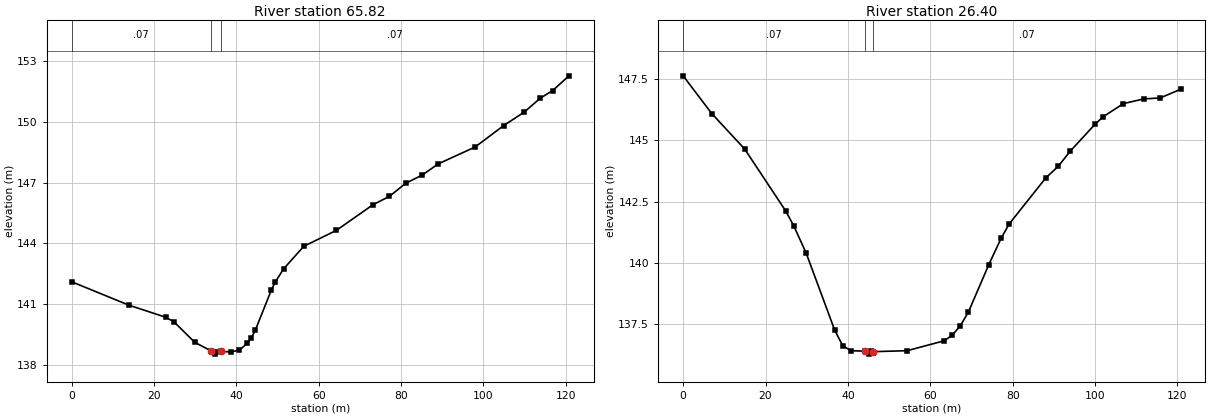
Type RM Length L Ch R = 1 ,65.82   ,40.91,39.42,39.37
XS GIS Cut Line= 4
340073.6801147465422710.47229004340108.5366821295422710.47229004
340123.9555053715422698.47290039340117.2152709965422632.45147705
#Sta/Elev= 30
       0   142.1   13.94  140.94   22.91  140.34    24.9  140.11   29.88  139.11
   33.86  138.68   34.86  138.52   35.07  138.62   36.28  138.65   38.76  138.63
   40.72  138.72   42.67  139.05   43.65  139.32   44.63  139.71   48.53   141.7
   49.51   142.1   51.46  142.73   56.38  143.85    64.3  144.64   73.21  145.91
   77.18  146.32   81.14  146.97    85.1  147.37   89.06  147.93   97.98  148.76
  104.91  149.82  109.86  150.48  113.83  151.18   116.8  151.55  120.76  152.28
#Mann= 3 , 0 , 0
       0     .07       0   33.86     .04       0   36.28     .07       0
Bank Sta=33.86,36.28
XS Rating Curve= 0 ,0
Exp/Cntr=0.3,0.1

Type RM Length L Ch R = 1 ,26.40   ,26.39,26.4,26.39
XS GIS Cut Line= 4
340096.9918823245422739.31469727340131.8485107425422739.31469727
340147.2672729495422727.31530762340140.5270996095422661.29388428
#Sta/Elev= 30
       0  147.62    6.97  146.08   14.94  144.64    24.9  142.12   26.89   141.5
   29.88   140.4   36.81  137.26   38.76  136.63   40.72  136.43   44.17  136.41
   45.17  136.29    45.6   136.4   46.17  136.39   54.39  136.43   63.31  136.83
   65.29  137.05   67.27  137.44   69.25     138    74.2  139.93   77.18     141
   79.16  141.59   88.07  143.47   91.04  143.93   94.02  144.56   99.96  145.64
  101.94  145.95  106.89  146.49  111.84  146.68  115.81  146.72  120.76  147.07
#Mann= 3 , 0 , 0
       0     .07       0   44.17     .04       0   46.17     .07       0
Bank Sta=44.17,46.17
XS Rating Curve= 0 ,0
Exp/Cntr=0.3,0.1

River Reach=PetriesB        ,TR003
Reach XY= 30
     340211.3172    5422629.2283     340210.1665    5422631.5281
     340203.4267    5422635.4706      340199.317    5422638.9203
     340196.8513    5422643.1914     340197.8376    5422648.6124
     340198.3307     5422652.555     340197.0156     5422657.976
     340195.3718    5422660.4401     340195.5362    5422662.9042
     340197.0156    5422665.6968      340199.317    5422669.3108
      340200.139    5422672.7605     340198.6595    5422677.5244
     340194.3855    5422682.2883     340192.4128    5422684.9167
     340186.4949    5422688.0379     340183.8648    5422688.3664
     340177.2893    5422691.8162     340168.9057    5422702.9867
     340164.1175    5422714.0775340163.5208740235422718.72967529
340163.5957031255422722.29650879340162.4816894535422725.79571533
340161.5270996095422732.71447754340162.1635131845422737.56549072
340162.2034912115422740.30908203 340160.49029541 5422742.9967041
340156.3131103525422751.62530518340154.0706787115422755.21411133

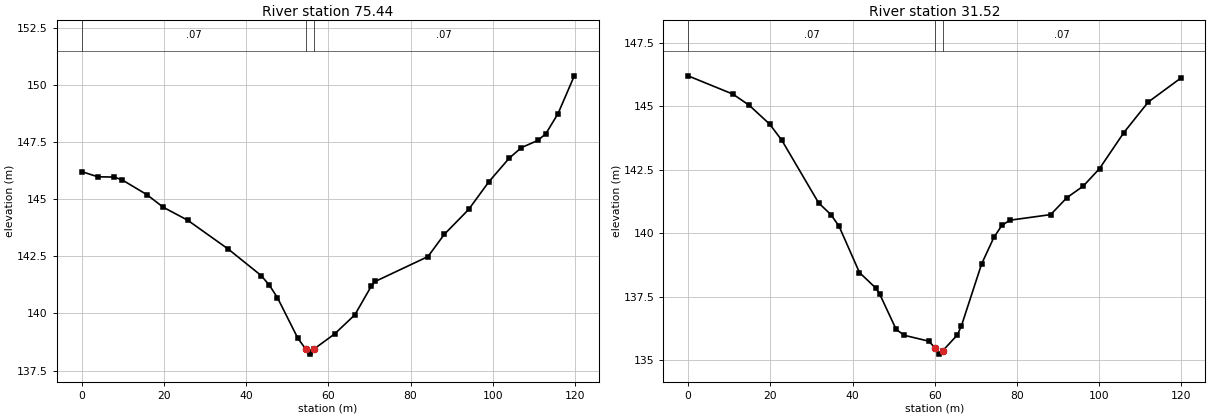
Type RM Length L Ch R = 1 ,75.44   ,44.72,44.75,44.78
XS GIS Cut Line= 3
340174.7932739265422633.26312256340180.9556884775422688.50531006
340244.9166870125422694.58850098
#Sta/Elev= 30
       0  146.21    3.97  145.98    7.94  145.97    9.93  145.84   15.88   145.2
   19.85  144.65   25.81  144.08   35.73  142.81   43.67  141.66   45.66  141.24
   47.64  140.69   52.61  138.91   54.49  138.45   55.53  138.22   55.58  138.32
   56.57  138.45   61.52   139.1   66.46  139.94   70.41  141.18    71.4   141.4
   84.25  142.49    88.2  143.46   94.13  144.55   99.08  145.77  104.02   146.8
  106.98  147.26  110.94  147.57  112.92  147.87  115.88  148.75  119.83   150.4
#Mann= 3 , 0 , 0
       0     .07       0   54.49     .04       0   56.57     .07       0
Bank Sta=54.49,56.57
XS Rating Curve= 0 ,0
Exp/Cntr=0.3,0.1

Type RM Length L Ch R = 1 ,31.52   ,31.52,31.52,31.52
XS GIS Cut Line= 3
340150.9263305665422670.14807129340157.0886840825422725.39031982
340221.0496826175422731.47351074
#Sta/Elev= 30
       0   146.2   10.92  145.48   14.89  145.04   19.85   144.3   22.83  143.66
   31.76   141.2   34.74  140.74   36.73  140.28   41.69  138.46   45.66  137.85
   46.65   137.6   50.62  136.22   52.61  135.99   58.55  135.76   59.99  135.51
   60.99  135.25   61.99  135.39   65.47     136   66.46  136.35    71.4   138.8
   74.37  139.84   76.34  140.32   78.32  140.52    88.2  140.74   92.16  141.41
   96.11  141.86  100.07  142.55     106  143.97  111.93  145.17  119.83  146.11
#Mann= 3 , 0 , 0
       0     .07       0   59.99     .04       0   61.99     .07       0
Bank Sta=59.99,61.99
XS Rating Curve= 0 ,0
Exp/Cntr=0.3,0.1

River Reach=PetriesB        ,M002
Reach XY= 30
340154.0706787115422755.21411133340153.0338745125422763.43969727
340164.6981201175422771.85968018 340168.871093755422789.63092041
340201.7111206055422814.05950928340217.2686767585422851.41967773
340213.999084473    5422864.6875340217.5957031255422894.36010742
340242.4683227545422927.16290283340262.9716796885422928.99969482
340286.5123291025422941.09088135340299.5979003915422983.33190918
340297.4398803715422993.33148193340284.2965087895423006.33789063
340301.9583129885423047.74353027340294.5012817385423083.21948242
340304.3043212895423154.63128662340293.6411132815423185.97412109
340294.8181152345423196.69268799 340276.181701665423212.05187988
 340274.746093755423220.91271973340282.265930176 5423243.0690918
 340280.380676275423261.12188721340293.6182861335423275.93670654
340296.6060791025423363.77508545340301.4562988285423399.82147217
 340308.541076665423414.91589355340301.9896850595423438.07507324
340308.1182861335423456.71112061 340318.699096685423466.61431885

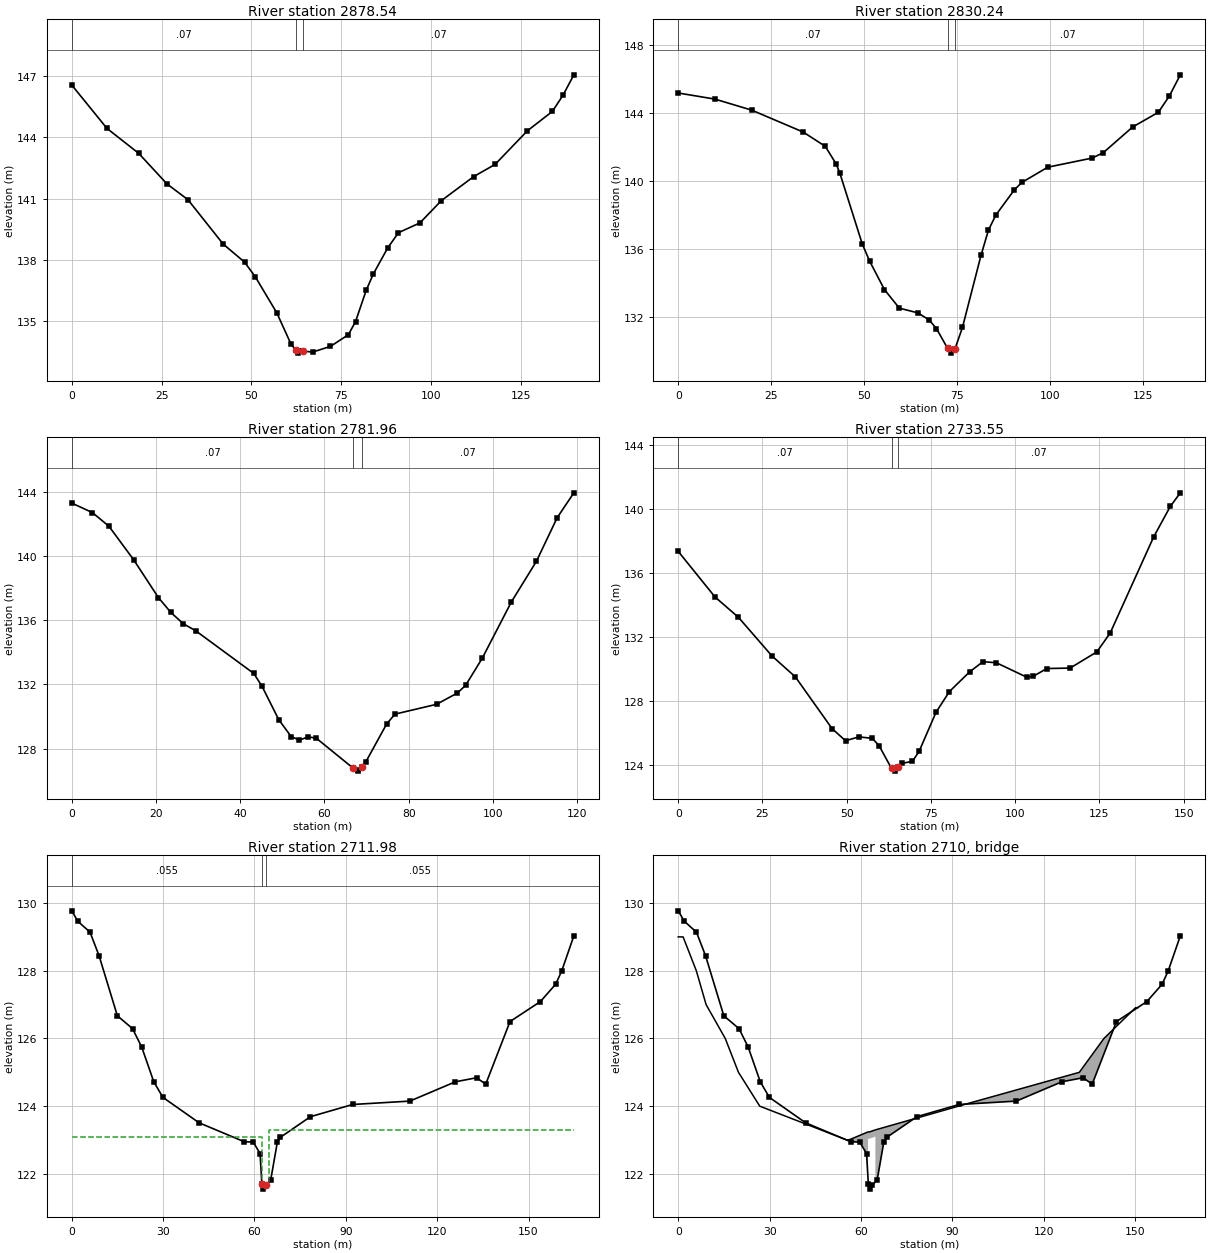
Type RM Length L Ch R = 1 ,2878.54 ,50.79,48.29,38.58
XS GIS Cut Line= 3
340090.1920776375422759.60351563340134.0516967775422764.35968018
340228.7479248055422751.03912354
#Sta/Elev= 30
       0  146.55     9.8  144.43   18.63  143.21   26.47  141.72   32.35  140.94
   42.16  138.77    48.1  137.89   51.09  137.17   57.07  135.41   61.05  133.87
   62.35   133.6   63.04  133.44   63.37  133.54   64.39  133.54   67.03  133.49
   72.01  133.77   76.99  134.34   78.98  134.98   81.97  136.52   83.96  137.32
   87.95  138.59   90.94  139.33   96.91  139.81  102.89   140.9  111.85  142.07
  117.83  142.67   126.8  144.31  133.77  145.26  136.76  146.06  139.75  147.05
#Mann= 3 , 0 , 0
       0     .07       0   62.35     .04       0   64.39     .07       0
Bank Sta=62.35,64.39
XS Rating Curve= 0 ,0
Exp/Cntr=0.3,0.1

Type RM Length L Ch R = 1 ,2830.24 ,43.24,48.28,50.69
XS GIS Cut Line= 4
340130.4509277345422845.89892578340164.290283203 5422818.6519165
340203.3007202155422761.96508789340225.6536865235422758.36230469
#Sta/Elev= 30
       0  145.18    9.87  144.82   19.75  144.17   33.57  142.88    39.5  142.04
   42.46  140.99   43.45  140.44   49.43   136.3   51.42  135.28   55.41   133.6
    59.4  132.51   64.39  132.23   67.38  131.82   69.37  131.31   72.37  130.14
   73.26  129.86   74.37  130.12   76.36  131.37   81.34  135.61   83.34   137.1
   85.33  137.99   90.32  139.48   92.31  139.91   99.29  140.81  111.26  141.35
  114.23  141.67   122.1  143.18  128.99  144.04  131.95     145   134.9  146.25
#Mann= 3 , 0 , 0
       0     .07       0   72.37     .04       0   74.37     .07       0
Bank Sta=72.37,74.37
XS Rating Curve= 0 ,0
Exp/Cntr=0.3,0.1

Type RM Length L Ch R = 1 ,2781.96 ,40.62,48.4,49.83
XS GIS Cut Line= 4
340147.6715087895422850.89367676340174.0516967775422853.05609131
340227.6585083015422819.77868652340242.3358764655422794.01208496
#Sta/Elev= 30
       0  143.29     4.9   142.7    8.82  141.85    14.7  139.76   20.59   137.4
   23.53  136.48   26.47  135.78   29.43  135.34   43.23  132.68    45.2  131.87
   49.14  129.81    52.1  128.75   54.07  128.53   56.04  128.73   58.02  128.66
   66.89  126.77   67.88   126.6   67.89   126.7   68.89  126.87   69.85  127.19
   74.78  129.54   76.75  130.15   86.61  130.76   91.54  131.46   93.52  131.94
   97.47  133.63  104.39  137.14  110.32  139.66  115.26  142.38  119.22  143.93
#Mann= 3 , 0 , 0
       0     .07       0   66.89     .04       0   68.89     .07       0
Bank Sta=66.89,68.89
XS Rating Curve= 0 ,0
Exp/Cntr=0.3,0.1

Type RM Length L Ch R = 1 ,2733.55 ,29.65,21.58,18.67
XS GIS Cut Line= 4
340151.7285156255422874.21551514340221.1448974615422877.53051758
340231.3322753915422844.14208984340250.9962768555422804.12329102
#Sta/Elev= 30
       0  137.35   10.92   134.5   17.87  133.23    27.8  130.82   34.75  129.51
   45.67  126.27   49.64  125.52   53.61  125.76   57.58  125.67   59.57  125.22
   63.29  123.79    64.3  123.62    65.3  123.88   66.52  124.11    69.5  124.23
   71.49  124.86   76.48  127.29   80.47  128.59   86.45  129.82   90.44  130.46
   94.43  130.39  103.41  129.49  105.39  129.55  109.36  130.03  116.29  130.06
  124.22  131.07  128.18  132.25  141.07  138.25  146.02  140.16  148.99  141.01
#Mann= 3 , 0 , 0
       0     .07       0   63.29     .04       0    65.3     .07       0
Bank Sta=63.29,65.3
XS Rating Curve= 0 ,0
Exp/Cntr=0.3,0.1

Type RM Length L Ch R = 1 ,2711.98 ,5.63,5.49,6.83
XS GIS Cut Line= 4
340170.403930664 5422932.1652832340189.3347167975422910.27807617
340268.4860839845422876.51367188340304.0363159185422841.51831055
#Sta/Elev= 30
       0  129.77       2  129.46    5.99  129.14    8.98  128.44   14.97  126.67
   19.96  126.29   22.95  125.75   26.94  124.72   29.93  124.26    41.8  123.51
   56.63  122.95    59.6  122.94   61.84   122.6   62.43   121.7   62.95  121.55
   63.71  121.66   65.35  121.83   67.51  122.94    68.5  123.08   78.39  123.69
   92.24  124.05  111.03  124.15  125.97  124.72  132.95  124.84  135.94  124.65
  143.92   126.5   153.9  127.09  158.89   127.6  160.88  127.99  164.88  129.03
#Mann= 3 , 0 , 0
       0    .055       0   62.43     .04       0   63.71    .055       0
#XS Ineff= 2 , 0
       0   62.34   123.1   64.74       0   123.3
Permanent Ineff=
       F       F
Bank Sta=62.43,63.71
XS Rating Curve= 0 ,0
Exp/Cntr=0.5,0.3

Type RM Length L Ch R = 3 ,2710    ,,,
BEGIN DESCRIPTION:
Private Access Road (1108)
ATV Trail (1108)
END DESCRIPTION:
Bridge Culvert--1,0,-1,-1, 0
Deck Dist Width WeirC Skew NumUp NumDn MinLoCord MaxHiCord MaxSubmerge Is_Ogee
1.3,2.8,1.67,0, 19, 24, 122.99, , 0.98, 0, 1,1,,
       0     1.6    5.94    9.15   15.44   19.78   26.78   55.43    56.5   62.33
   62.34    62.8   64.74   64.75   92.01  131.71   139.8   150.2  150.93
     129     129     128     127     126     125     124     123  123.02  123.24
  123.24  123.24   123.3   123.3     124     125     126  126.91  126.91
                                                           122.8  122.82     121
  123.04  123.04   123.1     121     122     122     122     122     122
       0     1.6    5.94    9.15   15.44   19.78   26.78   55.43   55.99   56.92
    57.7   57.71   60.12   60.13   60.94   60.98   61.93   62.92   63.91   92.01
  131.71   139.8   150.2  150.93
     129     129     128     127     126     125     124     123     123  122.98
     123     123  123.05  123.05  123.12  123.12  123.18  123.21  123.21     124
     125     126  126.91  126.91
                                                                  122.72   121.5
  121.42   122.8  122.85  121.28  121.43  121.45  121.95  122.48  122.86   123.8
                                
BR Coef=-1 , 0 , 0 ,, 0 ,,,0.8,-1,,0,
WSPro=,,,, 1 ,,,, 0 ,,,, 0 ,,,,-1 ,-1 ,-1 , 0 , 0 , 0 , 0 , 0
BC Design=,, 0 ,, 0 ,,,,,,
BC Use User HTab Curves=0
BC User HTab FreeFlow(D)= 0