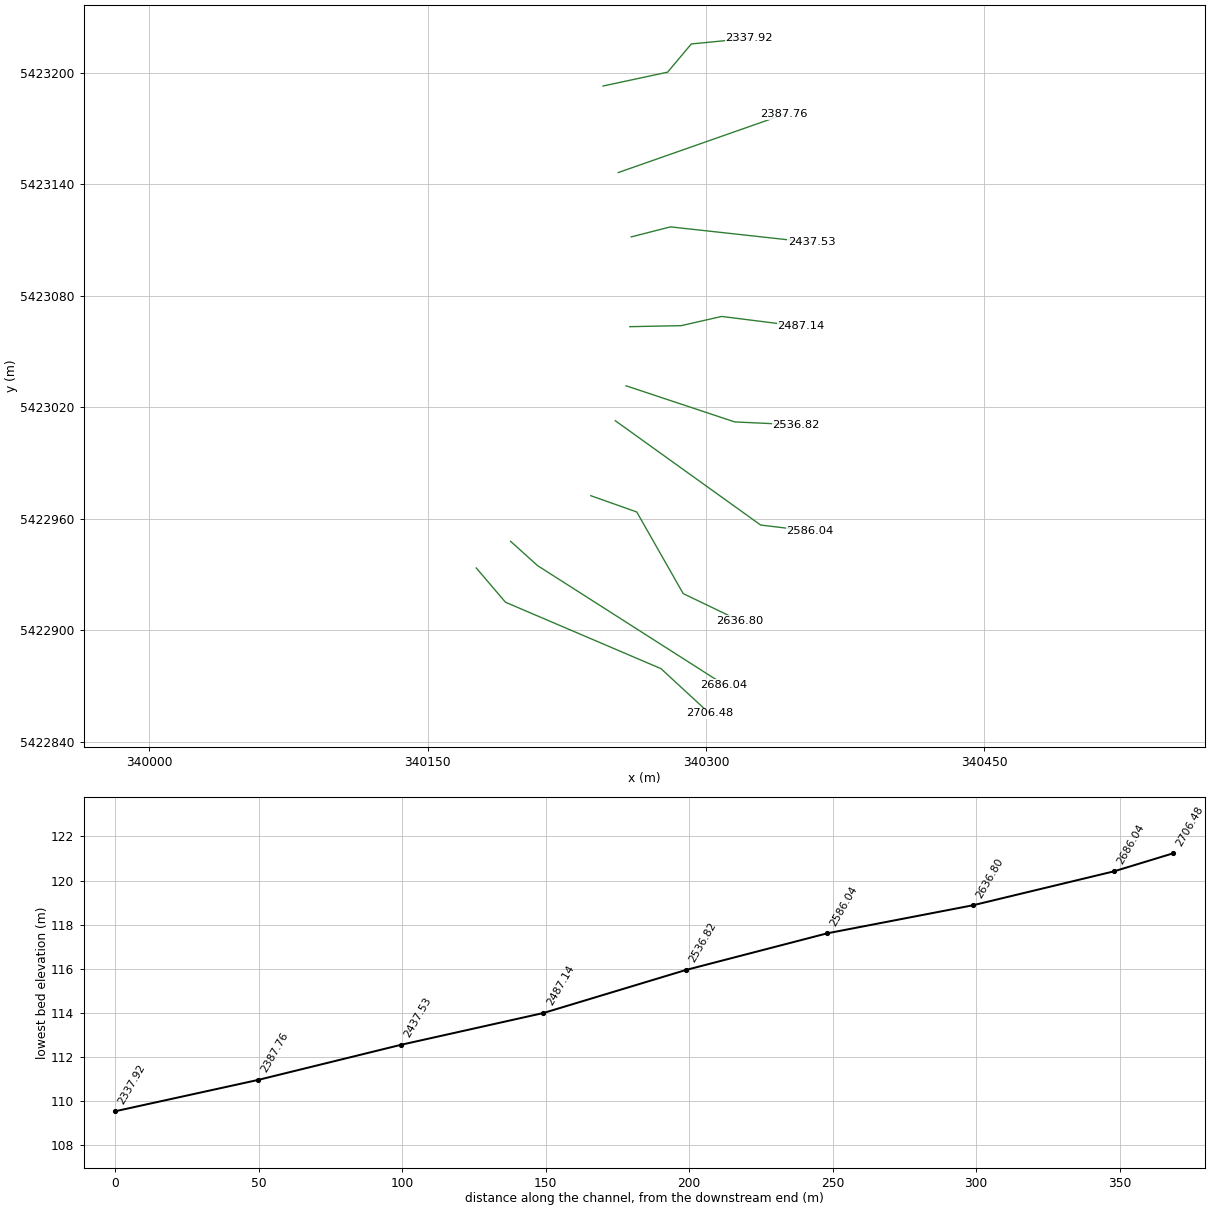
HEC-RAS study PetriesBrk_v001.prj: Petries_Brook

--- PetriesBrk_v001.g01 (geometry) --- (continued)

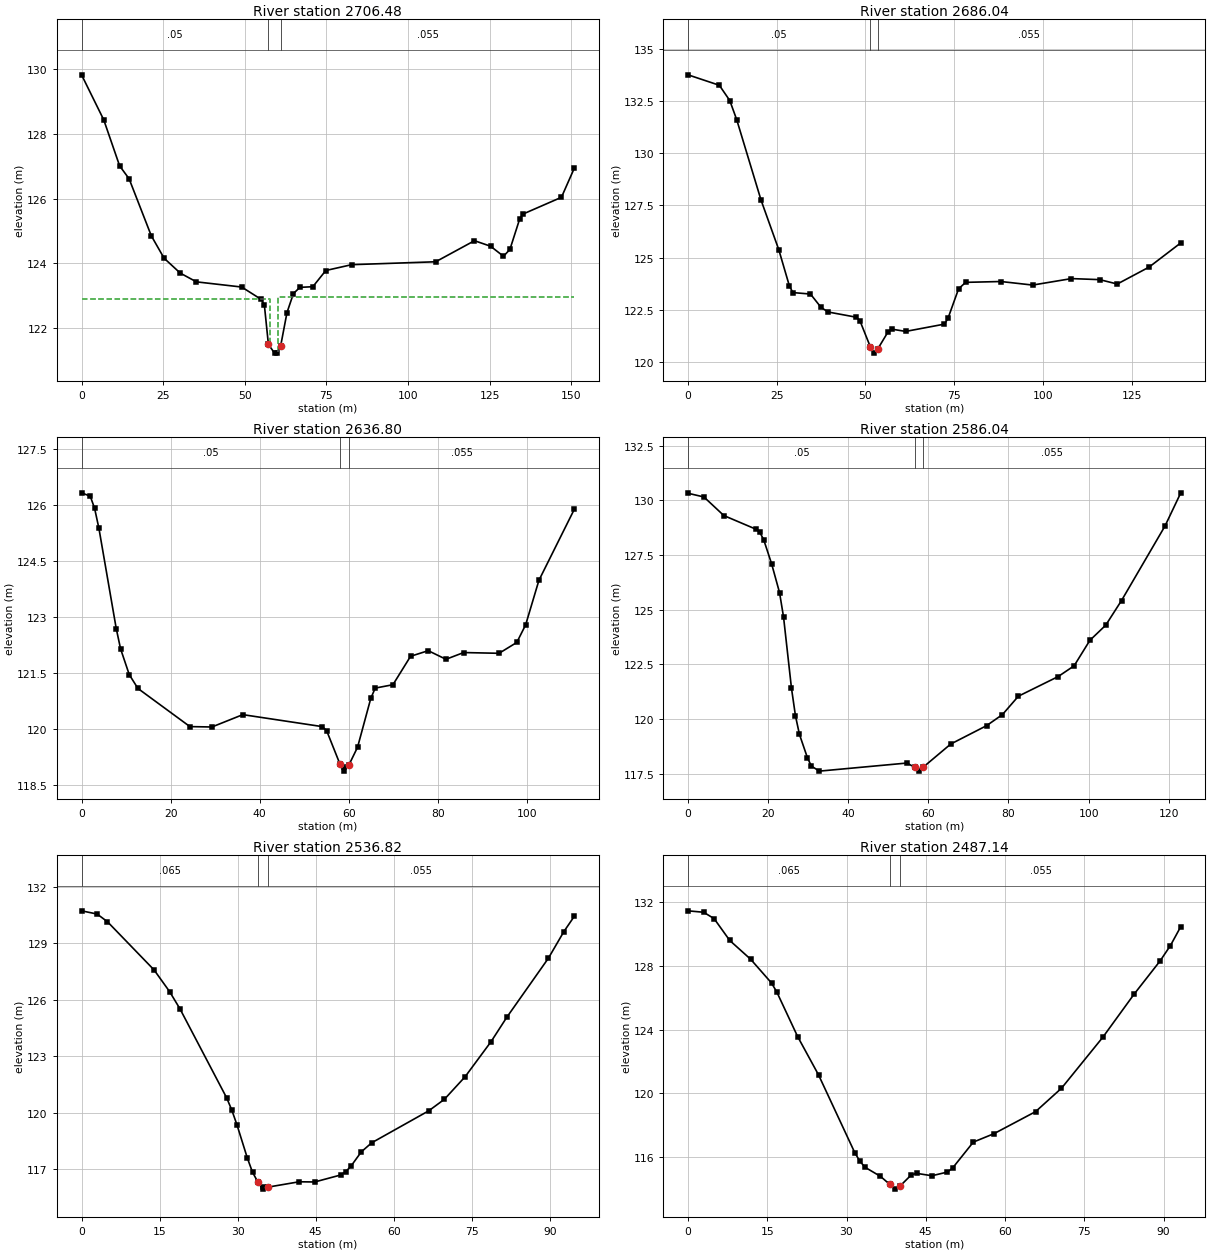
Type RM Length L Ch R = 1 ,2706.48 ,25.82,20.44,24.95
XS GIS Cut Line= 4
340176.1707153325422933.51727295340191.9425048835422915.04608154
340275.7636718755422879.28747559 340301.873107915422855.21130371
#Sta/Elev= 30
       0  129.82     6.8  128.43   11.66  127.01   14.57  126.61   21.37  124.85
   25.28  124.16   30.23   123.7   35.18  123.43   49.05  123.27      55  122.89
   55.99  122.72   57.23   121.5   59.11  121.23   59.87  121.23   60.98  121.45
   62.92  122.48    64.9  123.07   66.88  123.26   70.84  123.28   74.81  123.78
   82.73  123.96  108.48  124.05  120.35   124.7  125.28  124.53  129.23  124.22
   131.2  124.43  134.16  125.36  135.15  125.52  146.99  126.04  150.93  126.94
#Mann= 3 , 0 , 0
       0     .05       0   57.23     .04       0   60.98    .055       0
#XS Ineff= 2 , 0
       0   57.71   122.9   60.12       0  122.95
Permanent Ineff=
       F       F
Bank Sta=57.23,60.98
XS Rating Curve= 0 ,0
Exp/Cntr=0.5,0.3

Type RM Length L Ch R = 1 ,2686.04 ,53.06,49.24,39.42
XS GIS Cut Line= 3
 340194.697326665422947.84069824340209.2700805665422934.73907471
  340309.80468755422870.63409424
#Sta/Elev= 30
       0  133.75    8.82  133.25   11.76  132.52   13.72   131.6   20.59  127.74
   25.56  125.38   28.54  123.65   29.53  123.32    34.5  123.25   37.48  122.61
   39.47  122.39   47.42  122.14   48.41  121.98   51.39  120.71   52.39  120.42
   53.39   120.6   56.36  121.44   57.35  121.57   61.33  121.46   72.26  121.81
   73.25  122.09   76.23   123.5   78.22  123.81   88.16  123.85    97.1  123.68
  108.03  123.99  115.98  123.94  120.94  123.73  129.89  124.54  138.83   125.7
#Mann= 3 , 0 , 0
       0     .05       0   51.39     .04       0   53.39    .055       0
Bank Sta=51.39,53.39
XS Rating Curve= 0 ,0
Exp/Cntr=0.3,0.1

Type RM Length L Ch R = 1 ,2636.80 ,36.51,50.76,54.8
XS GIS Cut Line= 4
340237.9028930665422972.42828369340262.6873168955422963.65447998
 340287.704895025422919.71350098340318.1688842775422905.08270264
#Sta/Elev= 30
       0  126.32    1.95  126.23    2.92  125.91     3.9  125.37    7.79  122.69
    8.76  122.15   10.71  121.46   12.66  121.09   24.34  120.07   29.27  120.06
   36.21  120.39   54.05  120.07   55.04  119.96   58.02  119.07   59.01  118.88
   59.02  118.98   60.02  119.04   61.98  119.52   64.96  120.83   65.95   121.1
   69.92  121.19   73.88  121.95   77.85   122.1   81.83  121.87    85.8  122.05
   93.75  122.03   97.73  122.32   99.72  122.79   102.7  123.98  110.65  125.88
#Mann= 3 , 0 , 0
       0     .05       0   58.02     .04       0   60.02    .055       0
Bank Sta=58.02,60.02
XS Rating Curve= 0 ,0
Exp/Cntr=0.3,0.1

Type RM Length L Ch R = 1 ,2586.04 ,35.46,49.22,44.21
XS GIS Cut Line= 3
340251.1276855475423012.77752686 340329.462707525422956.62487793
340355.900878906 5422953.4440918
#Sta/Elev= 30
       0  130.33    3.97  130.16    8.94  129.31   16.89  128.69   17.89  128.55
   18.88  128.21   20.87   127.1   22.85  125.78   23.85  124.66   25.83   121.4
   26.83  120.13   27.82  119.29   29.81  118.22    30.8  117.84   32.79  117.61
   54.65  117.98   56.64  117.78   57.56  117.62   58.64  117.78   65.58  118.85
   74.52  119.69    78.5   120.2   82.47  121.04   92.41  121.94   96.38  122.43
  100.33   123.6  104.27  124.29  108.22  125.42  119.07  128.83  123.01  130.35
#Mann= 3 , 0 , 0
       0     .05       0   56.64     .04       0   58.64    .055       0
Bank Sta=56.64,58.64
XS Rating Curve= 0 ,0
Exp/Cntr=0.3,0.1

Type RM Length L Ch R = 1 ,2536.82 ,44.82,49.68,52.88
XS GIS Cut Line= 3
340256.894104004 5423031.6060791340315.472900391 5423012.1519165
340348.4030761725423010.62408447
#Sta/Elev= 30
       0  130.73    2.99  130.56    4.98  130.15   13.94  127.59   16.92  126.44
   18.92  125.52   27.88   120.8   28.87  120.15   29.87  119.36   31.86   117.6
   32.85  116.85   33.89  116.32   34.84  115.95   34.89  116.05   35.89  116.06
   41.81  116.34    44.8  116.33   49.78   116.7   50.77  116.88   51.77  117.17
   53.76  117.93   55.75  118.41   66.72  120.11   69.72  120.72   73.71  121.92
   78.71  123.79    81.7  125.07    89.7  128.21   92.69  129.63   94.69  130.44
#Mann= 3 , 0 , 0
       0    .065       0   33.89     .04       0   35.89    .055       0
Bank Sta=33.89,35.89
XS Rating Curve= 0 ,0
Exp/Cntr=0.3,0.1

Type RM Length L Ch R = 1 ,2487.14 ,51.11,49.61,46.45
XS GIS Cut Line= 4
340258.9425048835423063.43048096340286.6007080085423063.98150635
 340308.449096685423068.94232178340351.312927246 5423063.5557251
#Sta/Elev= 30
       0  131.46    2.96  131.37    4.94  130.97     7.9   129.6   11.86  128.42
   15.81  126.93    16.8  126.37   20.75  123.57    24.7  121.17   31.56  116.29
   32.53  115.75   33.51  115.37   36.43   114.8   38.18   114.3   39.18     114
   40.18  114.21   42.28   114.9   43.25  114.99   46.17  114.84   49.09  115.07
   50.07  115.32      54  116.95   57.92  117.48   65.78  118.86   70.69  120.33
   78.54  123.54   84.43  126.23   89.34  128.31   91.31  129.28   93.27  130.47
#Mann= 3 , 0 , 0
       0    .065       0   38.18     .04       0   40.18    .055       0
Bank Sta=38.18,40.18
XS Rating Curve= 0 ,0
Exp/Cntr=0.3,0.1

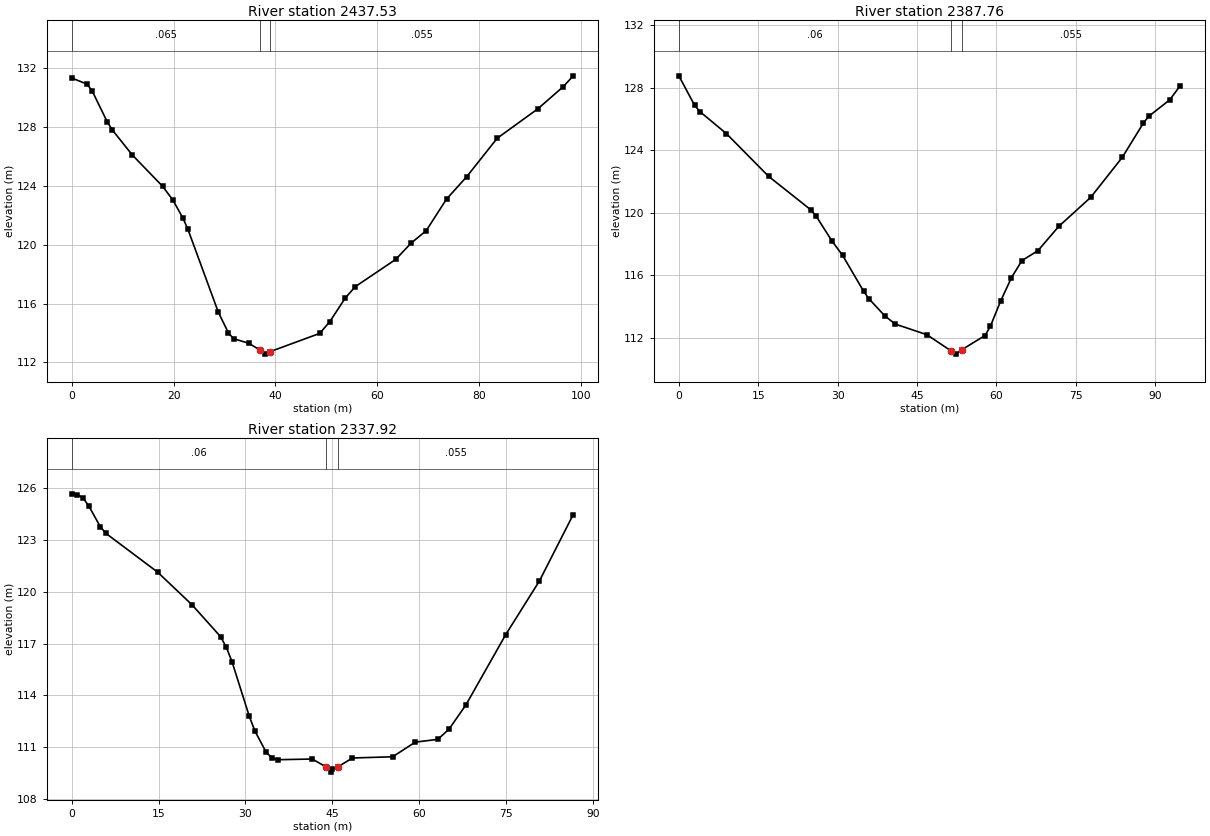
Type RM Length L Ch R = 1 ,2437.53 ,45.79,49.77,51.85
XS GIS Cut Line= 3
340259.7106933595423111.78088379340280.8557128915423117.17089844
340357.0626831055423108.80230713
#Sta/Elev= 30
       0  131.35    2.98  130.94    3.97   130.5    6.94  128.39    7.94  127.83
    11.9  126.11   17.85  123.98   19.84  123.06   21.82  121.83   22.82  121.05
   28.79  115.41   30.78     114   31.78  113.61   34.76   113.3   36.96  112.84
   37.96  112.56   38.96  112.73    48.7  113.97    50.7  114.78   53.68  116.36
   55.67  117.15   63.64  119.01   66.63  120.11   69.61  120.96    73.6  123.11
   77.58  124.64   83.55  127.25   91.52  129.25   96.49  130.75   98.49   131.5
#Mann= 3 , 0 , 0
       0    .065       0   36.96     .04       0   38.96    .055       0
Bank Sta=36.96,38.96
XS Rating Curve= 0 ,0
Exp/Cntr=0.3,0.1

Type RM Length L Ch R = 1 ,2387.76 ,44.11,49.83,53.01
XS GIS Cut Line= 2
340252.7562866215423146.42791748340342.1613159185423177.77490234
#Sta/Elev= 30
       0  128.75    2.99  126.86    3.99  126.46    8.98  125.06   16.95  122.33
   24.93  120.19   25.93  119.79   28.92   118.2   30.92  117.29    34.9  114.99
    35.9  114.51   38.89  113.42   40.89  112.89   46.87  112.21   51.41  111.18
   52.41  110.97   53.41  111.24   57.84  112.16   58.84  112.74   60.83  114.39
   62.83  115.85   64.82  116.95   67.81  117.57    71.8  119.14   77.79  120.98
   83.77  123.54   87.76  125.73   88.76  126.16   92.75  127.22   94.74  128.13
#Mann= 3 , 0 , 0
       0     .06       0   51.41     .04       0   53.41    .055       0
Bank Sta=51.41,53.41
XS Rating Curve= 0 ,0
Exp/Cntr=0.3,0.1

Type RM Length L Ch R = 1 ,2337.92 ,52.32,49.73,33.34
XS GIS Cut Line= 4
340244.5170898445423193.01928711 340279.310485845423200.47088623
340292.0844726565423215.66888428 340323.136718755423218.69268799
#Sta/Elev= 30
       0  125.69     .99  125.65    1.98  125.44    2.97  124.97    4.94  123.78
    5.93  123.39   14.83  121.15   20.76  119.26    25.7  117.41   26.69   116.8
   27.68  115.96   30.64  112.82   31.63  111.94   33.61  110.69   34.59  110.38
   35.58  110.27   41.54  110.31      44  109.84    44.8  109.55      45  109.73
      46  109.86   48.49  110.37   55.44  110.44   59.34  111.29   63.24  111.45
   65.19  112.05   68.11  113.46   74.94  117.51   80.79  120.64   86.63  124.49
#Mann= 3 , 0 , 0
       0     .06       0      44     .04       0      46    .055       0
Bank Sta=44,46
XS Rating Curve= 0 ,0
Exp/Cntr=0.3,0.1