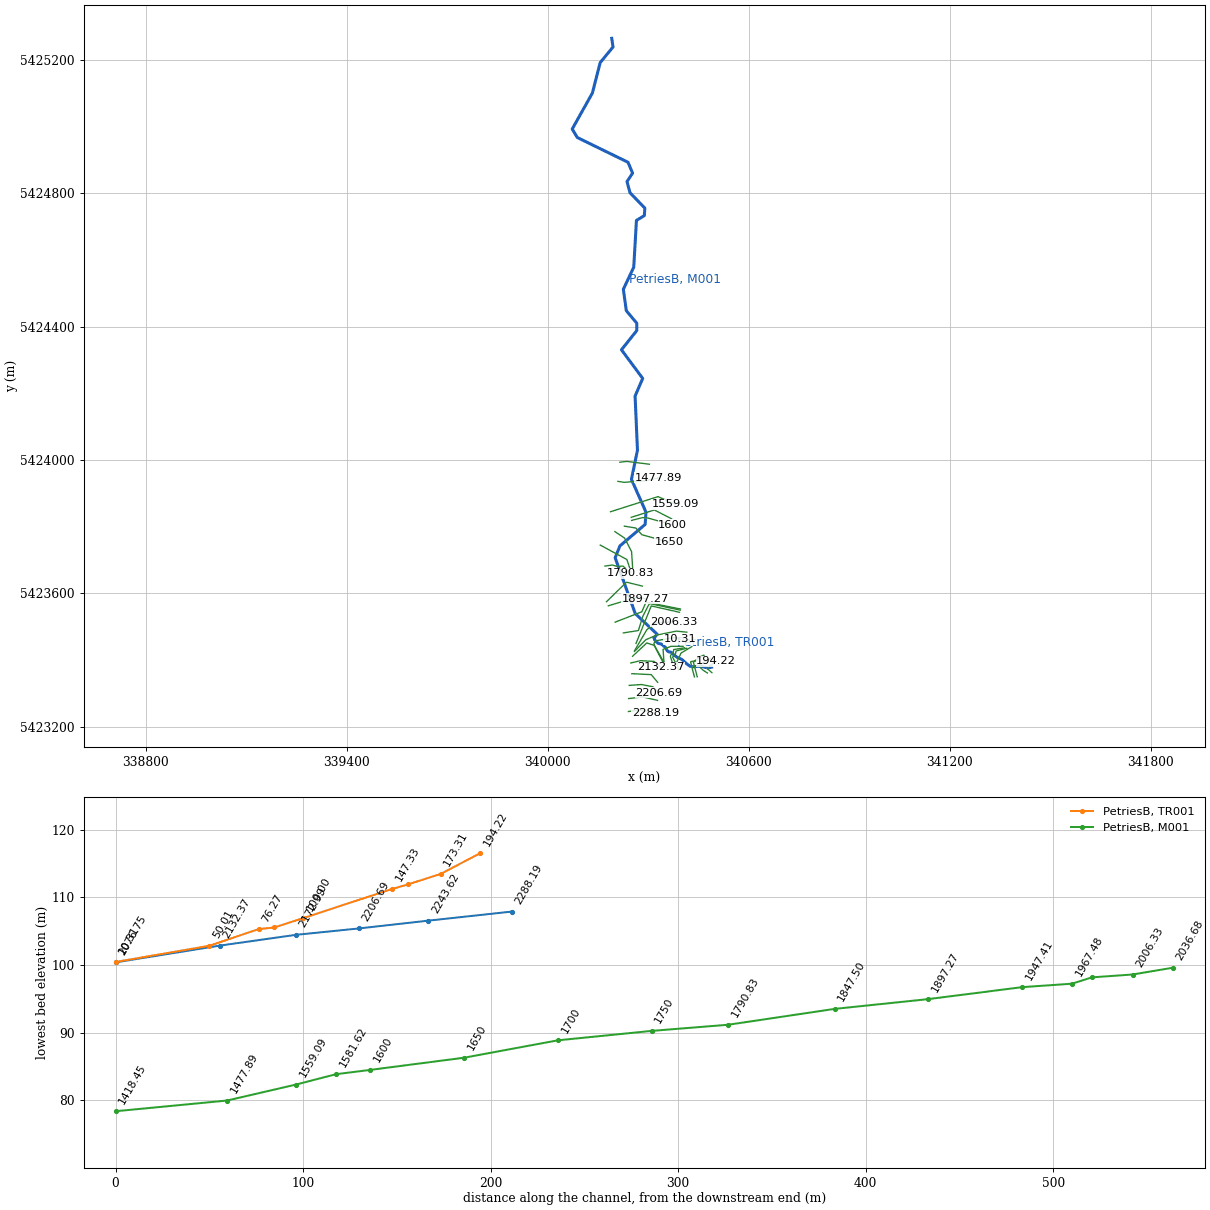
HEC-RAS study PetriesBrk_v001.prj: Petries_Brook

--- PetriesBrk_v001.g01 (geometry) --- (continued)

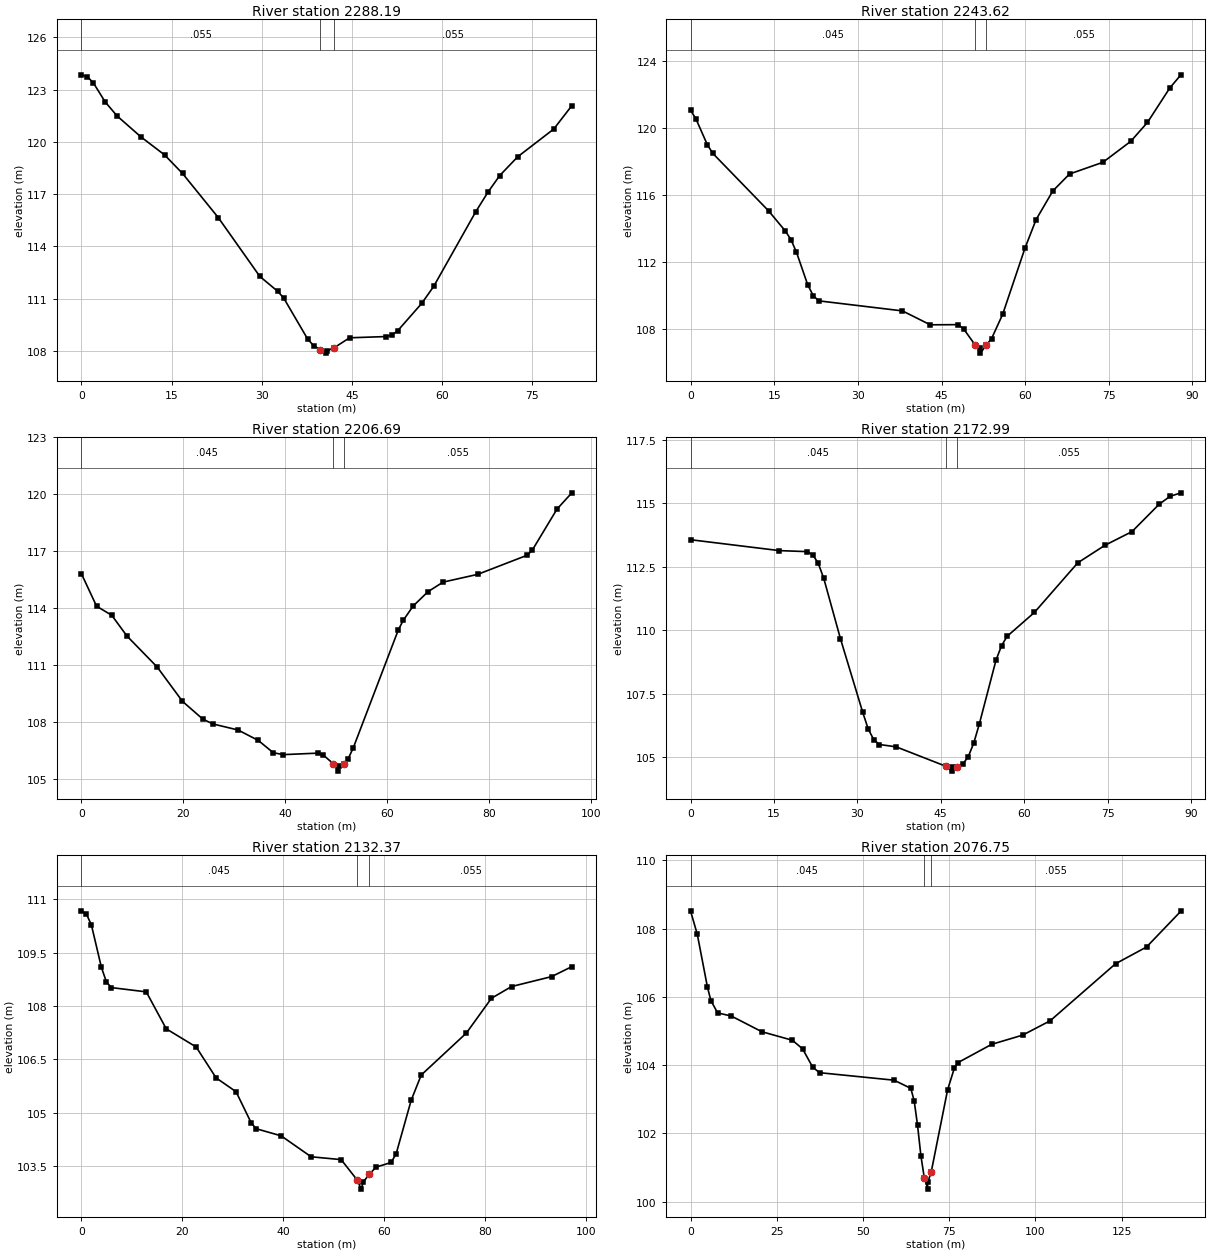
Type RM Length L Ch R = 1 ,2288.19 ,39.4,44.58,41.7
XS GIS Cut Line= 3
340241.3510742195423245.69189453340276.5734863285423250.86907959
340321.2490844735423240.12652588
#Sta/Elev= 30
       0  123.85     .99  123.74    1.98  123.39    3.96  122.29    5.93  121.49
    9.89  120.29   13.84  119.25   16.81  118.19   22.75  115.66   29.67  112.28
   32.63  111.43   33.62  111.05    37.6   108.7    38.6  108.31   39.72  108.08
    40.6  107.88    40.9  108.02   42.08   108.2   44.59  108.76   50.58  108.83
   51.58  108.91   52.58  109.16   56.58  110.73   58.58  111.71   65.57  115.99
   67.57   117.1   69.56  118.07   72.56  119.15   78.55  120.74   81.55  122.08
#Mann= 3 , 0 , 0
       0    .055       0   39.72     .04       0   42.08    .055       0
Bank Sta=39.72,42.08
XS Rating Curve= 0 ,0
Exp/Cntr=0.3,0.1

Type RM Length L Ch R = 1 ,2243.62 ,37.36,36.93,37.07
XS GIS Cut Line= 3
340241.8336791995423284.53668213340283.5184936525423289.63049316
340328.2086791995423279.05108643
#Sta/Elev= 30
       0  121.05       1   120.5       3  118.99       4  118.46      14  115.03
      17  113.83      18  113.32      19  112.56      21  110.63      22  109.97
      23  109.66      38  109.06   42.99  108.23   47.99  108.24   48.98  107.98
   50.98  107.05   51.98  106.84   51.98  106.54   52.98     107   53.98  107.41
   55.97  108.86   59.97  112.81   61.96  114.51   64.96  116.22   67.95  117.23
   73.94  117.93   78.93  119.18   81.93  120.31   85.92  122.36   87.92  123.15
#Mann= 3 , 0 , 0
       0    .045       0   50.98     .04       0   52.98    .055       0
Bank Sta=50.98,52.98
XS Rating Curve= 0 ,0
Exp/Cntr=0.3,0.1

Type RM Length L Ch R = 1 ,2206.69 ,32.31,33.7,34.06
XS GIS Cut Line= 4
340243.6629028325423324.02972412340280.2351074225423326.60388184
 340313.888488775423320.08251953340331.9172973635423302.40612793
#Sta/Elev= 30
       0   115.8    2.97  114.09    5.95  113.61    8.92  112.52   14.86  110.88
   19.82  109.07   23.78  108.14   25.76  107.88   30.72  107.56   34.68  107.01
   37.64  106.36    39.6  106.26   46.46  106.34   47.44  106.24    49.4  105.78
   50.37  105.39   50.44  105.65   51.57  105.79   52.33  106.05   53.31  106.61
   62.13  112.82   63.11  113.34   65.07   114.1      68  114.86   70.94  115.36
   77.74  115.77   87.45  116.78   88.42  117.04   93.28  119.21   96.19  120.07
#Mann= 3 , 0 , 0
       0    .045       0    49.4     .04       0   51.57    .055       0
Bank Sta=49.4,51.57
XS Rating Curve= 0 ,0
Exp/Cntr=0.3,0.1

Type RM Length L Ch R = 1 ,2172.99 ,40.44,40.61,40.84
XS GIS Cut Line= 3
340251.432495117 5423359.1348877340309.3024902345423356.36407471
340328.708129883 5423333.1585083
#Sta/Elev= 30
       0  113.57   15.98  113.14   20.98   113.1   21.98  112.98   22.97  112.64
   23.97  112.04   26.97  109.66   30.97  106.76   31.96   106.1   32.96  105.68
   33.96  105.49   36.96   105.4   45.95  104.63   46.95  104.44   46.97  104.59
   47.98  104.59   48.95  104.71   49.95  105.01   50.94  105.55   51.94   106.3
   54.94  108.82   55.94  109.39   56.94  109.76   61.84   110.7   69.65  112.66
   74.53  113.35    79.4  113.89   84.28  114.97   86.23  115.28   88.19  115.42
#Mann= 3 , 0 , 0
       0    .045       0   45.95     .04       0   47.98    .055       0
Bank Sta=45.95,47.98
XS Rating Curve= 0 ,0
Exp/Cntr=0.3,0.1

Type RM Length L Ch R = 1 ,2132.37 ,53.97,55.62,51.54
XS GIS Cut Line= 4
 340248.427673345423391.20751953340277.2858886725423398.14227295
340317.912475586  5423395.965271340338.1419067385423378.24328613
#Sta/Elev= 30
       0  110.68     .99  110.59    1.98  110.28    3.96  109.09    4.95  108.68
    5.94  108.52   12.86   108.4   16.82  107.36   22.75  106.85   26.71  105.98
   30.67  105.59   33.65  104.72   34.64  104.55    39.6  104.35   45.56  103.76
   51.51  103.68   54.73   103.1   55.48  102.85   55.91  103.05   57.09  103.27
   58.46  103.47   61.43   103.6   62.43  103.85    65.4  105.35   67.39  106.06
   76.34  107.24   81.32  108.22   85.31  108.55   93.27  108.83   97.26  109.11
#Mann= 3 , 0 , 0
       0    .045       0   54.73     .04       0   57.09    .055       0
Bank Sta=54.73,57.09
XS Rating Curve= 0 ,0
Exp/Cntr=0.3,0.1

Type RM Length L Ch R = 1 ,2076.75 ,13.38,48.96,52.85
XS GIS Cut Line= 4
340253.7935180665423411.42712402340295.9760742195423451.33007813
340318.0718994145423444.05212402340346.1937255865423390.09552002
#Sta/Elev= 30
       0  108.52    1.97  107.83    4.92  106.28    5.91  105.89    7.87  105.53
   11.81  105.44   20.67  104.98   29.52  104.73   32.48  104.48   35.43  103.94
    37.4  103.78   59.03  103.56   63.88  103.32   64.85  102.95   65.82  102.24
   66.79  101.35   67.76  100.71   68.11  100.66   68.73  100.37   68.76  100.57
   69.76  100.86   74.54  103.28   76.48  103.91   77.45  104.07   87.31  104.61
   96.29  104.88  104.27   105.3  123.22  106.97   132.2  107.46  142.17  108.51
#Mann= 3 , 0 , 0
       0    .045       0   67.76     .04       0   69.76    .055       0
Bank Sta=67.76,69.76
XS Rating Curve= 0 ,0
Exp/Cntr=0.3,0.1

River Reach=PetriesB        ,TR001
Reach XY= 28
340489.6113281255423378.60467529340479.4594726565423376.82910156
340472.1840820315423377.75909424340460.7633056645423380.88769531
340446.5507202155423381.14129639340436.2296752935423379.70391846
340425.2734985355423381.53692627340418.2517089845423386.44128418
340410.6378784185423392.86749268340401.4166870125423401.40771484
340394.6486816415423404.78991699340386.1043090825423408.84851074
340376.8831176765423415.10571289340372.5684814455423419.75628662
340369.2691040045423423.47668457340362.4166870125423424.40692139
340358.1868896485423426.68988037340355.4796752935423430.66412354
340353.3255004885423436.21252441340350.110900879 5423439.5100708
340345.9655151375423442.21588135340344.1043090825423445.17529297
340338.9439086915423447.96569824340330.3992919925423450.16430664
340325.7465209965423453.37731934340322.7855224615423457.01330566
340319.1477050785423460.90289307 340318.699096685423466.61431885

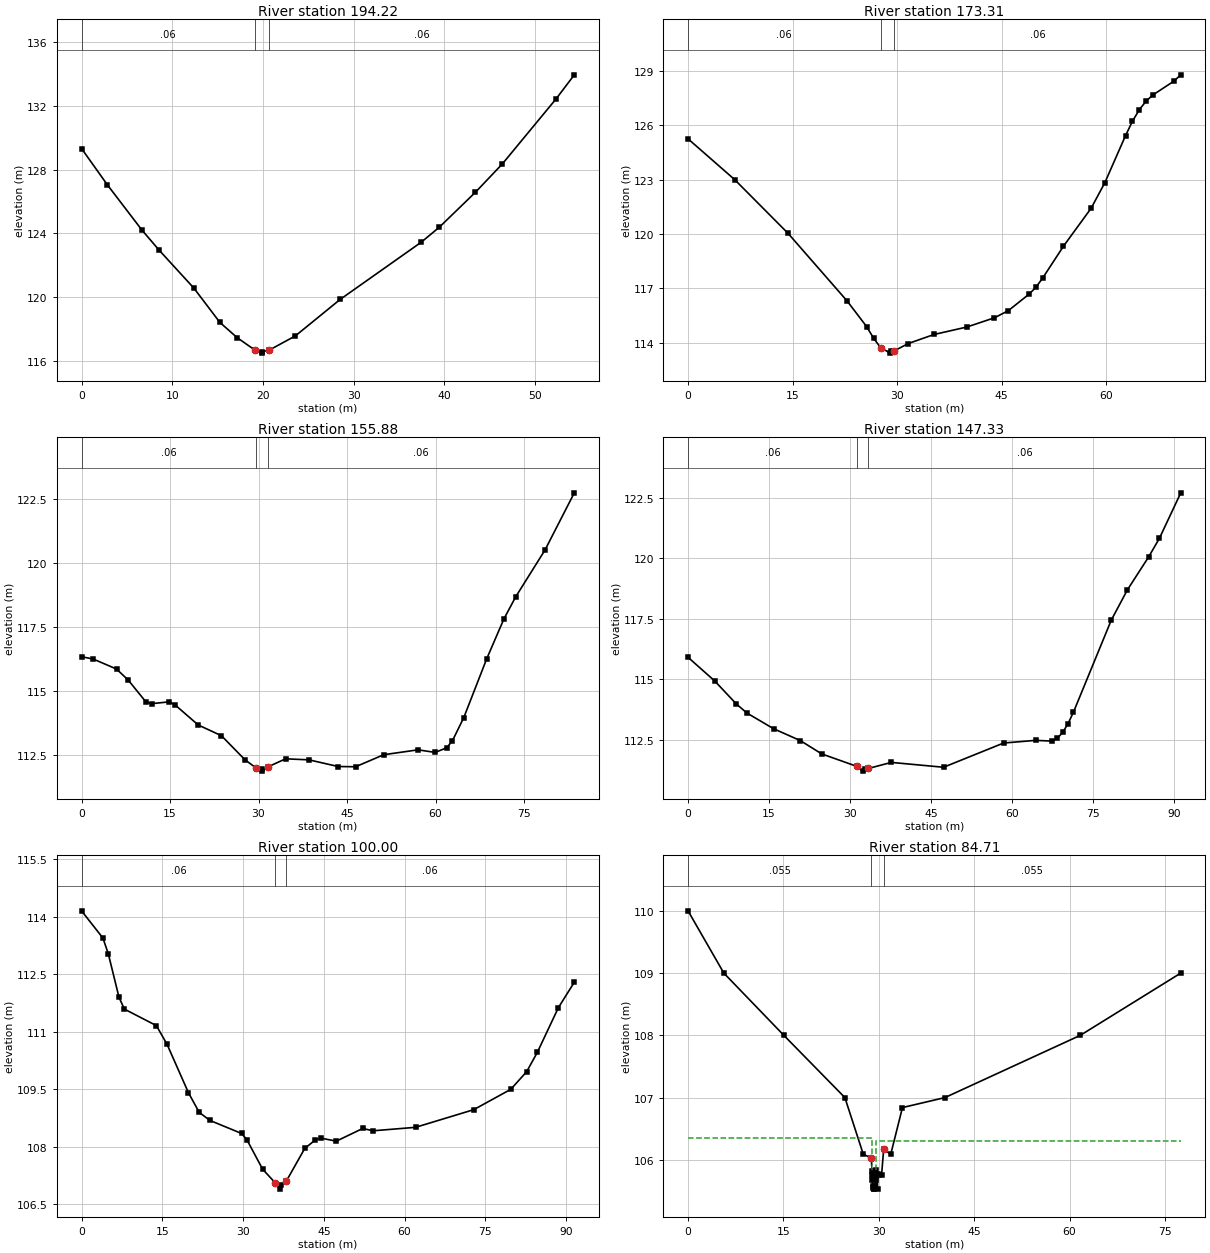
Type RM Length L Ch R = 1 ,194.22  ,22.47,20.91,22.73
XS GIS Cut Line= 4
 340490.552673345423362.19750977340476.1080932625423374.64129639
340476.4816894535423377.12988281340503.1295166025423396.16870117
#Sta/Elev= 19
       0  129.32    2.86  127.03    6.67  124.19    8.58  122.92   12.39  120.55
   15.25   118.4   17.16  117.44   19.07  116.68   19.87  116.47    19.9  116.57
   20.66  116.65   23.57  117.55   28.53  119.85   37.46  123.44   39.45  124.38
   43.42  126.57   46.39  128.35   52.35  132.46   54.33  133.95
#Mann= 3 , 0 , 0
       0     .06       0   19.07     .04       0   20.66     .06       0
Bank Sta=19.07,20.66
XS Rating Curve= 0 ,0
Exp/Cntr=0.3,0.1

Type RM Length L Ch R = 1 ,173.31  ,23.39,17.43,24.44
XS GIS Cut Line= 6
340477.0084838875423361.22491455340464.2337036135423369.64508057
340456.6232910165423376.61651611340455.7219238285423384.52410889
340457.2620849615423387.60247803340486.0733032235423404.98590088
#Sta/Elev= 28
       0  125.25    6.69     123   14.34  120.04   22.81  116.31   25.62  114.89
   26.62  114.25   27.61  113.74   28.99  113.43   29.06  113.53    29.6  113.56
   31.59  113.96    35.3  114.46   39.99  114.87   43.95  115.38   45.93  115.77
    48.9  116.68   49.89  117.06   50.88  117.58   53.85  119.33   57.81  121.42
   59.78  122.83   62.75  125.43   63.74  126.22   64.73  126.86   65.72  127.34
   66.71  127.68   69.68  128.43   70.67  128.78
#Mann= 3 , 0 , 0
       0     .06       0   27.61     .04       0    29.6     .06       0
Bank Sta=27.61,29.6
XS Rating Curve= 0 ,0
Exp/Cntr=0.3,0.1

Type RM Length L Ch R = 1 ,155.88  ,8.24,8.54,1.69
XS GIS Cut Line= 5
340446.7542724615423349.76367188340434.9246826175423394.68530273
340439.532104492 5423395.9296875340455.5407104495423408.51690674
340466.5941162115423413.04370117
#Sta/Elev= 30
       0  116.35    1.98  116.26    5.93  115.87    7.91  115.44   10.87   114.6
   11.86  114.52   14.83  114.59   15.81  114.48   19.77  113.69   23.72  113.27
   27.67  112.34   29.65     112   30.64  111.99   30.64  111.89   31.63  112.06
   34.59  112.37   38.55  112.33   43.49  112.07   46.45  112.06   51.23  112.53
   57.04  112.72   59.95  112.62   61.89   112.8   62.86  113.07    64.8  113.98
   68.68  116.27   71.59  117.82   73.58  118.68   78.56  120.51   83.53  122.74
#Mann= 3 , 0 , 0
       0     .06       0   29.65     .04       0   31.63     .06       0
Bank Sta=29.65,31.63
XS Rating Curve= 0 ,0
Exp/Cntr=0.3,0.1

Type RM Length L Ch R = 1 ,147.33  ,54.28,47.35,44.95
XS GIS Cut Line= 6
340438.2866821295423349.39050293340427.3289184575423392.56988525
340427.3289184575423395.30749512340439.1585083015423397.54748535
340454.9064941415423409.87487793 340465.86932373 5423414.4019165
#Sta/Elev= 25
       0  115.91    4.95  114.93    8.91  113.99   10.89  113.61   15.84  112.96
   20.79  112.47   24.75  111.92    31.2  111.41   32.29  111.21   32.67  111.31
   33.38  111.32   37.62  111.57   47.29  111.37    58.4  112.37   64.33  112.48
   67.33  112.45   68.33  112.56   69.33  112.81   70.33  113.17   71.32  113.64
   78.32  117.44    81.3  118.69   85.26  120.06   87.23  120.82   91.19   122.7
#Mann= 3 , 0 , 0
       0     .06       0    31.2     .04       0   33.38     .06       0
Bank Sta=31.2,33.38
XS Rating Curve= 0 ,0
Exp/Cntr=0.3,0.1

Type RM Length L Ch R = 1 ,100.00  ,12.44,15.29,12.54
XS GIS Cut Line= 4
340390.3770751955423370.14007568 340385.867309575423394.55627441
340398.457519531 5423421.0612793340430.515686035 5423440.2388916
#Sta/Elev= 30
       0  114.15    3.97  113.44    4.97  113.03    6.95   111.9    7.95  111.59
    13.9  111.16   15.89  110.67   19.86  109.41   21.85   108.9   23.84  108.69
   29.72  108.35    30.7  108.19   33.63  107.42      36  107.06   36.84   106.9
      37     107      38   107.1   41.46  107.96   43.41  108.18   44.39  108.23
   47.33  108.15   52.22  108.48   54.17  108.42   62.04  108.51   72.85  108.97
   79.73   109.5   82.68  109.96   84.65  110.46   88.58  111.63   91.53  112.29
#Mann= 3 , 0 , 0
       0     .06       0      36     .04       0      38     .06       0
Bank Sta=36,38
XS Rating Curve= 0 ,0
Exp/Cntr=0.3,0.1

Type RM Length L Ch R = 1 ,84.71   ,9.39,8.44,15.09
XS GIS Cut Line= 5
      340383.842     5423388.527      340373.204     5423408.496
      340381.381     5423417.416      340383.834     5423427.376
      340415.382     5423435.224
#Sta/Elev= 27
       0     110    5.63     109   15.07     108   24.67     107   27.56  106.09
   28.83  106.03   28.93  105.82   28.94  105.75   28.97  105.67   29.05  105.58
   29.12  105.55   29.23  105.53   29.31  105.54   29.41  105.58   29.49  105.67
   29.52  105.74   29.53  105.83    29.8  105.53   29.81  105.77      30  105.75
   30.44  105.76   30.77  106.17   31.88  106.09   33.72  106.84   40.39     107
   61.69     108   77.49     109
#Mann= 3 , 0 , 0
       0    .055       0   28.83     .04       0   30.77    .055       0
#XS Ineff= 2 , 0
       0   28.93  106.35   29.53       0  106.31
Permanent Ineff=
       F       F
Bank Sta=28.83,30.77
XS Rating Curve= 0 ,0
Exp/Cntr=0.5,0.3

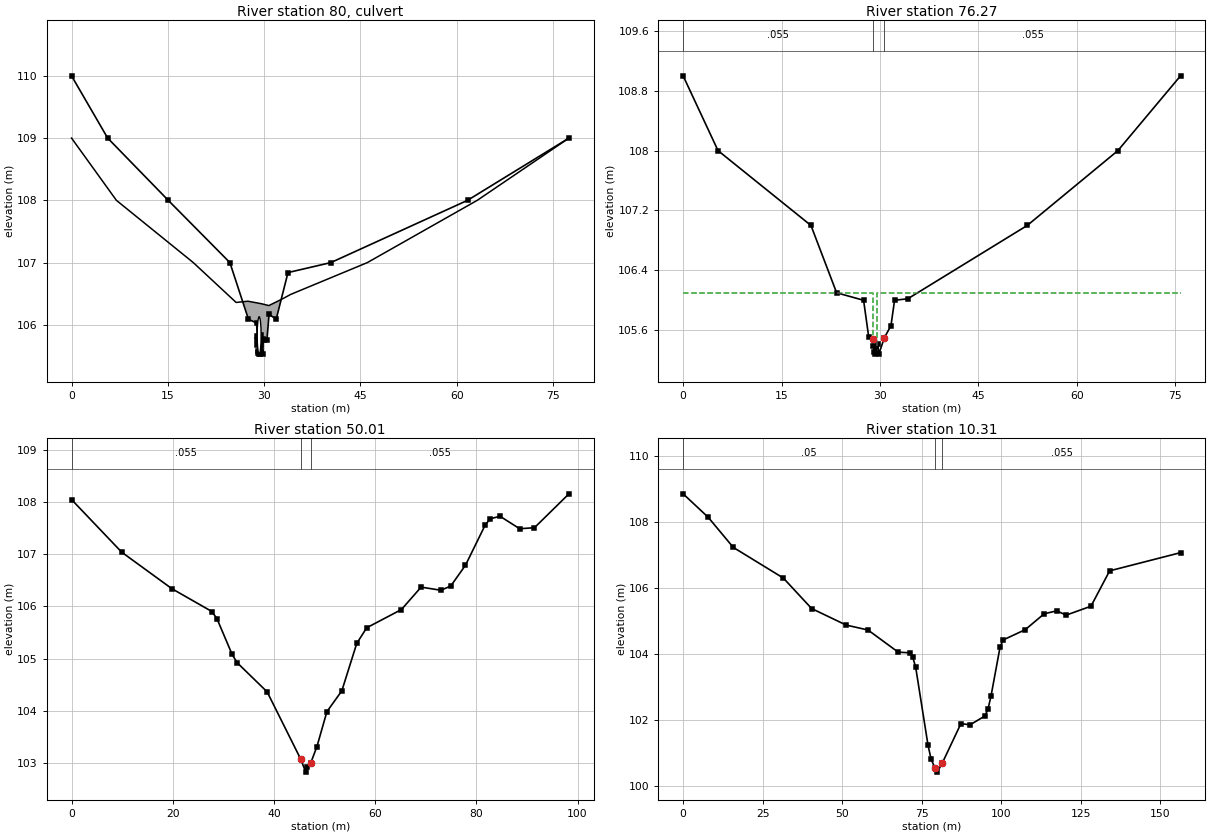
Type RM Length L Ch R = 2 ,80      ,,,
BEGIN DESCRIPTION:
ATV Trail (1109-B)
END DESCRIPTION:
Bridge Culvert--1,0,-1,-1, 0
Deck Dist Width WeirC Skew NumUp NumDn MinLoCord MaxHiCord MaxSubmerge Is_Ogee
2.85,3.1,1.64,0, 12, 12, 106, , 0.98, 0, 1,1,,
       0    6.99   18.97   25.64   27.48   29.56   30.74    32.9   34.16   46.08
    63.2   77.49
     109     108     107  106.36  106.38  106.34  106.31  106.42  106.49     107
     108     109
                                                                                
                
       0    6.99   18.97   25.64   27.48   29.56   30.74    32.9   34.16   46.08
    63.2    75.8
     109     108     107  106.36  106.38  106.34  106.31  106.42  106.49     107
     108     109
                                                                                
                
BR Coef=-1 , 0 , 0 ,, 0 ,,,0.8,-1,,0,
WSPro=,,,, 1 ,,,, 0 ,,,, 0 ,,,,-1 ,-1 ,-1 , 0 , 0 , 0 , 0 , 0
Culvert=1,0.6,,3.7,0.033,0.9,1,2,3,105.53,29.23,105.28,29.25,Culvert #1  , 0 ,2.64
Culvert Bottom n=0.033
BC Design=,, 0 ,, 0 ,,,,,,
BC Use User HTab Curves=0
BC User HTab FreeFlow(D)= 0

Type RM Length L Ch R = 1 ,76.27   ,28.25,26.27,17.7
XS GIS Cut Line= 6
      340372.308     5423392.562      340366.603     5423410.942
      340367.984     5423415.397      340375.233     5423423.031
      340376.448     5423431.529      340408.799      5423436.79
#Sta/Elev= 21
       0     109    5.32     108   19.48     107   23.39   106.1    27.5     106
   28.28  105.51   28.96  105.48   29.01  105.39    29.1  105.31   29.25  105.28
   29.36   105.3   29.46  105.37   29.66  105.42   29.82  105.28   30.67   105.5
   31.67  105.66   32.22     106   34.24  106.02   52.44     107   66.25     108
    75.8     109
#Mann= 3 , 0 , 0
       0    .055       0   28.96     .04       0   30.67    .055       0
#XS Ineff= 2 , 0
       0   28.95   106.1   29.55       0   106.1
Permanent Ineff=
       F       F
Bank Sta=28.96,30.67
XS Rating Curve= 0 ,0
Exp/Cntr=0.5,0.3

Type RM Length L Ch R = 1 ,50.01   ,38.76,50,44.4
XS GIS Cut Line= 4
340347.3402709965423395.34088135340344.6934814455423431.93768311
340368.5418701175423441.19671631340404.5776977545423441.10791016
#Sta/Elev= 28
       0  108.05    9.92  107.04   19.83  106.34   27.77   105.9   28.76  105.76
   31.73  105.08   32.73  104.92   38.66  104.36   45.29  103.07   46.29  102.82
   46.53  102.92   47.29     103    48.5  103.31   50.47  103.98   53.42  104.38
   56.37  105.29   58.34  105.59    65.2  105.94   69.09  106.37   72.99  106.31
   74.94  106.39   77.86  106.79   81.75  107.56   82.73  107.68   84.68  107.73
   88.57  107.49   91.49  107.51   98.31  108.16
#Mann= 3 , 0 , 0
       0    .055       0   45.29     .04       0   47.29    .055       0
Bank Sta=45.29,47.29
XS Rating Curve= 0 ,0
Exp/Cntr=0.3,0.1

Type RM Length L Ch R = 1 ,10.31   ,4.87,10.31,6.91
XS GIS Cut Line= 6
       340349.36      5423389.58340319.2850952155423443.17669678
340317.4757080085423450.09008789340321.9459228525423457.53527832
340378.143127441 5423467.5333252340395.9174804695423462.85351563
#Sta/Elev= 30
       0  108.85    7.88  108.14   15.75  107.23   31.51   106.3   40.37  105.38
    51.2  104.88   58.09  104.73   67.58  104.06   71.15  104.04   72.11  103.92
   73.08   103.6   76.94  101.25    77.9  100.83   79.06  100.57   79.83  100.43
   81.46  100.71    87.3   101.9   90.13  101.86   94.85  102.13    95.8  102.34
   96.74  102.73   99.58  104.21  100.57  104.43   107.5  104.74  113.44  105.22
   117.4  105.31  120.36  105.18  128.16  105.45  134.02  106.52   156.3  107.07
#Mann= 3 , 0 , 0
       0     .05       0   79.06     .04       0   81.46    .055       0
Bank Sta=79.06,81.46
XS Rating Curve= 0 ,0
Exp/Cntr=0.3,0.1

River Reach=PetriesB        ,M001
Reach XY= 30
 340318.699096685423466.61431885340327.0817260745423477.45751953
 340261.572326665423539.54547119340201.7526855475423706.82910156
340215.9166870125423742.26867676340291.2197265635423806.68890381
340293.7192993165423843.57647705340250.2764892585423941.80169678
340268.2886962895424029.25750732340261.2006835945424191.74511719
340283.9938964845424244.48669434340220.5006713875424330.30328369
340266.2257080085424388.01507568340266.3269042975424410.11810303
340235.0463256845424447.39868164340226.1043090825424511.75408936
340257.1984863285424578.05767822340265.236083984 5424718.2244873
340288.7479248055424732.67388916340290.3640747075424755.07208252
340245.9536743165424801.39727783340237.0942993165424834.77008057
 340253.689514165424860.10772705340240.0817260745424892.66027832
340088.7185058595424966.90032959340073.5012817385424992.30133057
340133.6962890635425100.14788818      340156.939    5425191.4388
     340195.3346    5425238.3823     340191.4736     5425264.319

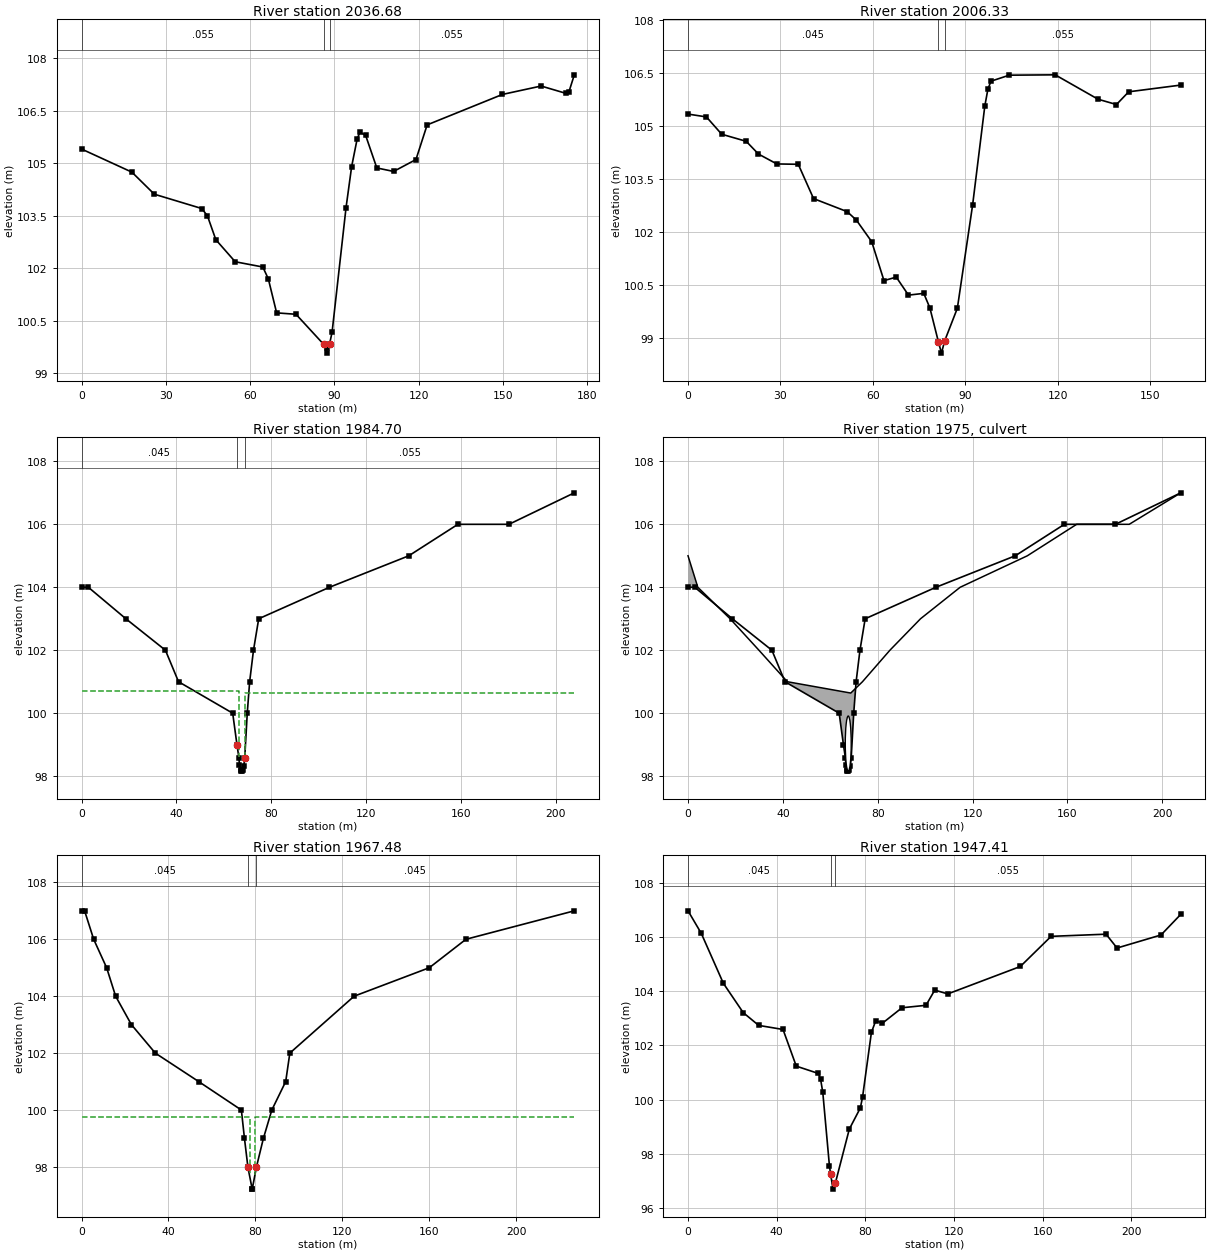
Type RM Length L Ch R = 1 ,2036.68 ,19.14,21.47,22.09
XS GIS Cut Line= 5
340259.3917236335423425.86730957340293.2619018555423460.98327637
340324.8032836915423474.73352051340384.2877197275423486.79150391
340415.6174926765423483.61828613
#Sta/Elev= 30
       0  105.41   17.92  104.75   25.89  104.12   42.81  103.71   44.81   103.5
   47.79  102.82   54.69  102.19   64.52  102.04   66.48   101.7   69.43  100.73
   76.32  100.69   86.18   99.83   87.18   99.58   87.22   99.73   88.25   99.83
   89.17  100.18   94.14  103.74   96.13  104.91   98.12  105.71   99.12  105.89
  101.11   105.8  105.09  104.87  111.06  104.77  119.02  105.11     123   106.1
   149.8  106.97  163.57  107.21  172.43     107  173.41  107.03  175.38  107.53
#Mann= 3 , 0 , 0
       0    .055       0   86.18     .04       0   88.25    .055       0
Bank Sta=86.18,88.25
XS Rating Curve= 0 ,0
Exp/Cntr=0.3,0.1

Type RM Length L Ch R = 1 ,2006.33 ,14.03,21.62,23.76
Node Photo=..\..\..\Corner Brook\Windshield Survey\CB photos\P1000600.JPG
XS GIS Cut Line= 4
340259.8197021485423428.49249268340296.3638916025423491.13690186
340324.138305664 5423511.9006958 340376.726684575423514.89208984
#Sta/Elev= 30
       0  105.34    5.96  105.26   10.93  104.77   18.88  104.57   22.85  104.21
   28.81  103.93   35.77  103.92   40.73  102.95   51.66  102.58   54.64  102.34
   59.61  101.73   63.58  100.63   67.56  100.73   71.53  100.22   76.49  100.27
   78.47   99.86   81.24    98.9   82.24   98.58   83.24   98.92   87.39   99.85
   92.34  102.77    96.3  105.57   97.29  106.04   98.29  106.27  104.23  106.44
  119.13  106.45  133.04  105.76  139.01  105.61  142.98  105.97  159.88  106.16
#Mann= 3 , 0 , 0
       0    .045       0   81.24     .04       0   83.24    .055       0
Bank Sta=81.24,83.24
XS Rating Curve= 0 ,0
Exp/Cntr=0.3,0.1

Type RM Length L Ch R = 1 ,1984.70 ,9.69,10.7,11.75
Node Photo=..\..\..\Corner Brook\Windshield Survey\CB photos\P1000599.JPG
XS GIS Cut Line= 3
340263.9069213875423449.70489502340309.4929199225423562.27612305
340393.7614746095423543.24847412
#Sta/Elev= 24
       0     104    2.87     104   18.69     103   35.38     102    40.9     101
   63.75     100   65.55      99   66.36   98.59   66.59   98.37    67.1   98.18
   67.19   98.16   67.58   98.16   68.06   98.19   68.46   98.32   68.83   98.59
   69.89     100    70.9     101   72.52     102   74.72     103  104.56     104
  138.03     105  158.74     106  180.28     106  207.84     107
#Mann= 3 , 0 , 0
       0    .045       0   65.55     .04       0   68.83    .055       0
#XS Ineff= 2 , 0
       0   66.34   100.7   68.83       0  100.64
Permanent Ineff=
       F       F
Bank Sta=65.55,68.83
XS Rating Curve= 0 ,0
Exp/Cntr=0.5,0.3

Type RM Length L Ch R = 2 ,1975    ,,,
Node Photo=..\..\..\Corner Brook\Windshield Survey\CB photos\P1000596.JPG
BEGIN DESCRIPTION:
Georgetown Road (1106)
END DESCRIPTION:
Bridge Culvert--1,0,-1,-1, 0
Deck Dist Width WeirC Skew NumUp NumDn MinLoCord MaxHiCord MaxSubmerge Is_Ogee
1.4,8.3,1.67,0, 14, 15, 100.64, , 0.98, 0, 1,1,,
       0    4.13   17.75   29.92   41.89   68.64   73.58   85.15   98.07  114.78
  143.12  163.92   186.1  207.84
     105     104     103     102     101  100.64     101     102     103     104
     105     106     106     107
                                                                                
                                
       0    4.62    9.41   16.08   24.87   39.21   52.86    80.4   86.18   97.91
  109.28  126.14  155.92   177.1  226.72
     107     106     105     104     103     102     101  100.55     101     102
     103     104     105     106     107
                                                                                
                                        
BR Coef=-1 , 0 , 0 ,, 0 ,,,0.8,-1,,0,
WSPro=,,,, 1 ,,,, 0 ,,,, 0 ,,,,-1 ,-1 ,-1 , 0 , 0 , 0 , 0 , 0
Culvert=3,1.75,2.49,9.4,0.033,0.5,1,34,1,98.16,67.58,97.58,78.53,Culvert #1  , 0 ,1.3
Culvert Bottom n=0.033
BC Design=,, 0 ,, 0 ,,,,,,
BC Use User HTab Curves=0
BC User HTab FreeFlow(D)= 0

Type RM Length L Ch R = 1 ,1967.48 ,41.67,26.59,20.75
Node Photo=..\..\..\Corner Brook\Windshield Survey\CB photos\P1000598.JPG
XS GIS Cut Line= 6
340226.2531127935423481.39349365340271.072692871 5423488.5480957
340284.2855224615423531.17669678340301.6506958015423565.12872314
340304.6704711915423569.27850342340396.0264892585423549.66168213
#Sta/Elev= 22
       0     107     1.4     107    5.58     106   11.54     105   15.68     104
   22.94     103   33.94     102   53.89     101   73.53     100   74.96      99
   76.53      98    78.5   97.22   78.53   97.22   80.47      98   83.65      99
   87.54     100   93.93     101   95.83     102  125.41     104  159.99     105
  176.86     106  226.72     107
#Mann= 3 , 0 , 0
       0    .045       0   76.53     .04       0   80.47    .045       0
#XS Ineff= 2 , 0
       0   77.28   99.75   79.77       0   99.75
Permanent Ineff=
       F       F
Bank Sta=76.53,80.47
XS Rating Curve= 0 ,0
Exp/Cntr=0.5,0.3

Type RM Length L Ch R = 1 ,1947.41 ,49.13,50.13,48.43
XS GIS Cut Line= 4
340201.5836791995423513.65350342340281.4672851565423544.79571533
340293.7230834965423573.80529785340396.7816772465423553.05688477
#Sta/Elev= 30
       0  106.96    5.98  106.13   15.95  104.29   24.92  103.21    31.9  102.74
   42.87  102.59   48.85  101.24   58.82  100.97   59.82  100.76   60.82  100.27
   63.81   97.57   64.34   97.27   65.43   96.71   66.51   96.94   72.78   98.92
   77.76    99.7   78.76   100.1   82.75  102.48   84.74  102.92   87.71  102.82
   96.56  103.39  107.39  103.48  111.33  104.04  117.23   103.9  149.96  104.91
  163.84  106.02  188.64   106.1   193.6  105.59  213.43  106.07  222.36  106.83
#Mann= 3 , 0 , 0
       0    .045       0   64.34     .04       0   66.51    .055       0
Bank Sta=64.34,66.51
XS Rating Curve= 0 ,0
Exp/Cntr=0.3,0.1

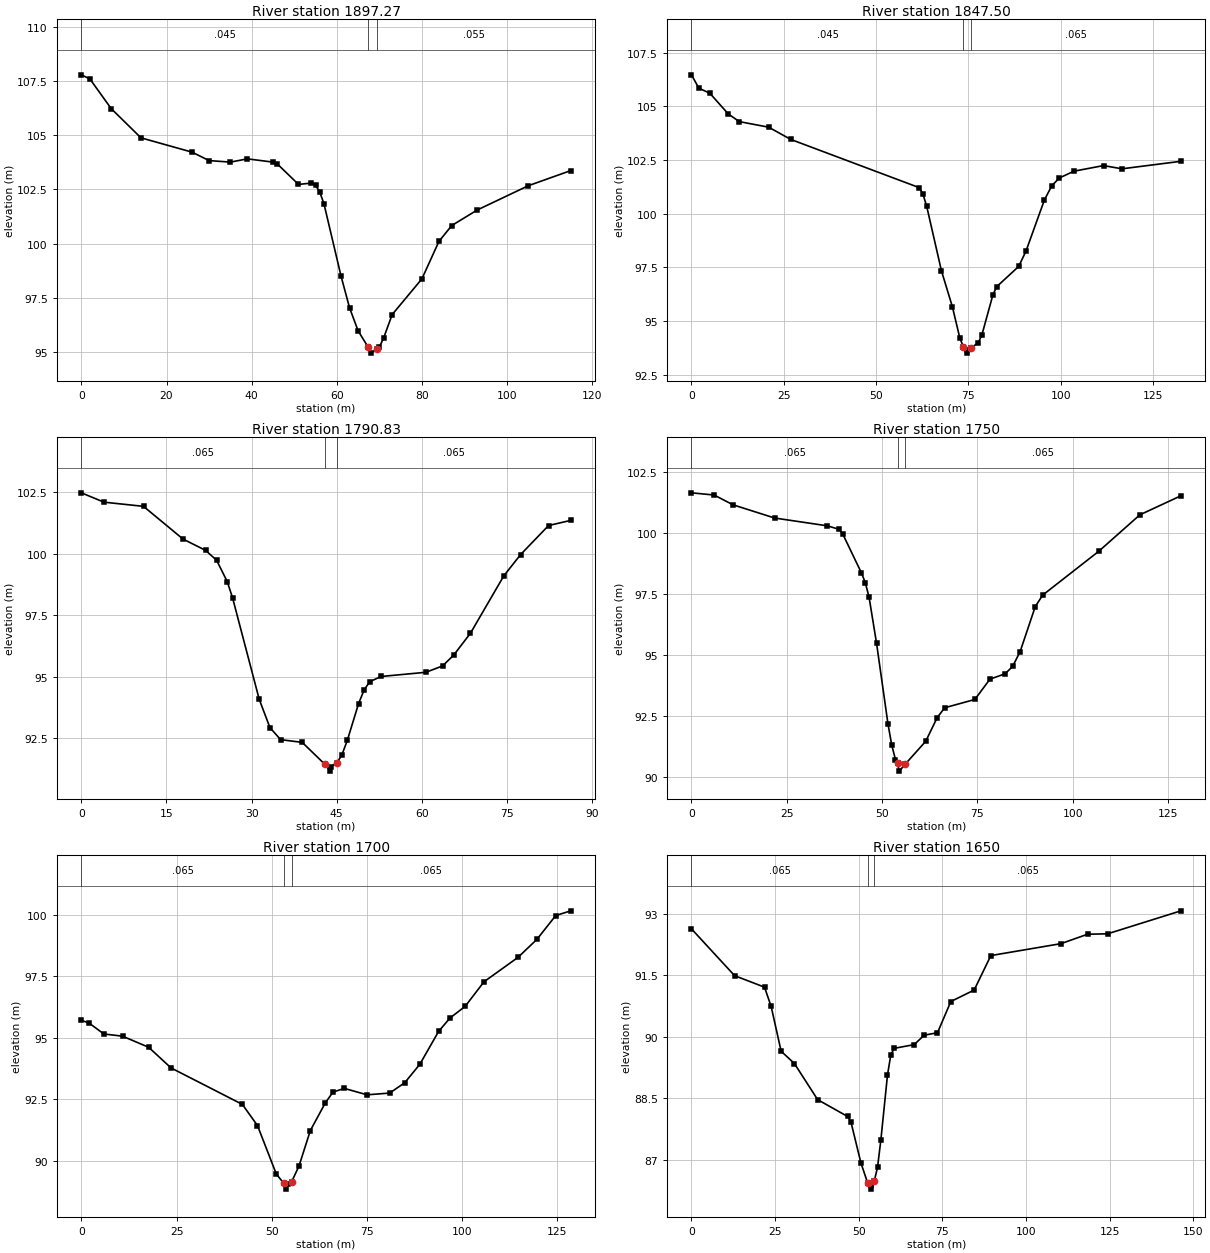
Type RM Length L Ch R = 1 ,1897.27 ,47.88,49.77,51.87
XS GIS Cut Line= 3
 340181.295104985423562.66168213340269.2659301765423589.52807617
340291.4022827155423583.35028076
#Sta/Elev= 30
       0  107.79       2   107.6       7  106.23      14  104.88   25.99  104.22
   29.99  103.83   34.99  103.76   38.99  103.91   44.99  103.76   45.99  103.68
   50.99  102.73   53.99  102.79   54.99  102.69   55.99  102.38   56.99  101.82
   60.99   98.49   62.99   97.03   64.99   95.97   67.34   95.22   67.99   94.94
   69.42   95.13   69.99   95.22   70.99   95.64   72.99   96.72   79.98   98.37
   83.98   100.1   86.98  100.83   92.98  101.55  104.97  102.67  114.96  103.37
#Mann= 3 , 0 , 0
       0    .045       0   67.34     .04       0   69.42    .055       0
Bank Sta=67.34,69.42
XS Rating Curve= 0 ,0
Exp/Cntr=0.3,0.1

Type RM Length L Ch R = 1 ,1847.50 ,59.8,56.68,53.63
XS GIS Cut Line= 3
340175.8522949225423574.91912842340235.4788818365423633.53289795
340282.9793090825423621.75372314
#Sta/Elev= 30
       0  106.47    1.99  105.85    4.98  105.61    9.95  104.65   12.94  104.29
    20.9  104.03   26.88  103.46   61.71  101.21   62.71   100.9    63.7  100.34
   67.69   97.34   70.67   95.65   72.66   94.21   73.66   93.78   74.65    93.5
   74.66   93.66   75.66   93.74   77.64   93.98   78.63   94.34   81.62   96.21
   82.62   96.59   88.61   97.54    90.6   98.26    95.6  100.65   97.59   101.3
   99.59  101.66  103.59  101.98  111.58  102.24  116.57  102.09  132.55  102.44
#Mann= 3 , 0 , 0
       0    .045       0   73.66     .04       0   75.66    .065       0
Bank Sta=73.66,75.66
XS Rating Curve= 0 ,0
Exp/Cntr=0.3,0.1

Type RM Length L Ch R = 1 ,1790.83 ,41.02,40.83,35.12
XS GIS Cut Line= 5
340171.1350708015423681.87109375340193.806884766 5423685.0123291
340208.1732788095423680.52508545340225.0089111335423681.87109375
340248.3541259775423660.78112793
#Sta/Elev= 30
       0  102.48    3.98   102.1   10.95  101.93   17.91   100.6   21.89  100.14
   23.83   99.74   25.71   98.87   26.65   98.21   31.35   94.08   33.24   92.93
   35.12   92.44   38.93   92.33   42.91   91.44    43.9   91.16   43.98   91.34
   45.05   91.51   45.89    91.8   46.88   92.41   48.87   93.91   49.86   94.47
   50.85    94.8   52.84   95.01   60.73   95.18   63.68   95.44   65.64   95.88
   68.59   96.77   74.49   99.11   77.44   99.97   82.36  101.15   86.29  101.36
#Mann= 3 , 0 , 0
       0    .065       0   42.91     .04       0   45.05    .065       0
Bank Sta=42.91,45.05
XS Rating Curve= 0 ,0
Exp/Cntr=0.3,0.1

Type RM Length L Ch R = 1 ,1750    ,52.18,50,44.17
XS GIS Cut Line= 3
340157.321716309 5423744.6494751340236.5733032235423701.55627441
340248.8344726565423665.35791016
#Sta/Elev= 30
       0  101.63    5.95  101.54    10.9  101.14   21.81   100.6   35.69  100.28
   38.66  100.14   39.65   99.96   44.61   98.35    45.6   97.96   46.59   97.37
   48.57   95.47   51.55   92.19   52.54   91.32   53.53   90.72   54.06   90.57
   54.52   90.25   56.06   90.53   61.46   91.47   64.44   92.43   66.42   92.84
   74.35   93.18   78.31   94.01   82.28   94.23   84.26   94.53   86.24   95.14
   90.21   96.98   92.17   97.45  106.87   99.24  117.65  100.73  128.43  101.51
#Mann= 3 , 0 , 0
       0    .065       0   54.06     .04       0   56.06    .065       0
Bank Sta=54.06,56.06
XS Rating Curve= 0 ,0
Exp/Cntr=0.3,0.1

Type RM Length L Ch R = 1 ,1700    ,48.36,50,51.14
XS GIS Cut Line= 4
340200.7401123055423785.32128906340230.0756835945423765.63391113
340250.7296752935423724.97210693340253.8300781255423677.48730469
#Sta/Elev= 30
       0   95.71    1.96   95.61    5.89   95.16    10.8   95.07   17.66   94.62
   23.55   93.78   42.27    92.3   46.24   91.44   51.19   89.47   53.18   89.09
   53.79   88.86   54.17   89.05   55.18   89.15   57.14    89.8   60.12   91.24
   64.08   92.37   66.06    92.8   69.04   92.95   74.99   92.69   80.94   92.76
    84.9   93.18   88.87   93.93   93.82   95.27    96.8   95.81  100.76   96.28
  105.72   97.28  114.64   98.27   119.6      99  124.56   99.97  128.52  100.16
#Mann= 3 , 0 , 0
       0    .065       0   53.18     .04       0   55.18    .065       0
Bank Sta=53.18,55.18
XS Rating Curve= 0 ,0
Exp/Cntr=0.3,0.1

Type RM Length L Ch R = 1 ,1650    ,36.58,50,59.53
XS GIS Cut Line= 4
340229.2329101565423801.52368164 340263.513488775423795.90209961
340281.3558959965423775.84747314340363.0126953135423753.14709473
#Sta/Elev= 30
       0   92.63    12.9   91.49   21.84   91.21   23.82   90.74    26.8   89.65
   30.77   89.35   37.72   88.47   46.67   88.06   47.66   87.93   50.65   86.93
   52.63   86.45   53.63   86.39   53.63   86.29   53.64   86.39   54.63   86.48
   55.62   86.82   56.61   87.48    58.6   89.07   59.59   89.56   60.59   89.72
   66.57   89.81   69.56   90.04   73.55    90.1   77.53   90.86   84.51   91.14
    89.5   91.98  110.44   92.27  118.42    92.5   124.4   92.51  146.33   93.07
#Mann= 3 , 0 , 0
       0    .065       0   52.63     .04       0   54.63    .065       0
Bank Sta=52.63,54.63
XS Rating Curve= 0 ,0
Exp/Cntr=0.3,0.1

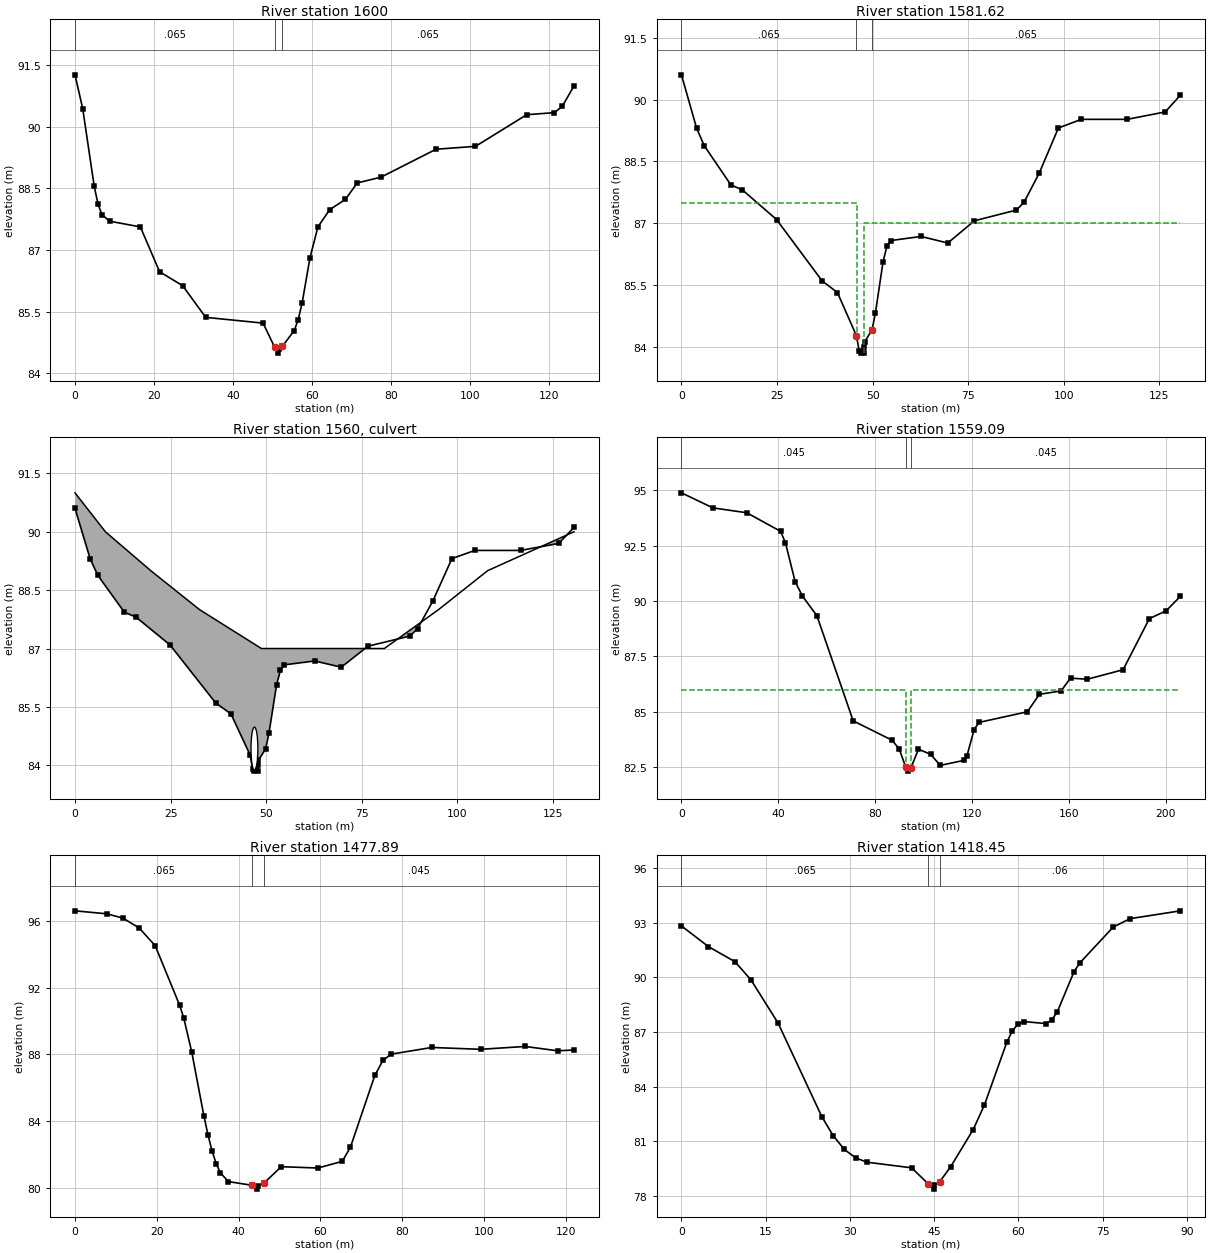
Type RM Length L Ch R = 1 ,1600    ,13.41,18.38,25.54
Node Photo=..\..\..\Corner Brook\Windshield Survey\CB photos\P1000587.JPG
XS GIS Cut Line= 4
340250.8914794925423818.72668457340282.8820800785423827.11669922
340300.237670898 5423825.7387085340373.1644897465423805.23388672
#Sta/Elev= 30
       0   91.26    1.95   90.44    4.86   88.55    5.84   88.11    6.81   87.86
    8.75    87.7   16.54   87.56    21.4   86.47   27.24   86.13   33.07   85.36
   47.58   85.22   50.48   84.64   51.48   84.49   51.49   84.59   52.49   84.66
   55.47   85.04   56.46    85.3   57.46   85.71   59.45   86.81   61.45   87.56
   64.44   87.98   68.42   88.23   71.41   88.63    77.4   88.77   91.35   89.45
  101.32   89.52  114.28   90.29  121.25   90.34  123.25   90.49  126.24   90.99
#Mann= 3 , 0 , 0
       0    .065       0   50.48     .04       0   52.49    .065       0
Bank Sta=50.48,52.49
XS Rating Curve= 0 ,0
Exp/Cntr=0.3,0.1

Type RM Length L Ch R = 1 ,1581.62 ,22.3,21.31,24.75
Node Photo=..\..\..\Corner Brook\Windshield Survey\CB photos\P1000586.JPG
XS GIS Cut Line= 3
340249.5263061525423827.92871094340318.7141113285423850.03131104
340370.2128906255423823.61828613
#Sta/Elev= 30
       0    90.6    3.98    89.3    5.97   88.88   12.93   87.93   15.92   87.81
   24.87   87.09   36.81    85.6   40.79   85.32   45.77   84.27   46.48    83.9
   46.93   83.85   47.76      84   47.82   83.85   47.97   84.13   49.86   84.42
   50.74   84.83   52.73   86.07   53.73   86.44   54.72   86.58   62.68   86.68
   69.65   86.52   76.62   87.06    87.6   87.32    89.6   87.51   93.59   88.22
   98.58   89.31  104.56   89.52  116.54   89.52  126.52    89.7  130.51   90.11
#Mann= 3 , 0 , 0
       0    .065       0   45.77     .04       0   49.86    .065       0
#XS Ineff= 2 , 0
       0   46.03    87.5   47.82       0      87
Permanent Ineff=
       F       F
Bank Sta=45.77,49.86
XS Rating Curve= 0 ,0
Exp/Cntr=0.5,0.3

Type RM Length L Ch R = 2 ,1560    ,,,
Node Photo=..\..\..\Corner Brook\Windshield Survey\CB photos\P1000582.JPG
BEGIN DESCRIPTION:
Candow Drive (1105)
END DESCRIPTION:
Bridge Culvert--1,0,-1,-1, 0
Deck Dist Width WeirC Skew NumUp NumDn MinLoCord MaxHiCord MaxSubmerge Is_Ogee
6.6,6.2,1.67,0, 9, 16, 87, , 0.98, 0, 1,1,,
       0    7.95   19.82   32.57   48.76   80.91   95.09  107.92  130.51
      91      90      89      88      87      87      88      89      90
                                                                        
       0   11.31   23.09   33.66   43.62   55.14   66.53    79.2   94.74  153.99
  168.75  174.52   182.9  192.47  201.94  206.07
      95      94      93      92      91      90      89      88      87      87
      88      89      90      91      92      93
                                                                                
                                                
BR Coef=-1 , 0 , 0 ,, 0 ,,,0.8,-1,,0,
WSPro=,,,, 1 ,,,, 0 ,,,, 0 ,,,,-1 ,-1 ,-1 , 0 , 0 , 0 , 0 , 0
Culvert=3,1.1,1.8,7.5,0.033,0.9,1,34,3,83.88,46.93,83.19,93.7,Culvert #1  , 0 ,1.8
Culvert Bottom n=0.033
BC Design=,, 0 ,, 0 ,,,,,,
BC Use User HTab Curves=0
BC User HTab FreeFlow(D)= 0

Type RM Length L Ch R = 1 ,1559.09 ,37.77,36.77,37
Node Photo=..\..\..\Corner Brook\Windshield Survey\CB photos\P1000583.JPG
XS GIS Cut Line= 3
340187.9370727545423844.78692627 340329.685485845423890.12249756
340381.9757080085423866.81750488
#Sta/Elev= 30
       0   94.89   12.98   94.21   26.97   93.99   40.95   93.15   42.95   92.63
   46.94   90.88   49.94   90.23   55.93   89.34   70.92   84.59    86.9   83.72
   89.89   83.33   92.67   82.49   93.71   82.32   94.75   82.46   97.88   83.31
  102.88   83.08  106.87   82.58  116.86   82.81  117.86   82.99  120.86    84.2
  122.85   84.52  142.83      85  147.82   85.79  156.72   85.94  160.67   86.52
  167.58   86.47  182.38    86.9  193.24   89.21  200.15   89.56  206.07   90.22
#Mann= 3 , 0 , 0
       0    .045       0   92.67     .04       0   94.75    .045       0
#XS Ineff= 2 , 0
       0   92.81      86   94.59       0      86
Permanent Ineff=
       F       F
Bank Sta=92.67,94.75
XS Rating Curve= 0 ,0
Exp/Cntr=0.5,0.3

Type RM Length L Ch R = 1 ,1477.89 ,60.04,59.45,57
XS GIS Cut Line= 4
340209.7918701175423935.84832764 340228.18572998 5423932.9664917
340290.6947021485423937.52667236 340330.507690435423946.17767334
#Sta/Elev= 30
       0   96.58    7.84    96.4   11.76   96.14   15.68   95.56   19.61    94.5
   25.58   90.95   26.58    90.2   28.57   88.13   31.55    84.3   32.55   83.18
   33.54   82.22   34.54   81.48   35.53   80.94   37.52   80.41   43.27   80.19
   44.48   79.96   44.76   80.15   46.25   80.33   50.45    81.3   59.41   81.22
   65.38   81.62   67.37   82.47   73.33   86.75   75.32   87.65   77.31   88.02
   87.26   88.42   99.18   88.31  110.11   88.48  118.06   88.22  122.04   88.27
#Mann= 3 , 0 , 0
       0    .065       0   43.27     .04       0   46.25    .045       0
Bank Sta=43.27,46.25
XS Rating Curve= 0 ,0
Exp/Cntr=0.3,0.1

Type RM Length L Ch R = 1 ,1418.45 ,57.65,59.45,59.69
XS GIS Cut Line= 3
340215.7122802735423993.27050781340236.6005249025423995.65368652
340303.918518066  5423987.253479
#Sta/Elev= 30
       0   92.83    4.78    91.7    9.56   90.86   12.42   89.85    17.2    87.5
   25.01   82.35   27.01   81.32      29   80.56      31    80.1      33   79.86
   40.98   79.55   43.98   78.66   44.97   78.38   44.98   78.58   45.98   78.78
   47.96   79.62   51.95   81.65   53.95      83   57.94   86.45   58.93   87.07
   59.93   87.44   60.93   87.58   64.92   87.47   65.92   87.66   66.92   88.11
   69.91   90.32   70.91   90.79   76.89   92.77   79.89   93.23   88.86   93.66
#Mann= 3 , 0 , 0
       0    .065       0   43.98     .04       0   45.98     .06       0
Bank Sta=43.98,45.98
XS Rating Curve= 0 ,0
Exp/Cntr=0.3,0.1