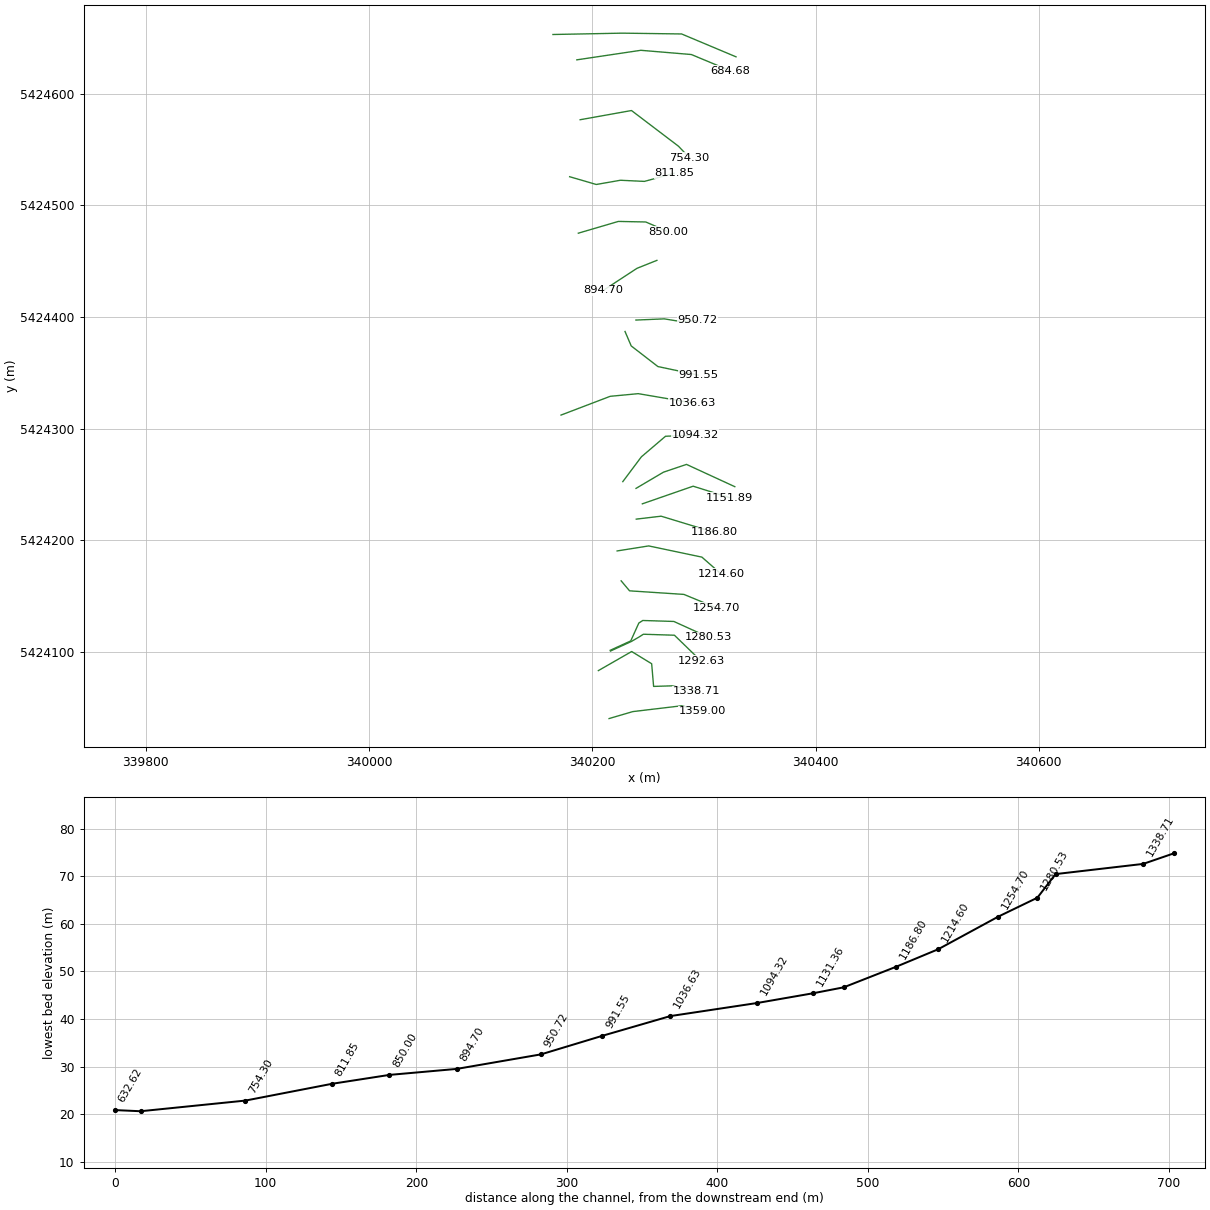
HEC-RAS study PetriesBrk_v001.prj: Petries_Brook

--- PetriesBrk_v001.g01 (geometry) --- (continued)

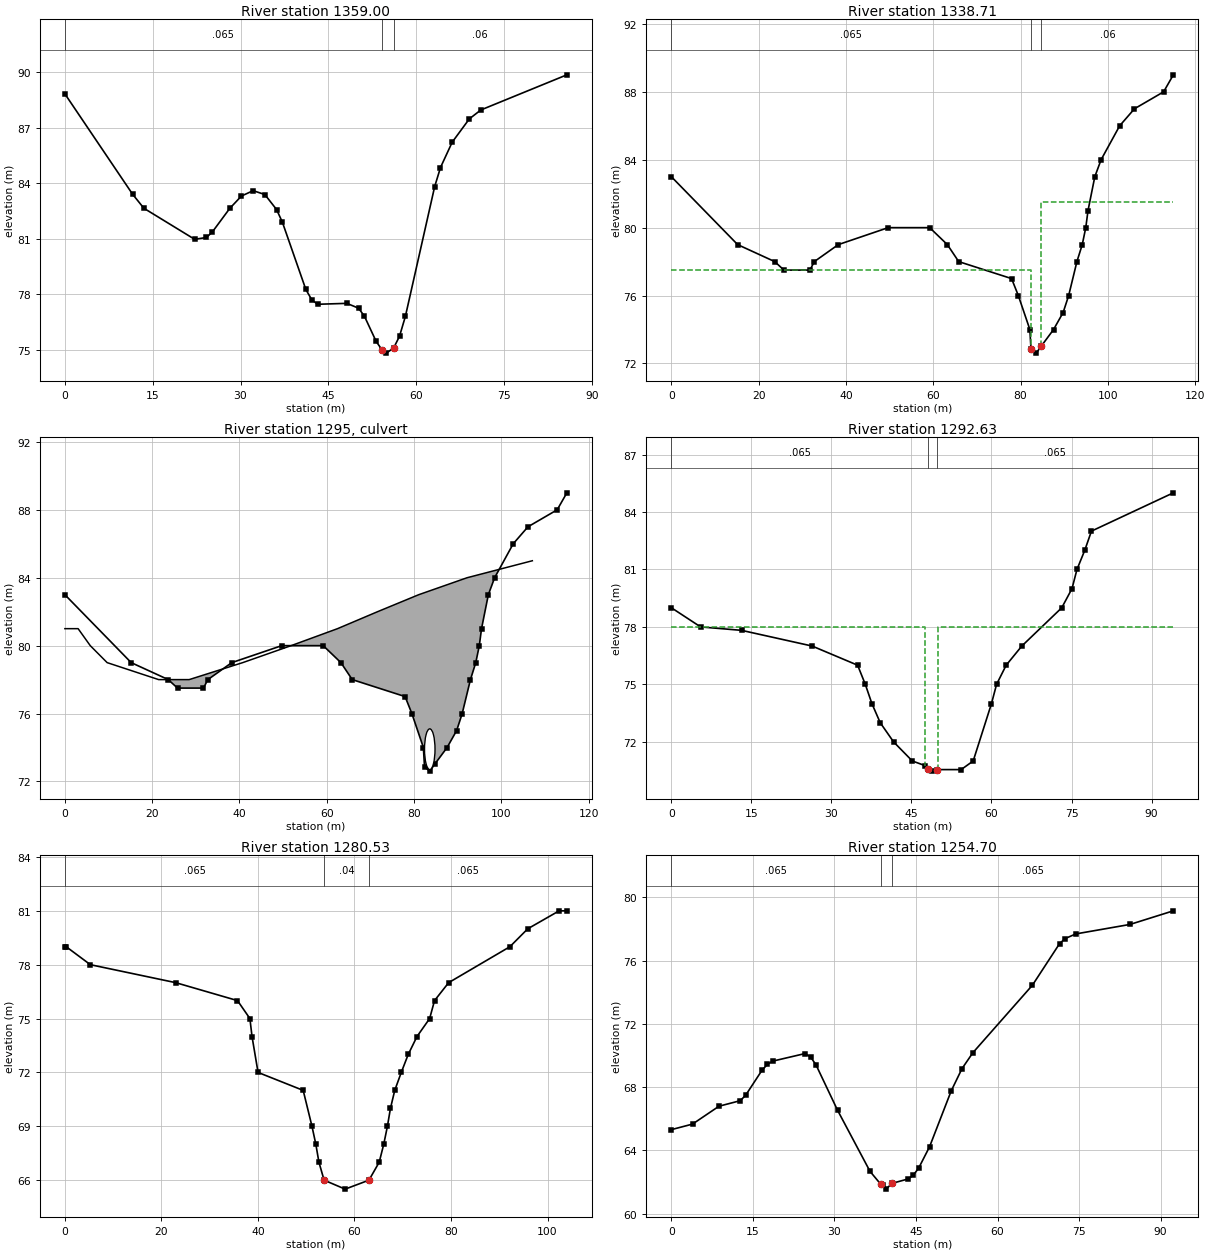
Type RM Length L Ch R = 1 ,1359.00 ,18.95,20.29,21.35
XS GIS Cut Line= 4
340215.0609130865424040.37988281340236.3314819345424046.61627197
340280.0125122075424051.82092285 340298.963073735424046.85308838
#Sta/Elev= 30
       0   88.83   11.56   83.41   13.49   82.65   22.17   80.97   24.17   81.07
   25.17   81.36   28.16   82.64   30.16   83.31   32.16    83.6   34.16   83.39
   36.16   82.58   37.16   81.89   41.16   78.26   42.16   77.71   43.16   77.46
   48.16   77.51   50.16   77.25   51.16   76.82   53.16   75.46   54.16      75
   54.91   74.82   56.16    75.1   57.16   75.73   58.16    76.8   63.16   83.81
   64.16   84.85   66.16   86.22   69.09   87.48   71.05   87.96   85.75   89.86
#Mann= 3 , 0 , 0
       0    .065       0   54.16     .04       0   56.16     .06       0
#XS Ineff= 2 , 0
       0   32.16    83.6               0
Permanent Ineff=
       F       F
Bank Sta=54.16,56.16
XS Rating Curve= 0 ,0
Exp/Cntr=0.3,0.1

Type RM Length L Ch R = 1 ,1338.71 ,61.19,58.18,56.11
Node Photo=..\..\..\Corner Brook\Windshield Survey\CB photos\P1000581.JPG
XS GIS Cut Line= 6
      340205.468     5424083.335       340235.29      5424100.44
       340253.21     5424089.482      340254.948     5424069.169
      340271.665     5424069.704      340293.571     5424064.924
#Sta/Elev= 30
       0      83   15.19      79   23.68      78    25.8    77.5   31.75    77.5
   32.75      78   38.24      79   49.68      80   59.18      80   63.23      79
   65.83      78   77.94      77   79.49      76   82.13      74   82.39   72.86
   83.59   72.61   84.79  73.039   87.56      74   89.75      75   91.02      76
   92.91      78   94.13      79   94.94      80   95.45      81   97.01      83
   98.45      84  102.71      86  106.09      87  112.78      88     115      89
#Mann= 3 , 0 , 0
       0    .065       0   82.39     .04       0   84.79     .06       0
#XS Ineff= 2 , 0
       0   82.39    77.5   84.79       0    81.5
Permanent Ineff=
       F       F
Bank Sta=82.39,84.79
XS Rating Curve= 0 ,0
Exp/Cntr=0.6,0.4

Type RM Length L Ch R = 2 ,1295    ,,,
Node Photo=..\..\..\Corner Brook\Windshield Survey\CB photos\P1000577.JPG
BEGIN DESCRIPTION:
O'Conner Drive (1104)
END DESCRIPTION:
Bridge Culvert--1,0,-1,-1, 0
Deck Dist Width WeirC Skew NumUp NumDn MinLoCord MaxHiCord MaxSubmerge Is_Ogee
17.2,7.7,1.67,0, 13, 12, 78, , 0.98, 0, 0.6,0.4,,
       0    3.03    5.81    9.68   21.48   28.47   40.74   51.83   62.45   71.63
   81.05   92.14  107.09
      81      81      80      79      78      78      79      80      81      82
      83      84      85
                                                                                
                        
       0    2.58     9.9   23.38   35.14   44.69   53.76   62.43   73.22   84.61
   87.39   104.3
      78      78      78      79      80      81      82      83      84      85
      85    86.5
                                                                                
                
BR Coef=-1 , 0 , 0 ,, 0 ,,,0.8,0,,0,72.86
WSPro=,,,, 1 ,,,, 0 ,,,, 0 ,,,,-1 ,-1 ,-1 , 0 , 0 , 0 , 0 , 0
Culvert=1,2.4,,43,0.035,0.9,1,2,3,72.7,83.59,70.47,48.78,Culvert #1  , 0 ,2.25
Culvert Bottom n=0.035
Culvert Bottom Depth=2.4
BC Design=,, 0 ,, 0 ,,,,,,
BC Use User HTab Curves=0
BC User HTab FreeFlow(D)= 0

Type RM Length L Ch R = 1 ,1292.63 ,12.1,12.1,12.1
Node Photo=..\..\..\Corner Brook\Windshield Survey\CB photos\P1000579.JPG
XS GIS Cut Line= 6
      340216.309     5424100.844      340235.021     5424109.429
       340242.22     5424113.623      340245.765     5424115.911
      340273.603     5424115.035      340297.367     5424092.005
#Sta/Elev= 26
       0      79    5.48      78   13.16   77.82   26.39      77   34.91      76
   36.35      75   37.58      74   39.14      73   41.64      72   45.16      71
   47.62   70.75   48.17   70.56   48.78   70.47   49.86   70.55   54.31   70.55
   56.57      71      60      74   60.95      75   62.75      76   65.68      77
   73.17      79   75.09      80   76.02      81   77.48      82   78.73      83
   94.08      85
#Mann= 3 , 0 , 0
       0    .065       0   48.17     .04       0   49.86    .065       0
#XS Ineff= 2 , 0
       0   47.58      78   49.98       0      78
Permanent Ineff=
       F       F
Bank Sta=48.17,49.86
XS Rating Curve= 0 ,0
Exp/Cntr=0.5,0.3

Type RM Length L Ch R = 1 ,1280.53 ,25.56,25.82,25.09
XS GIS Cut Line= 6
      340216.083     5424101.519      340234.472     5424109.933
       340241.71     5424125.948      340245.255     5424128.236
      340273.093     5424127.359      340303.914     5424113.364
#Sta/Elev= 30
       0      79     .28      79    5.28      78   22.95      77   35.76      76
   38.33      75   38.77      74   40.02      72   49.37      71   51.19      69
   51.99      68   52.63      67    53.7      66   58.06    65.5      63      66
   65.12      67   66.06      68   66.82      69   67.45      70   68.34      71
   69.69      72   71.13      73   72.95      74   75.57      75   76.58      76
   79.51      77   92.19      79    95.9      80   102.4      81     104      81
#Mann= 3 , 0 , 0
       0    .065       0    53.7     .04       0      63    .065       0
Bank Sta=53.7,63
XS Rating Curve= 0 ,0
Exp/Cntr=0.3,0.1

Type RM Length L Ch R = 1 ,1254.70 ,40.6,40.1,39.23
XS GIS Cut Line= 4
 340225.886718755424163.72808838340233.4039306645424154.79608154
340282.0579223635424151.59912109 340311.568298345424139.45507813
#Sta/Elev= 30
       0   65.31    3.89   65.66    8.76   66.79   12.67   67.14   13.66   67.48
   16.65   69.05   17.64   69.43   18.64   69.64   24.61   70.12   25.61    69.9
    26.6   69.41   30.58   66.53   36.55   62.67   38.54   61.85   38.98   61.83
   39.54   61.55   40.54   61.91   43.52   62.19   44.51   62.43   45.51   62.89
    47.5   64.23   51.48   67.76   53.47   69.17   55.46   70.17   66.42   74.44
    71.4   77.06    72.4   77.38   74.39   77.68   84.37   78.28   92.34   79.14
#Mann= 3 , 0 , 0
       0    .065       0   38.54    .035       0   40.54    .065       0
Bank Sta=38.54,40.54
XS Rating Curve= 0 ,0
Exp/Cntr=0.3,0.1

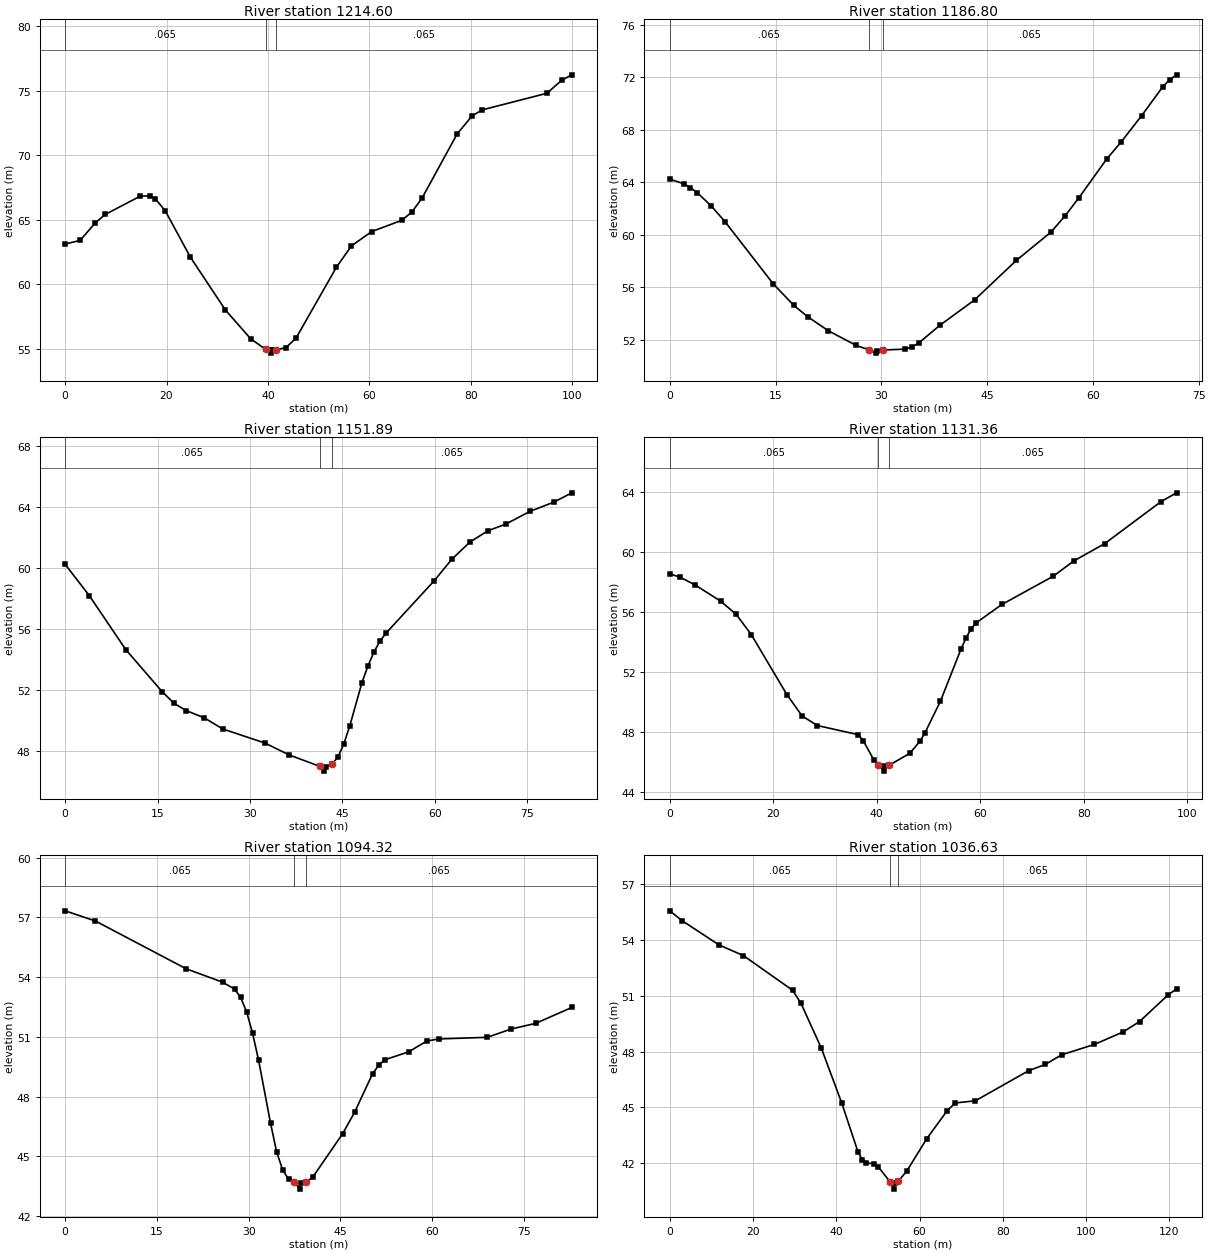
Type RM Length L Ch R = 1 ,1214.60 ,28.26,27.8,27.43
XS GIS Cut Line= 4
 340222.293090825424190.53369141340250.554077148 5424195.0333252
340298.2213134775424184.99389648340315.2128906255424170.09613037
#Sta/Elev= 30
       0   63.12    2.96    63.4    5.92   64.75    7.89   65.41    14.8   66.83
   16.78   66.86   17.76   66.64   19.74    65.7   24.67   62.12    31.6   58.01
   36.57   55.78   39.55   54.95   40.55   54.89   40.55   54.66   40.71    54.9
   41.55   54.91   43.53   55.09   45.52   55.81   53.47    61.3   56.45   62.97
   60.43   64.08   66.39   64.96   68.38    65.6   70.37   66.67   77.33   71.67
   80.28   73.06   82.24   73.52   95.02   74.81   97.96   75.83   99.93   76.24
#Mann= 3 , 0 , 0
       0    .065       0   39.55    .035       0   41.55    .065       0
Bank Sta=39.55,41.55
XS Rating Curve= 0 ,0
Exp/Cntr=0.3,0.1

Type RM Length L Ch R = 1 ,1186.80 ,25.25,34.92,35.78
XS GIS Cut Line= 3
340239.397521973 5424219.0322876340261.7108764655424221.66650391
340308.9729003915424207.26672363
#Sta/Elev= 30
       0   64.25    1.95   63.91    2.93    63.6    3.91   63.21    5.86   62.22
    7.82   61.02   14.65   56.29   17.58   54.64   19.54   53.78   22.47   52.71
   26.42   51.59   28.24   51.25   29.24      51   29.39    51.2   30.24   51.24
   33.34    51.3   34.33   51.47   35.31   51.77   38.28   53.11   43.22   55.05
   49.15   58.06   54.09   60.23   56.07   61.46   58.04   62.84   61.99    65.8
   63.97   67.05   66.93   69.09    69.9   71.27   70.89   71.82   71.88    72.2
#Mann= 3 , 0 , 0
       0    .065       0   28.24    .035       0   30.24    .065       0
Bank Sta=28.24,30.24
XS Rating Curve= 0 ,0
Exp/Cntr=0.3,0.1

Type RM Length L Ch R = 1 ,1151.89 ,20.73,20.52,20.47
XS GIS Cut Line= 3
340244.8441162115424232.72967529340290.3491210945424248.53430176
340322.8529052735424238.34912109
#Sta/Elev= 30
       0   60.23    3.93   58.17    9.83   54.64   15.73   51.88    17.7    51.1
   19.66   50.63   22.61   50.15   25.56   49.43   32.44    48.5   36.37   47.72
   41.29   46.98   41.93   46.66   42.27   46.95   43.29   47.12   44.24   47.56
   45.22   48.44   46.21   49.65   48.17   52.47   49.14   53.56   50.12   54.48
   51.09   55.18   52.06   55.71   59.85   59.13   62.77   60.57   65.69   61.69
   68.61   62.43   71.53   62.87   75.42    63.7   79.31   64.31   82.23   64.92
#Mann= 3 , 0 , 0
       0    .065       0   41.29    .035       0   43.29    .065       0
Bank Sta=41.29,43.29
XS Rating Curve= 0 ,0
Exp/Cntr=0.3,0.1

Type RM Length L Ch R = 1 ,1131.36 ,25.77,37.05,38
XS GIS Cut Line= 4
340239.2006835945424246.57751465340263.7606811525424261.08288574
340284.4135131845424268.05688477340327.6729125985424248.11169434
#Sta/Elev= 30
       0   58.55    1.97   58.34    4.92   57.81    9.84   56.73   12.79   55.87
   15.74   54.51   22.62   50.51   25.57   49.08   28.52   48.44   36.45   47.83
   37.44    47.4   39.42   46.16   40.33   45.84   41.33    45.4    41.4   45.71
   42.33   45.78   46.36   46.58   48.34   47.38   49.33   47.96   52.31   50.06
   56.28   53.53   57.27   54.29   58.26   54.89   59.25    55.3   64.22   56.52
   74.14    58.4   78.11   59.42   84.06   60.57   94.98   63.38   97.96   63.96
#Mann= 3 , 0 , 0
       0    .065       0   40.33    .035       0   42.33    .065       0
Bank Sta=40.33,42.33
XS Rating Curve= 0 ,0
Exp/Cntr=0.3,0.1

Type RM Length L Ch R = 1 ,1094.32 ,60.38,57.68,53.64
XS GIS Cut Line= 4
 340227.351684575424252.60668945340243.9583129885424274.79992676
340265.6029052735424293.26312256 340292.285278325424294.38208008
#Sta/Elev= 30
       0   57.33    4.95   56.82    19.8   54.42   25.74   53.75   27.72    53.4
    28.7   52.98   29.68   52.26   30.66   51.18   31.64   49.83    33.6   46.66
   34.59   45.23   35.57   44.33   36.55   43.85   37.43   43.72   38.44   43.36
   38.51   43.68   39.44   43.71   40.47   43.95   45.38   46.14   47.34   47.22
   50.28   49.15   51.26   49.57   52.24   49.85   56.17   50.25   59.14   50.79
   61.11    50.9   69.03   50.98   72.98    51.4   76.94   51.68   82.87   52.48
#Mann= 3 , 0 , 0
       0    .065       0   37.43    .035       0   39.44    .065       0
Bank Sta=37.43,39.44
XS Rating Curve= 0 ,0
Exp/Cntr=0.3,0.1

Type RM Length L Ch R = 1 ,1036.63 ,48.92,45.08,39.98
XS GIS Cut Line= 4
340171.9953002935424312.23510742340216.0892944345424329.05828857
340241.2180786135424331.42767334 340289.816284185424323.13470459
#Sta/Elev= 30
       0   55.57    2.95   55.04    11.8   53.74    17.7   53.16    29.5    51.3
   31.46   50.62   36.38    48.2    41.3   45.24   45.23    42.6   46.21    42.2
   47.19   42.02   49.14   41.97   50.11    41.8   52.86   41.02   53.88   40.61
   53.99   40.94   54.89   41.04    56.9   41.57   61.76   43.33   66.61   44.82
   68.55   45.24   73.42   45.36   86.24   46.98   90.18   47.31   94.13   47.83
  102.02   48.39  108.92   49.06  112.86   49.62  119.76   51.06  121.74   51.37
#Mann= 3 , 0 , 0
       0    .065       0   52.86    .035       0   54.89    .065       0
Bank Sta=52.86,54.89
XS Rating Curve= 0 ,0
Exp/Cntr=0.3,0.1

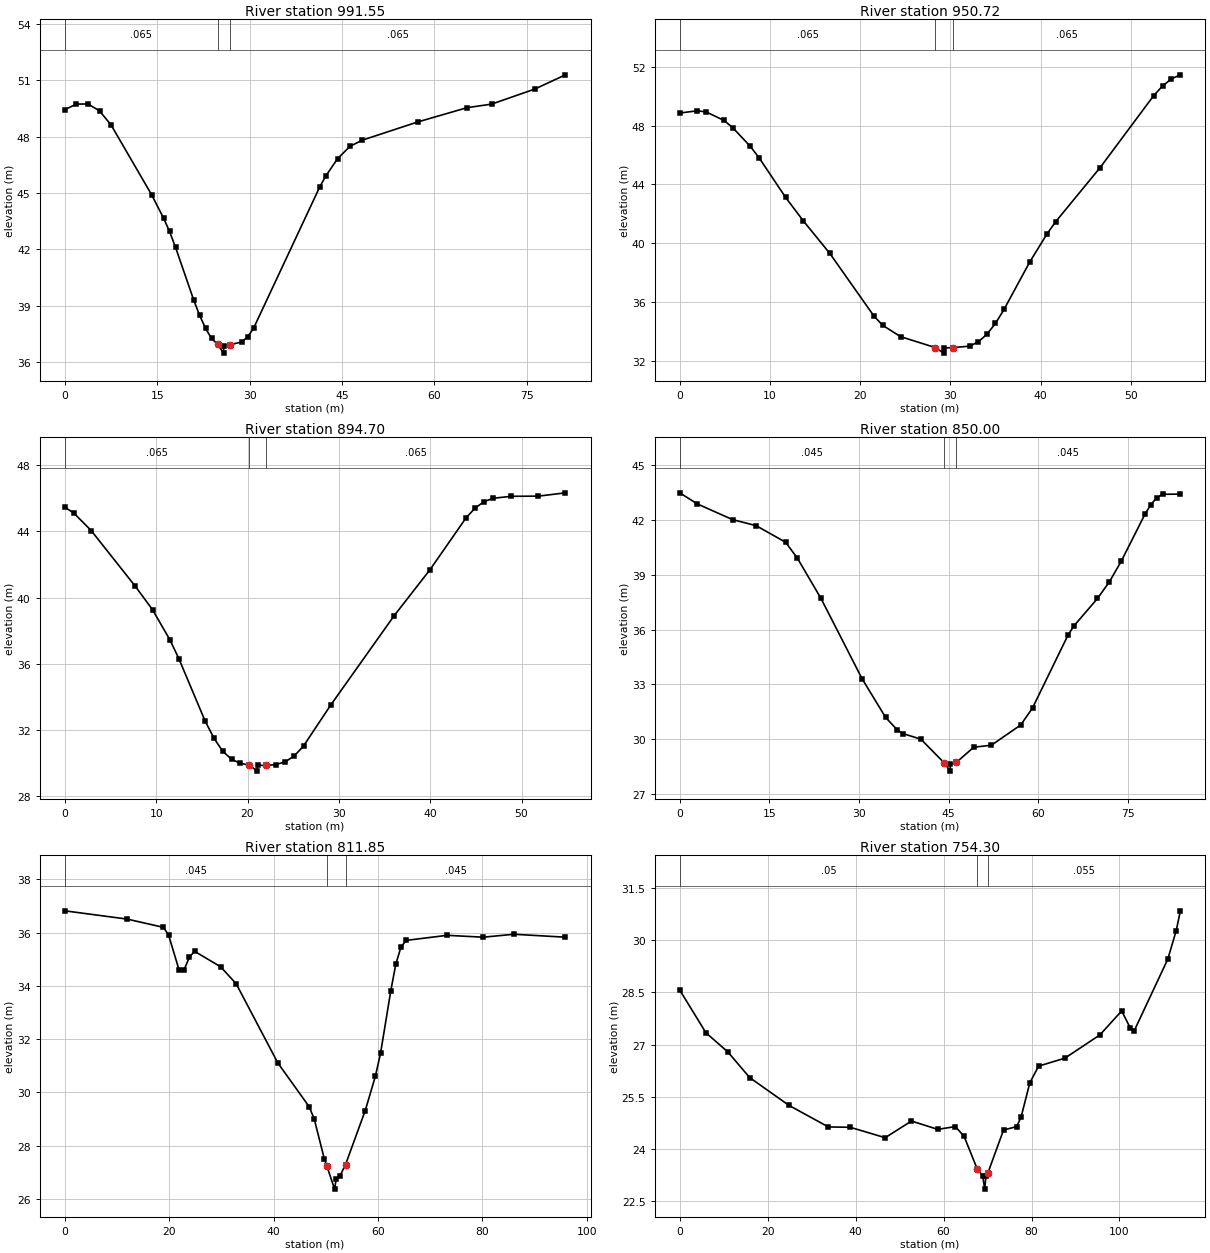
Type RM Length L Ch R = 1 ,991.55  ,37.49,40.83,42.68
XS GIS Cut Line= 4
340229.3386840825424387.13153076340234.8859252935424374.19451904
340258.7916870125424355.71289063340294.9808959965424348.05627441
#Sta/Elev= 30
       0   49.44    1.88   49.73    3.75   49.74    5.63   49.37    7.51   48.62
   14.08   44.91   16.03   43.66      17   42.95   17.98    42.1    20.9   39.32
   21.87   38.49   22.85   37.79   23.82   37.25    24.8   36.94   25.77   36.47
   25.81   36.87   26.81   36.92    28.7   37.06   29.67   37.33   30.65    37.8
   41.37   45.31   42.34   45.89   44.29   46.83   46.29   47.48   48.29   47.81
   57.29   48.78   65.29   49.54   69.29   49.73   76.28   50.53   81.28   51.29
#Mann= 3 , 0 , 0
       0    .065       0    24.8    .035       0   26.81    .065       0
Bank Sta=24.8,26.81
XS Rating Curve= 0 ,0
Exp/Cntr=0.3,0.1

Type RM Length L Ch R = 1 ,950.72  ,51.8,56.02,58.21
XS GIS Cut Line= 4
340239.1104736335424397.36450195340264.5355224615424398.42327881
340280.5437011725424395.83508301340294.3154907235424397.01171875
#Sta/Elev= 30
       0   48.85    1.96      49    2.94   48.92    4.89   48.35    5.87   47.86
    7.83   46.58    8.81    45.8   11.74   43.12    13.7   41.53   16.64   39.32
   21.53   35.07   22.51   34.44   24.47   33.68   28.31   32.94   29.26   32.56
   29.31   32.91   30.31   32.94   32.12   33.03   33.08   33.32   34.03   33.83
   34.99   34.57   35.94   35.52    38.8   38.75   40.71   40.65   41.66   41.47
    46.6   45.15   52.52   50.02   53.51   50.68    54.5   51.17   55.49   51.44
#Mann= 3 , 0 , 0
       0    .065       0   28.31    .035       0   30.31    .065       0
Bank Sta=28.31,30.31
XS Rating Curve= 0 ,0
Exp/Cntr=0.3,0.1

Type RM Length L Ch R = 1 ,894.70  ,47,44.71,42.01
XS GIS Cut Line= 3
340257.9028930665424450.84350586340240.0692749025424443.71368408
340210.2770996095424424.21173096
#Sta/Elev= 30
       0   45.46     .96   45.13    2.88   44.06    7.68   40.71     9.6   39.27
   11.52   37.43   12.48   36.31   15.36   32.53   16.33   31.49   17.29    30.7
   18.25   30.22   19.21   29.97    20.2   29.87   21.06    29.5   21.11   29.85
   22.02   29.85   23.08   29.89   24.15   30.07   25.14   30.43   26.13   31.02
    29.1   33.49   36.02   38.88   39.98   41.69   43.93   44.83   44.92   45.42
   45.91   45.81    46.9   46.01   48.88   46.13   51.85   46.14   54.81   46.34
#Mann= 3 , 0 , 0
       0    .065       0    20.2    .035       0   22.02    .065       0
Bank Sta=20.2,22.02
XS Rating Curve= 0 ,0
Exp/Cntr=0.3,0.1

Type RM Length L Ch R = 1 ,850.00  ,37.6,38.14,38.02
XS GIS Cut Line= 4
340187.4959106455424475.19091797340223.3823242195424485.72192383
340247.9417114265424485.22027588340267.9468994145424476.56628418
#Sta/Elev= 30
       0   43.49    2.95   42.88    8.86   42.02   12.79   41.69   17.72   40.78
   19.68   39.91   23.62   37.71   30.51    33.3   34.45   31.18   36.42   30.49
    37.4   30.29   40.35   29.99   44.28   28.68   45.26   28.24   45.28   28.61
   46.28   28.72   49.19   29.55   52.14   29.66   57.05   30.77   59.02    31.7
   64.94   35.68   65.93   36.19   69.89    37.7   71.87   38.61   73.85   39.73
   77.82   42.31   78.81   42.84    79.8   43.22   80.79   43.41   83.76   43.42
#Mann= 3 , 0 , 0
       0    .045       0   44.28    .035       0   46.28    .045       0
Bank Sta=44.28,46.28
XS Rating Curve= 0 ,0
Exp/Cntr=0.3,0.1

Type RM Length L Ch R = 1 ,811.85  ,66.88,57.56,53.13
XS GIS Cut Line= 5
340179.7424926765424525.77111816340203.6002807625424518.81170654
340225.2055053715424522.59832764340246.7081298835424521.57489014
340273.3305053715424528.84130859
#Sta/Elev= 30
       0   36.82   11.93   36.51   18.89    36.2   19.88   35.91   21.87   34.61
   22.86   34.61   23.86   35.08   24.85    35.3   29.84   34.72   32.83   34.08
    40.8   31.11   46.79   29.47   47.77   29.01   49.72    27.5   50.21   27.23
   51.68   26.37   51.99   26.75   52.66   26.85   53.77   27.29   57.55   29.32
   59.51   30.62   60.49   31.48   62.44   33.81   63.42   34.83    64.4   35.46
   65.38   35.71   73.24    35.9   80.14   35.83   86.05   35.94   95.91   35.83
#Mann= 3 , 0 , 0
       0    .045       0   50.21    .045       0   53.77    .045       0
Bank Sta=50.21,53.77
XS Rating Curve= 0 ,0
Exp/Cntr=0.3,0.1

Type RM Length L Ch R = 1 ,754.30  ,55.1,69.62,72.69
XS GIS Cut Line= 4
340189.1492919925424576.81689453 340235.136718755424585.06170654
340277.2058715825424553.11328125340287.0748901375424542.75292969
#Sta/Elev= 30
       0   28.57    5.96   27.34   10.93   26.79   15.91   26.05   24.85   25.25
    33.8   24.63   38.77   24.62   46.72   24.32    52.7    24.8   58.68   24.56
   62.67   24.64   64.66   24.36   67.65   23.42   68.87   23.23   69.36   22.84
   69.64   23.23   70.09   23.31   73.63   24.54   76.62   24.64   77.62   24.91
   79.61    25.9   81.61   26.38   87.59   26.61   95.56   27.28   100.5   27.97
  102.41   27.49  103.36    27.4  110.99   29.46   112.9   30.28  113.85   30.85
#Mann= 3 , 0 , 0
       0     .05       0   67.65    .035       0   70.09    .055       0
Bank Sta=67.65,70.09
XS Rating Curve= 0 ,0
Exp/Cntr=0.3,0.1

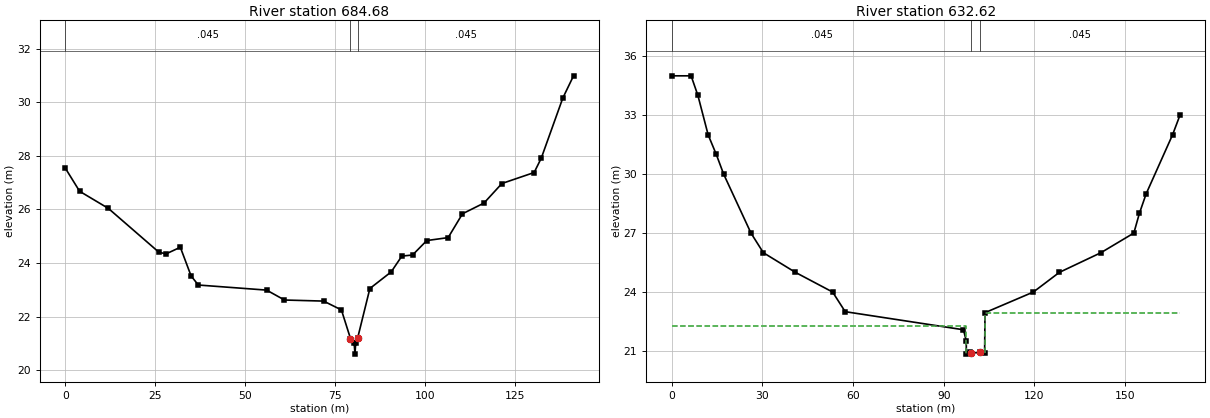
Type RM Length L Ch R = 1 ,684.68  ,15.33,16.82,17.85
XS GIS Cut Line= 4
340186.1815185555424630.47332764340243.4896850595424639.01428223
340288.7612915045424635.23052979340323.6533203135424620.69268799
#Sta/Elev= 30
       0   27.55       4   26.68   11.99   26.04   25.97   24.41   27.97   24.34
   31.97   24.59   34.96   23.52   36.96   23.18   55.94   22.99    60.9   22.62
   71.77   22.58   76.71   22.25   79.23   21.18   80.24      21   80.48    20.6
   80.66      21   81.25   21.22   84.61   23.05   90.53   23.67   93.49   24.26
   96.46    24.3  100.41   24.84  106.35   24.95  110.33   25.84   116.3   26.24
  121.28   26.97  130.23   27.38  132.22   27.92  138.19   30.16  141.17   30.99
#Mann= 3 , 0 , 0
       0    .045       0   79.23    .035       0   81.25    .045       0
Bank Sta=79.23,81.25
XS Rating Curve= 0 ,0
Exp/Cntr=0.3,0.1

Type RM Length L Ch R = 1 ,632.62  ,25.35,24.01,23.18
Node Photo=..\..\..\Corner Brook\Windshield Survey\CB photos\P1000570.JPG
XS GIS Cut Line= 4
      340164.761      5424653.17      340226.992     5424654.375
      340280.058     5424653.652      340328.782     5424633.164
#Sta/Elev= 27
       0      35    6.43      35    8.68      34   12.06      32   14.76      31
   17.19      30   26.23      27   30.33      26   40.94      25   53.24      24
   57.41      23   96.53   22.08   97.47   21.51   97.48   20.84   98.54   20.97
   99.13   20.88  101.96   20.93  103.53   20.88  103.66   22.95  119.66      24
  128.26      25     142      26   152.9      27  154.73      28  156.98      29
  165.71      32  168.17      33
#Mann= 3 , 0 , 0
       0    .045       0   99.13    .035       0  101.96    .045       0
#XS Ineff= 2 , 0
       0   97.48   22.25  103.53       0   22.95
Permanent Ineff=
       F       F
Bank Sta=99.13,101.96
XS Rating Curve= 0 ,0
Exp/Cntr=0.5,0.3