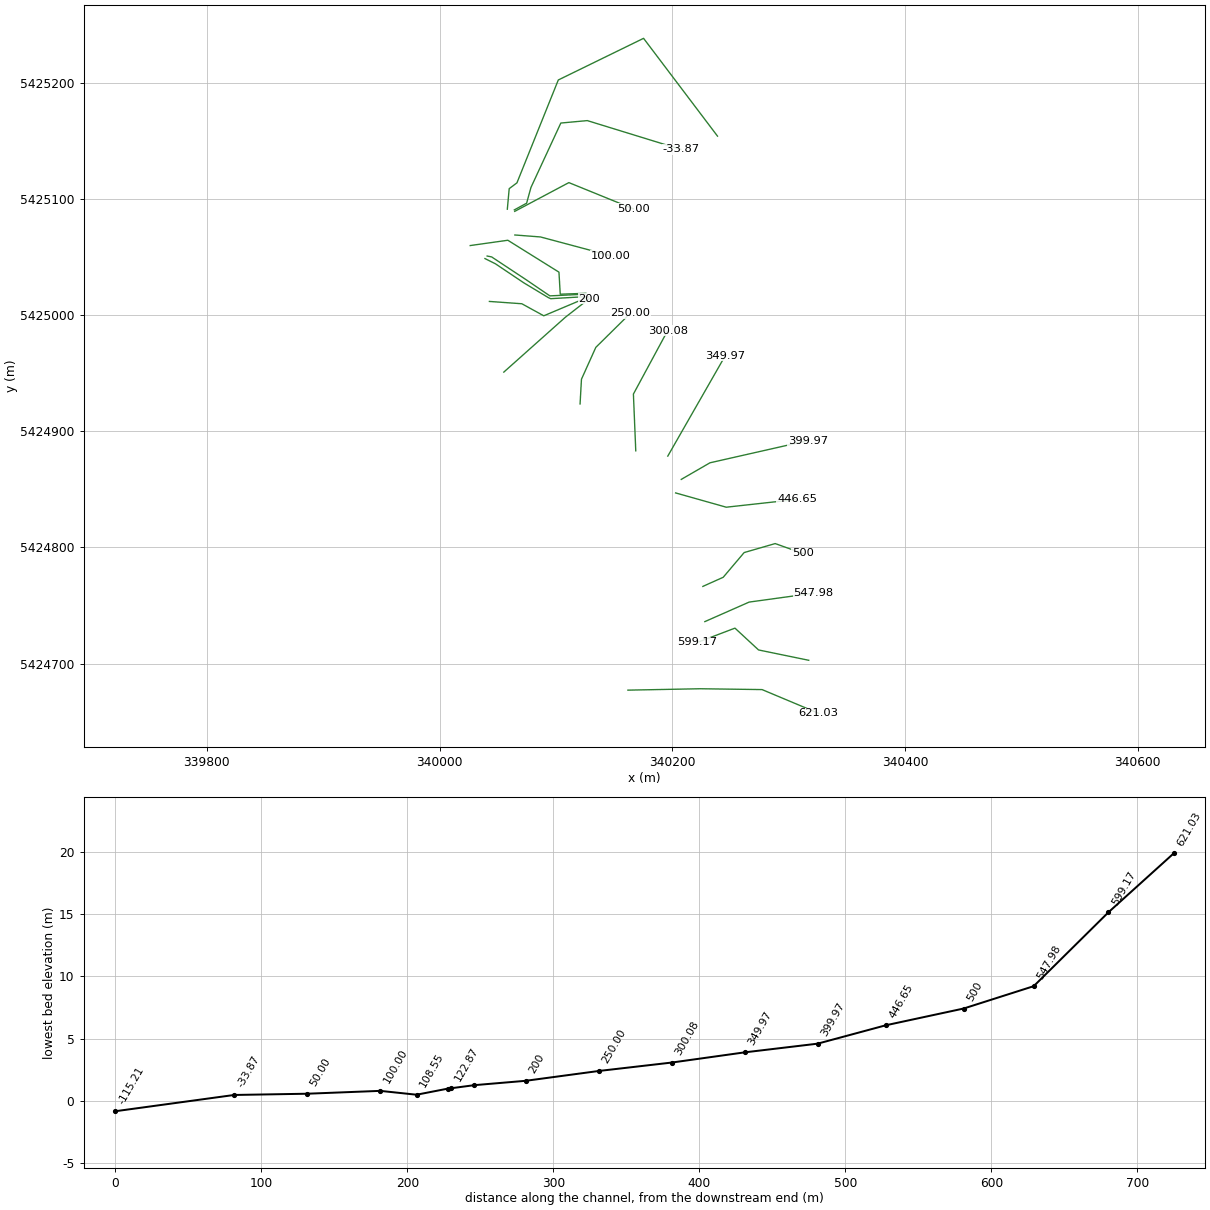
HEC-RAS study PetriesBrk_v001.prj: Petries_Brook

--- PetriesBrk_v001.g01 (geometry) --- (continued)

Type RM Length L Ch R = 3 ,625     ,,,
Node Photo=..\..\..\Corner Brook\Windshield Survey\CB photos\P1000565.JPG
BEGIN DESCRIPTION:
Petrie's Street (1102)
END DESCRIPTION:
Bridge Culvert--1,0,-1,-1, 0
Deck Dist Width WeirC Skew NumUp NumDn MinLoCord MaxHiCord MaxSubmerge Is_Ogee
6.47,10.6,1.67,0, 8, 8, 22.36, , 0.98, 0, 0,0,,
   57.42   80.93   90.75   97.48  103.53  103.66  105.36  113.21
      23      22      22   22.36    22.9   22.95   22.67      23
                           21.72   21.97
   51.56   90.75   95.79   98.93  104.94  105.01  113.21   131.8
      23   22.22   21.87   21.82   22.07   22.07      23      24
                           21.19    21.4
BR Coef=-1 , 0 , 0 ,, 0 ,,,0.8,-1,,0,
WSPro=,,,, 1 ,,,, 0 ,,,, 0 ,,,,-1 ,-1 ,-1 , 0 , 0 , 0 , 0 , 0
BC Design=,, 0 ,, 0 ,,,,,,
BC Use User HTab Curves=0
BC User HTab FreeFlow(D)= 0

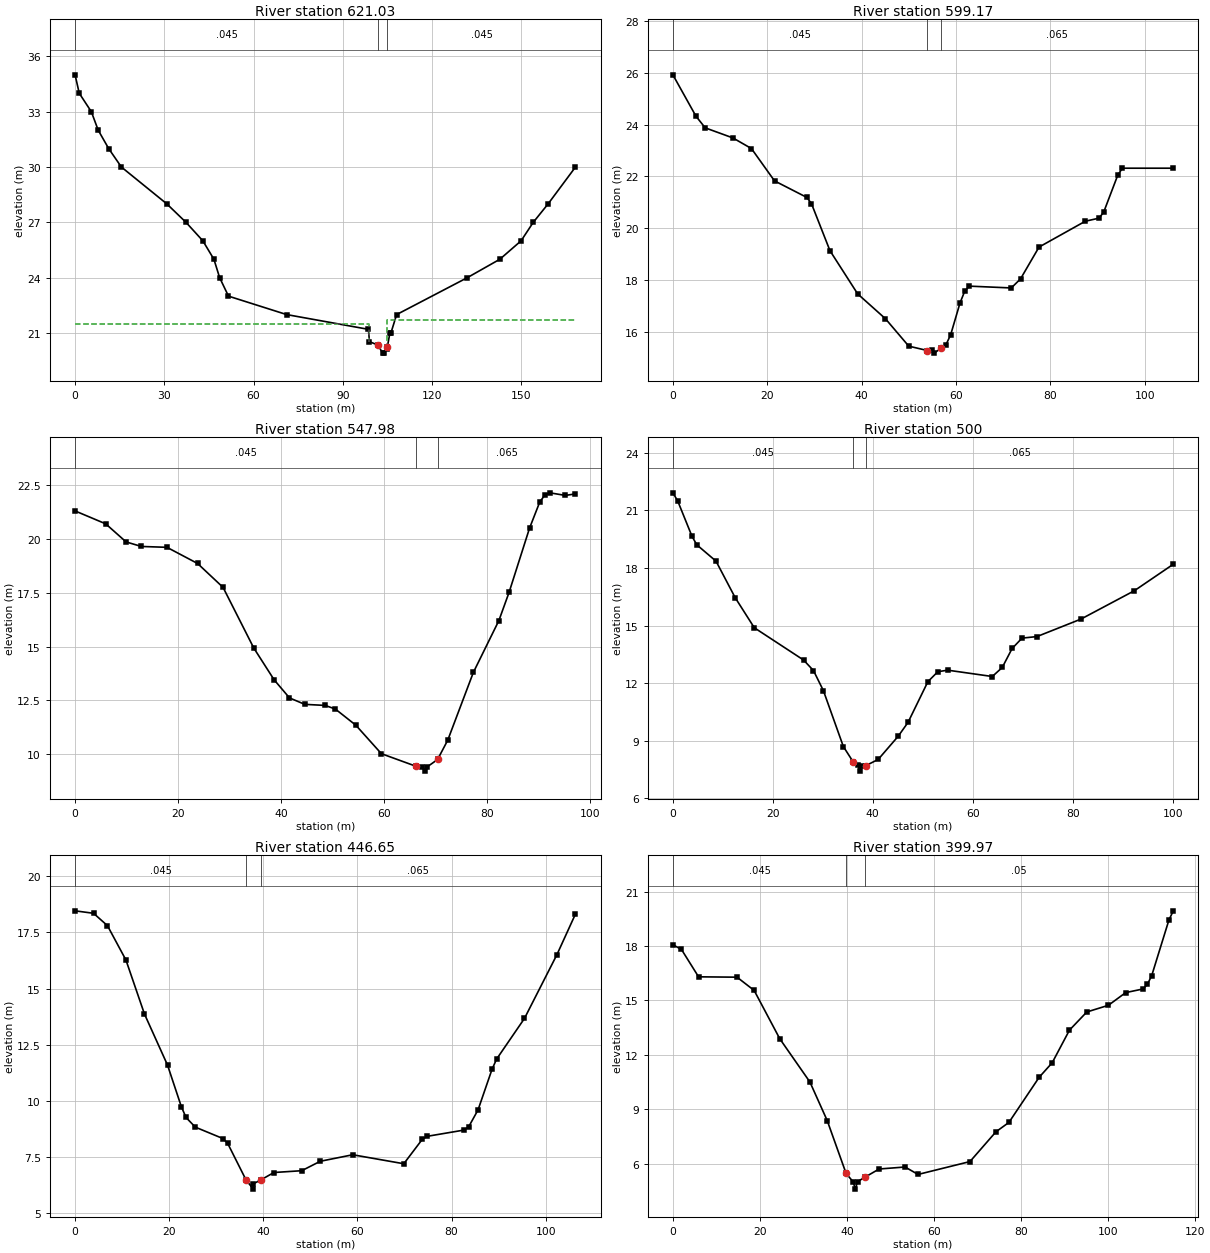
Type RM Length L Ch R = 1 ,621.03  ,63.06,44.67,36.85
Node Photo=..\..\..\Corner Brook\Windshield Survey\CB photos\P1000567.JPG
XS GIS Cut Line= 4
340161.8344726565424677.12811279340224.0656738285424678.33331299
340277.1311035165424677.61010742340325.854919434 5424657.1217041
#Sta/Elev= 29
       0      35    1.41      34    5.47      33    7.77      32    11.3      31
   15.57      30   30.85      28   37.29      27   42.94      26   46.66      25
   48.59      24   51.56      23   71.11      22    98.6    21.2   98.93   20.53
  101.78   20.35  103.37   19.91  103.83   19.91  104.94   20.11  104.96   20.26
   105.8      21  106.16   21.01  108.06      22   131.8      24  142.75      25
  149.89      26  153.97      27  158.96      28  168.17      30
#Mann= 3 , 0 , 0
       0    .045       0  101.78    .035       0  104.96    .045       0
#XS Ineff= 2 , 0
       0   98.93    21.5  104.94       0    21.7
Permanent Ineff=
       F       F
Bank Sta=101.78,104.96
XS Rating Curve= 0 ,0
Exp/Cntr=0.5,0.3

Type RM Length L Ch R = 1 ,599.17  ,42.47,51.19,56.77
XS GIS Cut Line= 4
340317.2623291025424702.84130859340274.1273193365424711.74090576
340253.8461303715424730.52868652340221.7706909185424718.29608154
#Sta/Elev= 30
       0   25.93    4.89   24.33    6.85   23.88   12.72   23.49   16.64   23.08
   21.53   21.83   28.38   21.19   29.36   20.95   33.28   19.13   39.15   17.46
   45.03    16.5   49.97   15.44   53.92   15.27    54.9   15.29   55.35   15.17
   56.77   15.35   57.87    15.5   58.85   15.88   60.83   17.11   61.82   17.56
    62.8   17.76   71.69   17.69   73.65   18.04   77.57   19.27   87.38   20.27
   90.33   20.39   91.31   20.64   94.25   22.05   95.23   22.32  106.02   22.32
#Mann= 3 , 0 , 0
       0    .045       0   53.92    .035       0   56.77    .065       0
Bank Sta=53.92,56.77
XS Rating Curve= 0 ,0
Exp/Cntr=0.3,0.1

Type RM Length L Ch R = 1 ,547.98  ,42.14,47.99,52.35
XS GIS Cut Line= 3
340227.9702758795424736.13427734340266.0335083015424752.95751953
340321.0383300785424760.54431152
#Sta/Elev= 30
       0    21.3    5.95    20.7    9.91   19.86   12.88   19.65   17.84   19.61
   23.78   18.86   28.73   17.75   34.68   14.94   38.64   13.46   41.62   12.62
   44.59   12.32   48.56   12.27   50.54    12.1   54.51   11.35   59.46   10.03
   66.24    9.44    67.4    9.41   67.96    9.22   68.31    9.41   70.37    9.76
   72.35   10.66   77.31    13.8   82.27   16.21   84.25   17.52   88.22    20.5
    90.2   21.71   91.19   22.04   92.18   22.14   95.16   22.02   97.14   22.09
#Mann= 3 , 0 , 0
       0    .045       0   66.24    .035       0   70.37    .065       0
Bank Sta=66.24,70.37
XS Rating Curve= 0 ,0
Exp/Cntr=0.3,0.1

Type RM Length L Ch R = 1 ,500     ,60.5,53.35,49.24
XS GIS Cut Line= 5
340226.2656860355424766.46551514340243.7484741215424774.32269287
340261.7570800785424795.61627197340288.4268798835424803.34887695
340312.2490844735424794.80908203
#Sta/Elev= 30
       0   21.92     .96    21.5    3.83   19.65    4.79   19.21    8.63   18.36
   12.46   16.46   16.29   14.89   26.14   13.21   28.13   12.66   30.12   11.61
   34.11     8.7    36.1    7.89    37.1    7.72   37.37    7.42    37.7     7.7
   38.64    7.71   41.08    8.03   45.06    9.23   47.05    9.96   51.02   12.08
   53.01    12.6   54.99   12.68   63.91   12.35    65.9   12.82   67.88   13.81
   69.86   14.35   72.84   14.43   81.64   15.34   92.34   16.82  100.13    18.2
#Mann= 3 , 0 , 0
       0    .045       0    36.1    .035       0   38.64    .065       0
Bank Sta=36.1,38.64
XS Rating Curve= 0 ,0
Exp/Cntr=0.3,0.1

Type RM Length L Ch R = 1 ,446.65  ,40.57,46.68,45.89
XS GIS Cut Line= 3
340202.8817138675424846.96569824340246.3759155275424834.67572021
340307.1436767585424841.38751221
#Sta/Elev= 30
       0   18.46    3.93   18.35    6.88    17.8   10.81   16.27   14.74   13.87
   19.65   11.59    22.6    9.73   23.58    9.26   25.55    8.83   31.44    8.32
   32.42    8.11   36.35    6.47   37.89    6.07   37.91    6.31   39.47    6.48
   42.25    6.81   48.16    6.89    52.1    7.31      59     7.6   69.85     7.2
   73.79    8.29   74.78    8.42   82.67     8.7   83.65    8.85   85.63     9.6
   88.59    11.4   89.57   11.86   95.49   13.67  102.39   16.51  106.33   18.32
#Mann= 3 , 0 , 0
       0    .045       0   36.35    .035       0   39.47    .065       0
Bank Sta=36.35,39.47
XS Rating Curve= 0 ,0
Exp/Cntr=0.3,0.1

Type RM Length L Ch R = 1 ,399.97  ,43.09,50,61.08
XS GIS Cut Line= 3
340207.7009277345424858.61791992 340232.363281255424872.90429688
340316.6909179695424892.06091309
#Sta/Elev= 30
       0   18.07    1.97   17.81     5.9    16.3   14.74   16.28   18.67   15.55
   24.57   12.88   31.48    10.5   35.46    8.37   39.79    5.46   41.42    4.99
   41.93    4.59   42.42       5   44.06    5.24   47.39     5.7   53.35    5.81
   56.33     5.4   68.26    6.11   74.22    7.75   77.21    8.27   84.16   10.76
   87.15   11.56   91.12   13.36    95.1   14.36  100.07   14.73  104.04   15.43
  108.02   15.63  109.01   15.88  110.01   16.36  113.98   19.44  114.98   19.94
#Mann= 3 , 0 , 0
       0    .045       0   39.79    .035       0   44.06     .05       0
Bank Sta=39.79,44.06
XS Rating Curve= 0 ,0
Exp/Cntr=0.3,0.1

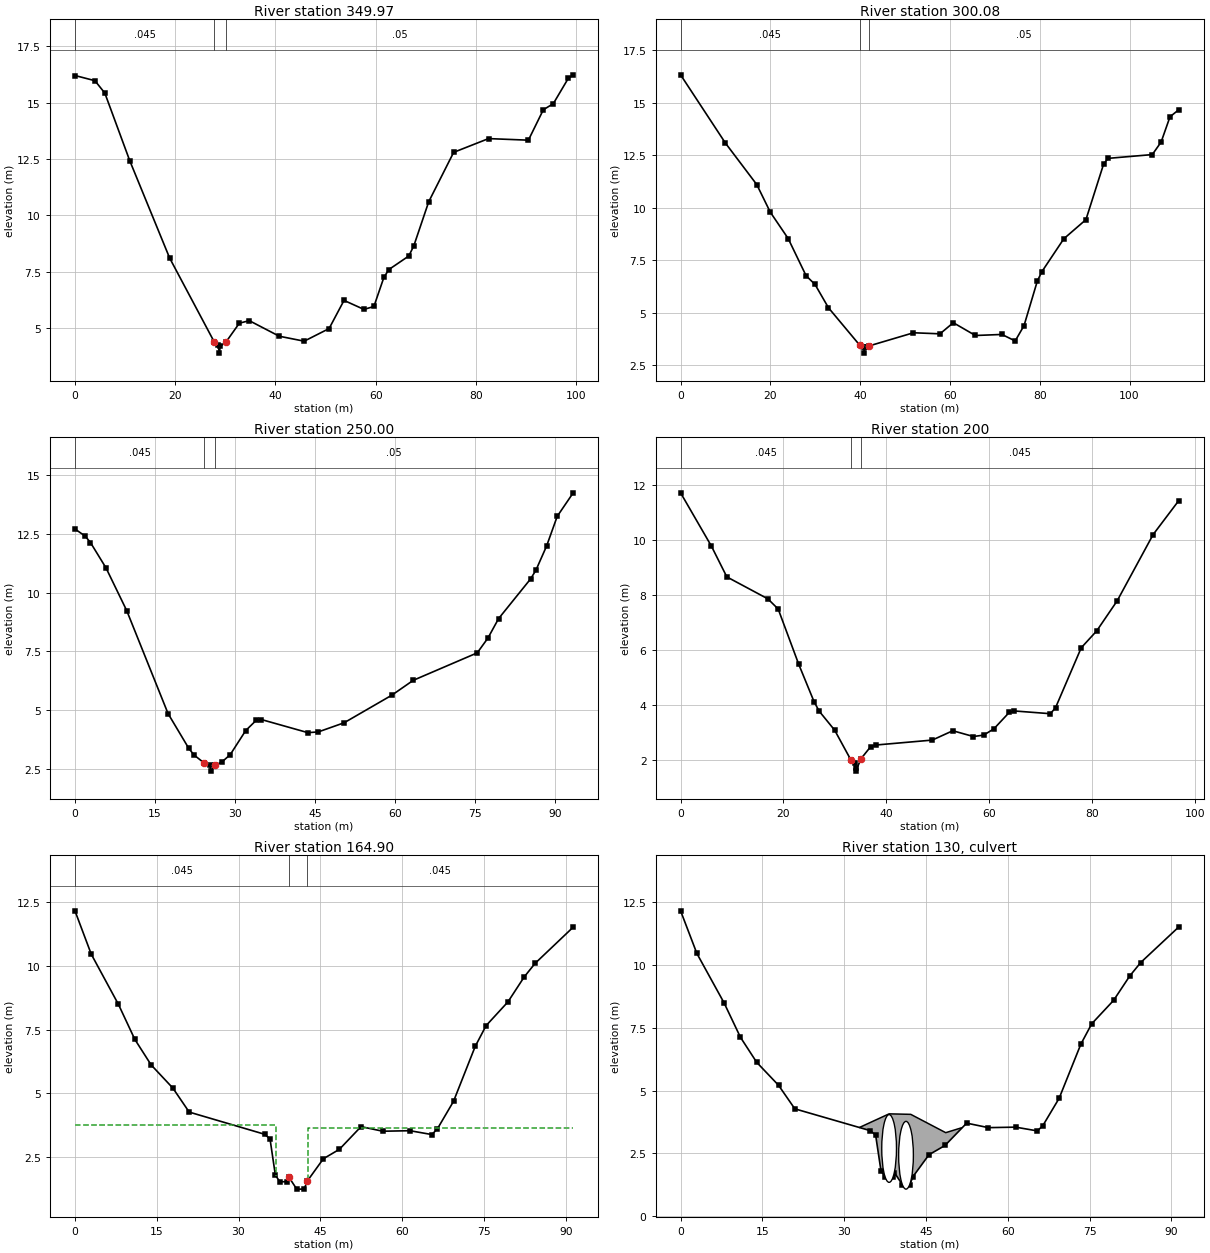
Type RM Length L Ch R = 1 ,349.97  ,46.29,49.89,52.66
XS GIS Cut Line= 2
340196.1428833015424878.69488525340245.4359130865424965.01690674
#Sta/Elev= 30
       0   16.21    3.98   15.98    5.96   15.43   10.93   12.43   18.89    8.11
   27.83    4.37   28.56    4.24   28.83    3.89   28.96    4.19   30.09    4.37
    32.8    5.22   34.79    5.33   40.76    4.64   45.73    4.42    50.7    4.98
   53.68    6.23   57.65    5.83   59.64    5.96   61.63    7.25   62.63     7.6
    66.6     8.2    67.6    8.65   70.58   10.61   75.55    12.8   82.51   13.41
   90.46   13.34   93.44   14.69   95.43   14.96   98.41   16.08    99.4   16.24
#Mann= 3 , 0 , 0
       0    .045       0   27.83    .035       0   30.09     .05       0
Bank Sta=27.83,30.09
XS Rating Curve= 0 ,0
Exp/Cntr=0.3,0.1

Type RM Length L Ch R = 1 ,300.08  ,52.99,50.08,47.27
XS GIS Cut Line= 3
340168.6113281255424883.23352051340166.5836791995424932.10668945
340196.0034790045424986.74291992
#Sta/Elev= 30
       0   16.33    9.98   13.08   16.97    11.1   19.97    9.79   23.96    8.53
   27.95    6.76   29.95    6.34   32.94    5.23   39.93    3.44   40.93    3.37
   40.93    3.07      41    3.37   41.93    3.41   51.87    4.04   57.78    3.99
   60.74    4.52   65.66    3.91   71.57    3.96   74.52    3.65   76.49    4.38
   79.45     6.5   80.43    6.94   85.36    8.52   90.28    9.43   94.22   12.08
   95.21   12.35  105.06   12.53  107.03   13.13     109   14.33  110.97   14.67
#Mann= 3 , 0 , 0
       0    .045       0   39.93    .035       0   41.93     .05       0
Bank Sta=39.93,41.93
XS Rating Curve= 0 ,0
Exp/Cntr=0.3,0.1

Type RM Length L Ch R = 1 ,250.00  ,53.02,50,43.41
XS GIS Cut Line= 4
340120.7506713875424923.58831787 340121.947082525424944.88812256
340134.2816772465424972.31207275340164.1124877935425001.82128906
#Sta/Elev= 30
       0   12.71    1.94    12.4    2.91   12.13    5.82   11.05     9.7    9.23
   17.45    4.84   21.33    3.36    22.3    3.08   24.24    2.73   25.24    2.65
   25.48    2.39   26.24    2.65   27.48    2.77   29.09    3.09      32    4.12
   33.94    4.55   34.91    4.59   43.64    4.03   45.58    4.06   50.43    4.45
    59.4    5.63   63.39    6.26   75.38    7.43   77.38    8.06   79.38    8.89
   85.37   10.58   86.37   10.95   88.37   11.98   90.37   13.25   93.36   14.25
#Mann= 3 , 0 , 0
       0    .045       0   24.24    .035       0   26.24     .05       0
Bank Sta=24.24,26.24
XS Rating Curve= 0 ,0
Exp/Cntr=0.3,0.1

Type RM Length L Ch R = 1 ,200     ,41.59,35.1,14.44
XS GIS Cut Line= 3
340055.2227172855424951.01568604340108.0842895515424998.23651123
340128.5507202155425014.19708252
#Sta/Elev= 30
       0   11.73    5.99    9.79    8.99    8.67   16.97    7.87   18.97     7.5
   22.96    5.49   25.96    4.12   26.95    3.78   29.95    3.09   33.06    2.02
   33.94     1.9   34.06     1.7   34.06     1.6   35.06    2.05   36.94    2.49
   37.94    2.55   48.92    2.73   52.91    3.07    56.9    2.86    58.9    2.91
    60.9    3.14   63.89    3.74   64.89    3.79   71.88    3.69   72.88    3.91
   77.87    6.09   80.86     6.7   84.86     7.8   91.84   10.21   96.84   11.45
#Mann= 3 , 0 , 0
       0    .045       0   33.06    .035       0   35.06    .045       0
Bank Sta=33.06,35.06
XS Rating Curve= 0 ,0
Exp/Cntr=0.3,0.1

Type RM Length L Ch R = 1 ,164.90  ,16.7,16,13.4
Node Photo=..\..\..\Corner Brook\Windshield Survey\CB photos\P1000564.JPG
XS GIS Cut Line= 4
340042.8353271485425011.87188721340070.7041015635425009.88110352
340089.5620727545424999.50390625340128.1572875985425015.82373047
#Sta/Elev= 30
       0   12.16    2.99   10.46    7.98    8.49   10.98    7.12   13.97    6.12
   17.96    5.21   20.95    4.27   34.79     3.4   35.77    3.22   36.75     1.8
   37.57    1.54   38.92    1.54    39.2    1.73   40.67    1.25   42.02    1.25
   42.62    1.57   45.55    2.44   48.49    2.81   52.46     3.7   56.45    3.52
   61.44    3.54   65.43    3.39   66.43     3.6   69.42    4.69   73.41    6.85
    75.4    7.66    79.4    8.59   82.39    9.57   84.38    10.1   91.37   11.52
#Mann= 3 , 0 , 0
       0    .045       0    39.2    .035       0   42.62    .045       0
#XS Ineff= 2 , 0
       0   36.89    3.75    42.7       0    3.65
Permanent Ineff=
       F       F
Bank Sta=39.2,42.62
XS Rating Curve= 0 ,0
Exp/Cntr=0.5,0.3

Type RM Length L Ch R = 2 ,130     ,,,
Node Photo=..\..\..\Corner Brook\Windshield Survey\CB photos\P1000561.JPG
BEGIN DESCRIPTION:
Bartlett's Avenue(1101-1)
END DESCRIPTION:
Bridge Culvert--1,0,-1,-1, 0
Deck Dist Width WeirC Skew NumUp NumDn MinLoCord MaxHiCord MaxSubmerge Is_Ogee
4.3,9,1.57,0, 5, 11, 3.62, , 0.98, 0, 1,1,,
   32.83   38.24   42.21   48.62   51.46
    3.53    4.07    4.05    3.32    3.51
                                        
   21.62   23.63   29.41    34.5   37.15   38.55   39.57    42.4   45.81   63.75
   74.09
       4    3.86    3.62    3.66    4.12       4       4    3.93    3.95       4
       4
                                                                                
        
BR Coef=-1 , 0 , 0 ,, 0 ,,,0.8,-1,,0,
WSPro=,,,, 1 ,,,, 0 ,,,, 0 ,,,,-1 ,-1 ,-1 , 0 , 0 , 0 , 0 , 0
Culvert=1,2.7,,11.6,0.032,0.9,1,2,3,1.34,38.24,1.24,57,Culvert #1  , 0 ,2.4
Culvert Bottom n=0.035
Culvert Bottom Depth=0.2
Culvert Depth Blocked=0.2
Culvert=1,2.7,,11.6,0.032,0.9,1,2,3,1.07,41.34,0.94,59.9,Culvert #2  , 0 ,2.4
Culvert Bottom n=0.035
Culvert Bottom Depth=0.17
Culvert Depth Blocked=0.17
BC Design=,, 0 ,, 0 ,,,,,,
BC Use User HTab Curves=0
BC User HTab FreeFlow(D)= 0

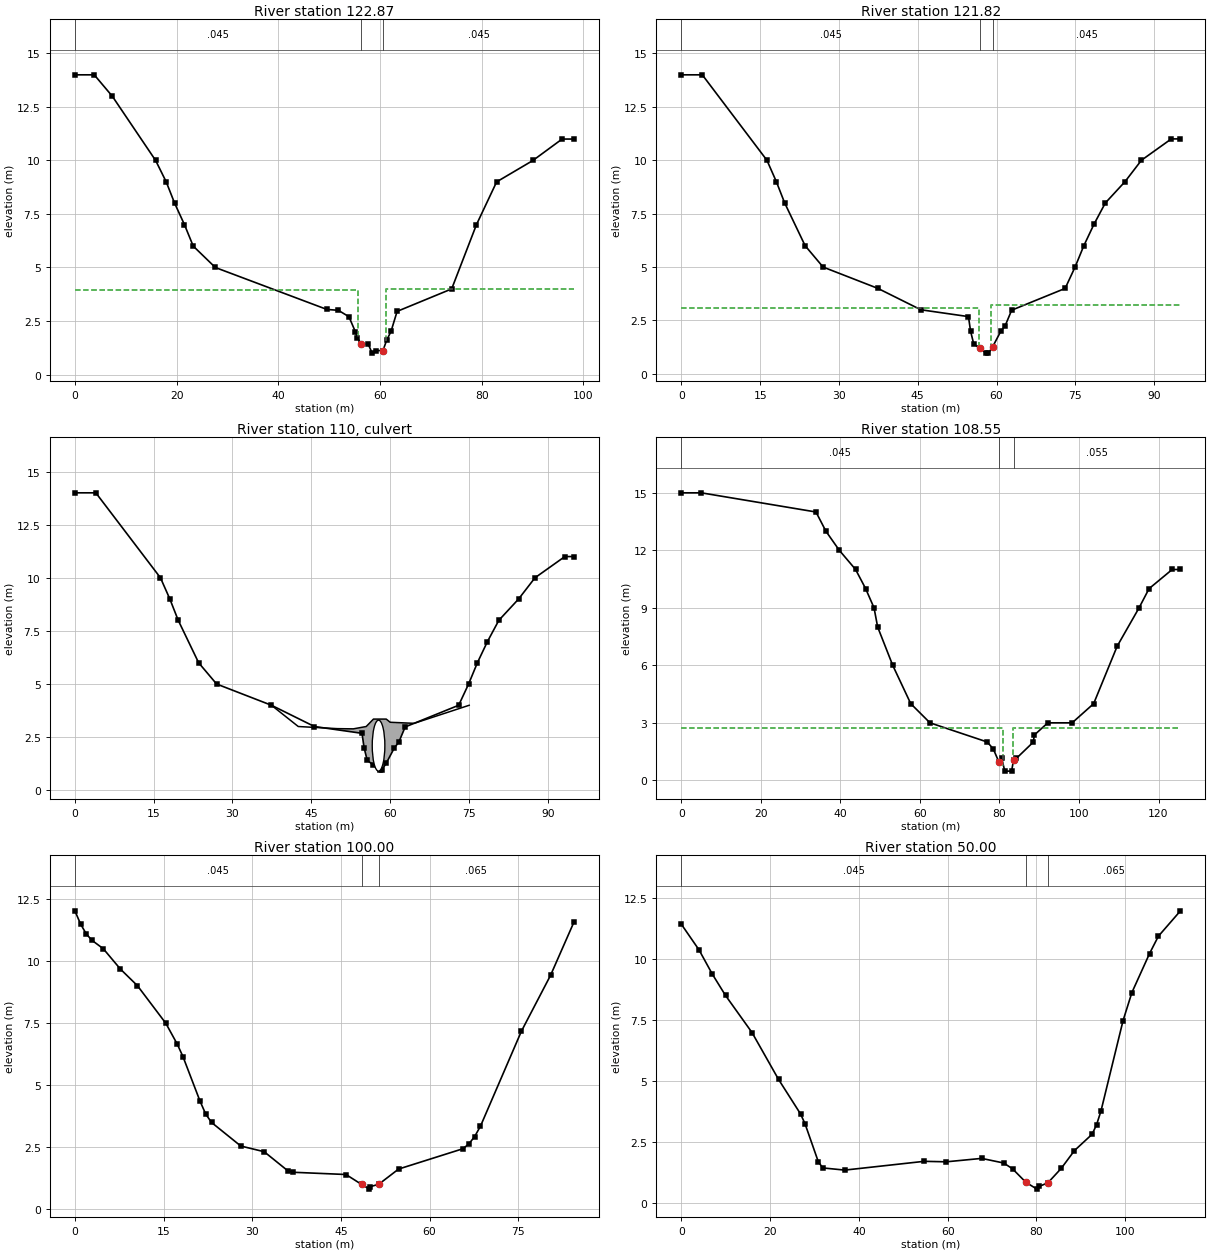
Type RM Length L Ch R = 1 ,122.87  ,3.2,2.2,2.7
Node Photo=..\..\..\Corner Brook\Windshield Survey\CB photos\P1000560.JPG
XS GIS Cut Line= 6
      340039.015     5425048.775      340048.069     5425044.251
      340072.358     5425027.922      340093.557     5425015.123
      340095.544     5425014.241      340127.303     5425016.112
#Sta/Elev= 28
       0      14    3.81      14    7.36      13   15.88      10   17.96       9
   19.62       8   21.55       7   23.27       6   27.62       5   49.56    3.04
   51.81       3   53.89     2.7   55.15       2   55.55    1.71   56.32    1.42
   57.68    1.42   58.45       1   59.23    1.12   60.58    1.12    61.3     1.6
   62.17    2.02   63.36    2.95   74.09       4   78.96       7   82.93       9
   90.07      10    95.8      11   98.14      11
#Mann= 3 , 0 , 0
       0    .045       0   56.32    .035       0   60.58    .045       0
#XS Ineff= 2 , 0
       0   55.65    3.95   61.25       0       4
Permanent Ineff=
       F       F
Bank Sta=56.32,60.58
XS Rating Curve= 0 ,0
Exp/Cntr=0.5,0.3

Type RM Length L Ch R = 1 ,121.82  ,20.4,21.4,13
Node Photo=..\..\..\Corner Brook\Windshield Survey\CB photos\P1000560.JPG
XS GIS Cut Line= 6
      340040.892     5425050.981      340044.756     5425050.209
      340074.235      5425030.68      340094.771     5425016.668
      340094.771     5425016.668      340125.575     5425018.102
#Sta/Elev= 28
       0      14    3.99      14   16.29      10   18.08       9   19.67       8
   23.56       6   26.98       5   37.42       4   45.59       3   54.65    2.68
   55.05       2   55.64    1.41   56.79    1.19   58.03     .97   58.46     .97
   59.26    1.27   60.82       2   61.65    2.26   62.87    2.98   73.05       4
   74.94       5   76.61       6   78.53       7    80.7       8   84.45       9
   87.57      10   93.26      11      95      11
#Mann= 3 , 0 , 0
       0    .045       0   56.79    .035       0   59.26    .045       0
#XS Ineff= 2 , 0
       0    56.6     3.1      59       0     3.2
Permanent Ineff=
       F       F
Bank Sta=56.79,59.26
XS Rating Curve= 0 ,0
Exp/Cntr=0.5,0.3

Type RM Length L Ch R = 2 ,110     ,,,
Node Photo=..\..\..\Corner Brook\Windshield Survey\CB photos\P1000557.JPG
BEGIN DESCRIPTION:
Bartlett's Avenue (1101)
END DESCRIPTION:
Bridge Culvert--1,0,-1,-1, 0
Deck Dist Width WeirC Skew NumUp NumDn MinLoCord MaxHiCord MaxSubmerge Is_Ogee
5.7,7.6,1.67,0, 10, 10, 2.89, , 0.98, 0, 1,1,,
   37.42   42.52   49.94      53   55.45   56.83   59.26   60.02   64.58   75.05
       4       3     2.9    2.89       3    3.35    3.35     3.2    3.15       4
                                                                                
   62.53   70.12   72.28   74.03   74.82    77.1    79.1   81.07   87.02   92.16
       3    2.64    2.88       3    3.02    3.06     3.2    3.12    3.15       3
                                                                                
BR Coef=-1 , 0 , 0 ,, 0 ,,,0.8,-1,,0,
WSPro=,,,, 1 ,,,, 0 ,,,, 0 ,,,,-1 ,-1 ,-1 , 0 , 0 , 0 , 0 , 0
Culvert=1,2.4,,15.4,0.032,0.9,1,1,1,0.9,57.8,0.13,82.2,Culvert #1  , 0 ,2.2
Culvert Bottom n=0.035
Culvert Bottom Depth=0.35
BC Design=,, 0 ,, 0 ,,,,,,
BC Use User HTab Curves=0
BC User HTab FreeFlow(D)= 0

Type RM Length L Ch R = 1 ,108.55  ,21.3,24.9,35.5
Node Photo=..\..\..\Corner Brook\Windshield Survey\CB photos\P1000558.JPG
XS GIS Cut Line= 5
       340026.34     5425059.998      340058.661      5425064.56
       340102.61      5425037.08      340103.714     5425018.102
      340125.735     5425018.884
#Sta/Elev= 30
       0      15    5.02      15   33.86      14   36.35      13   39.73      12
   43.82      11   46.35      10   48.46       9   49.37       8   53.16       6
   57.69       4   62.53       3   76.93       2   78.44    1.64   79.84     .97
   80.56    1.14   81.35     .48   83.05     .48   83.56    1.07   84.28    1.15
   88.54       2   88.75    2.36   92.16       3   98.28       3  103.69       4
  109.61       7  115.11       9  117.62      10  123.44      11  125.52      11
#Mann= 3 , 0 , 0
       0    .045       0   79.84    .035       0   83.56    .055       0
#XS Ineff= 2 , 0
       0      81    2.75    83.4       0    2.75
Permanent Ineff=
       F       F
Bank Sta=79.84,83.56
XS Rating Curve= 0 ,0
Exp/Cntr=0.5,0.3

Type RM Length L Ch R = 1 ,100.00  ,51.01,50,48.15
XS GIS Cut Line= 3
340064.700927734 5425069.0994873340086.762878418 5425067.3994751
340146.9454956055425051.29589844
#Sta/Elev= 30
       0   12.02     .96   11.49    1.92   11.09    2.89   10.83    4.81   10.49
     7.7    9.67   10.58       9   15.39    7.48   17.32    6.64   18.28    6.14
   21.17    4.34   22.13    3.82   23.12    3.48   28.06    2.53   32.02     2.3
   35.97    1.54   36.96    1.47   45.86    1.38    48.5     .98   49.82     .79
   49.94     .89   51.37     .98   54.76     1.6   65.64    2.42   66.63    2.61
   67.62    2.91   68.61    3.33   75.53    7.16   80.47    9.42   84.43   11.57
#Mann= 3 , 0 , 0
       0    .045       0    48.5    .035       0   51.37    .065       0
Bank Sta=48.5,51.37
XS Rating Curve= 0 ,0
Exp/Cntr=0.3,0.1

Type RM Length L Ch R = 1 ,50.00   ,42.7,50,62.04
XS GIS Cut Line= 3
 340064.588073735425089.43432617340111.1361083985425114.20391846
340166.4172973635425091.65087891
#Sta/Elev= 30
       0   11.42    3.98   10.37    6.96    9.38    9.95     8.5   15.92    6.98
   21.89    5.06   26.86    3.64   27.86    3.24   30.84    1.69   31.84    1.43
   36.81    1.34   54.72     1.7   59.69    1.68   67.65    1.82   72.63    1.63
   74.62    1.39   77.61     .84    80.1     .56   80.59     .67   82.58     .82
   85.57    1.41   88.55    2.14   92.53    2.81   93.53     3.2   94.52    3.76
    99.5    7.47  101.49    8.62  105.47   10.22  107.46   10.93  112.43   11.97
#Mann= 3 , 0 , 0
       0    .045       0   77.61    .035       0   82.58    .065       0
Bank Sta=77.61,82.58
XS Rating Curve= 0 ,0
Exp/Cntr=0.3,0.1

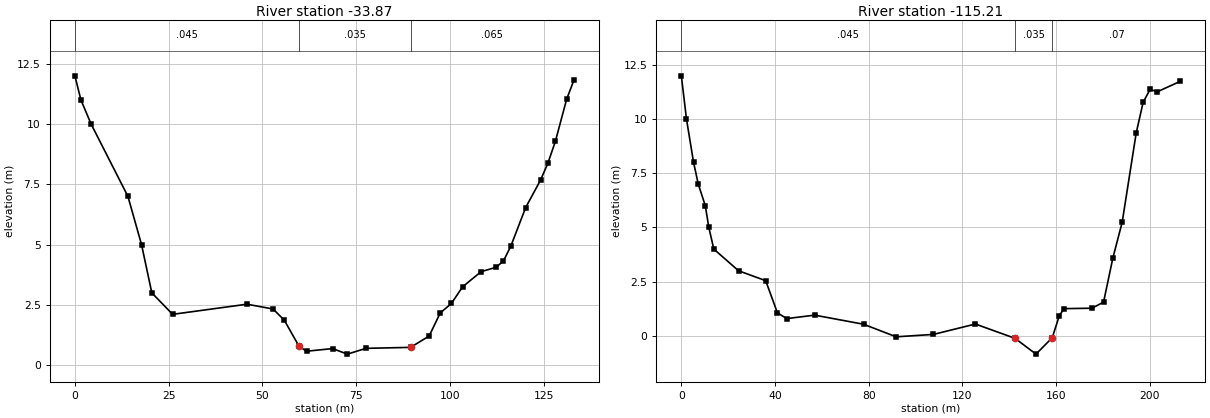
Type RM Length L Ch R = 1 ,-33.87  ,47.21,81.46,53.88
XS GIS Cut Line= 6
      340064.244     5425090.711      340074.824     5425096.472
      340078.531        5425110.      340104.217     5425165.507
       340126.95     5425167.599      340207.414     5425142.789
#Sta/Elev= 30
       0      12    1.61      11    4.33      10   14.15       7   17.78       5
   20.52       3   26.07    2.11   45.92    2.53   52.86    2.33   55.83    1.87
    59.8     .78   61.78     .58   68.71     .69   72.67     .46   77.63      .7
   89.51     .74   94.47    1.21   97.44    2.17  100.41    2.56  103.38    3.25
  108.34    3.88   112.3    4.06  114.28    4.32  116.26    4.94  120.22    6.54
  124.19    7.68  126.17    8.39  128.15    9.29  131.12   11.02   133.1   11.83
#Mann= 3 , 0 , 0
       0    .045       0    59.8    .035       0   89.51    .065       0
Bank Sta=59.8,89.51
XS Rating Curve= 0 ,0
Exp/Cntr=0.3,0.1

Type RM Length L Ch R = 1 ,-115.21 ,0,0,0
XS GIS Cut Line= 6
      340058.242     5425091.305      340059.846     5425109.004
        340066.5        5425114.       340102.03     5425202.577
      340175.315     5425238.447      340238.857     5425154.222
#Sta/Elev= 30
       0      12     2.2      10    5.23       8    7.23       7   10.24       6
   11.74       5   13.87       4   24.43       3   36.04    2.54   41.02    1.06
      45     .79   56.94     .95   77.83     .53   91.76    -.05  107.68     .06
   125.6     .54  142.52    -.12  151.48    -.85  158.44    -.09  161.43     .92
  163.42    1.25  175.37    1.27  180.34    1.55  184.32    3.59   188.3    5.24
  194.28    9.36  197.26   10.78  200.25   11.38  203.23   11.26  213.19   11.75
#Mann= 3 , 0 , 0
       0    .045       0  142.52    .035       0  158.44     .07       0
Bank Sta=142.52,158.44
XS Rating Curve= 0 ,0
Exp/Cntr=0.3,0.1

Chan Stop Cuts=-1
Use User Specified Reach Order=0
Composite Channel Slope=5

--- PetriesBrk_v001.g02 (geometry) ---

Geom Title=PetriesBrook-no below waterline
Program Version=4.10

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
River Reach=PetriesB        ,TR002

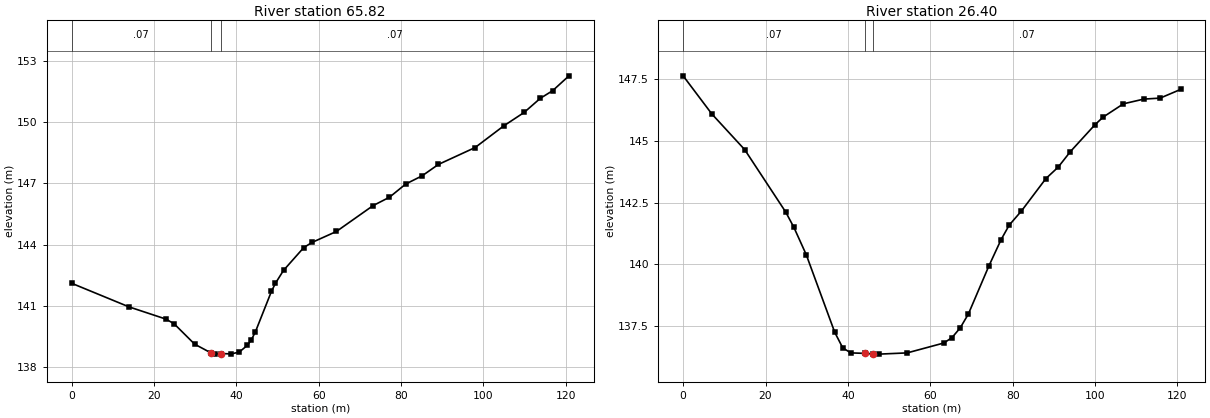
Type RM Length L Ch R = 1 ,65.82   ,40.91,39.42,39.37
XS GIS Cut Line= 4
340073.6801147465422710.47229004340108.5366821295422710.47229004
340123.9555053715422698.47290039340117.2152709965422632.45147705
#Sta/Elev= 30
       0   142.1   13.94  140.94   22.91  140.34    24.9  140.11   29.88  139.11
   33.86  138.68   34.86  138.62   36.28  138.65   38.76  138.63   40.72  138.72
   42.67  139.05   43.65  139.32   44.63  139.71   48.53   141.7   49.51   142.1
   51.46  142.73   56.38  143.85   58.36   144.1    64.3  144.64   73.21  145.91
   77.18  146.32   81.14  146.97    85.1  147.37   89.06  147.93   97.98  148.76
  104.91  149.82  109.86  150.48  113.83  151.18   116.8  151.55  120.76  152.28
#Mann= 3 , 0 , 0
       0     .07       0   33.86     .04       0   36.28     .07       0
Bank Sta=33.86,36.28
XS Rating Curve= 0 ,0
Exp/Cntr=0.3,0.1

Type RM Length L Ch R = 1 ,26.40   ,26.39,26.4,26.39
XS GIS Cut Line= 4
340096.9918823245422739.31469727340131.8485107425422739.31469727
340147.2672729495422727.31530762340140.5270996095422661.29388428
#Sta/Elev= 30
       0  147.62    6.97  146.08   14.94  144.64    24.9  142.12   26.89   141.5
   29.88   140.4   36.81  137.26   38.76  136.63   40.72  136.43   44.17  136.41
   46.17  136.39   47.56  136.38   54.39  136.43   63.31  136.83   65.29  137.05
   67.27  137.44   69.25     138    74.2  139.93   77.18     141   79.16  141.59
   82.13  142.16   88.07  143.47   91.04  143.93   94.02  144.56   99.96  145.64
  101.94  145.95  106.89  146.49  111.84  146.68  115.81  146.72  120.76  147.07
#Mann= 3 , 0 , 0
       0     .07       0   44.17     .04       0   46.17     .07       0
Bank Sta=44.17,46.17
XS Rating Curve= 0 ,0
Exp/Cntr=0.3,0.1

River Reach=PetriesB        ,TR003

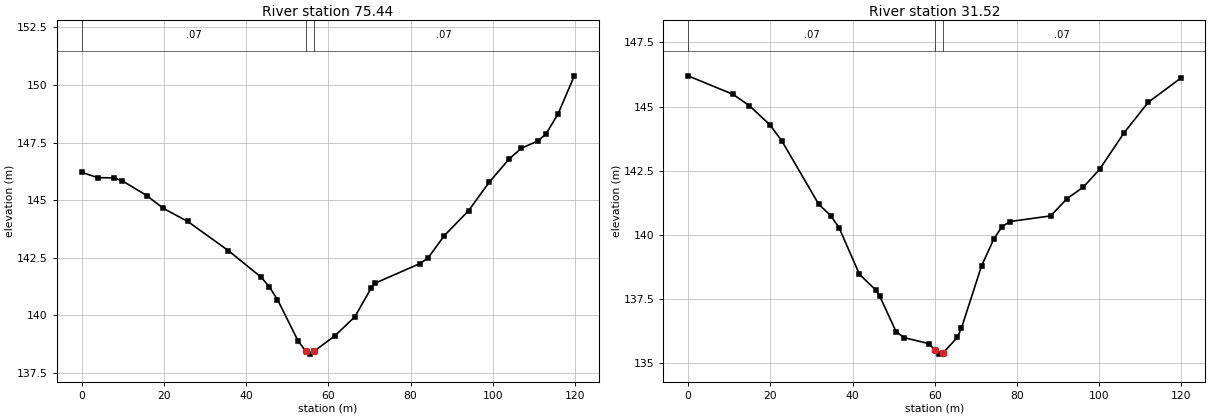
Type RM Length L Ch R = 1 ,75.44   ,44.72,44.75,44.78
XS GIS Cut Line= 3
340174.7932739265422633.26312256340180.9556884775422688.50531006
340244.9166870125422694.58850098
#Sta/Elev= 30
       0  146.21    3.97  145.98    7.94  145.97    9.93  145.84   15.88   145.2
   19.85  144.65   25.81  144.08   35.73  142.81   43.67  141.66   45.66  141.24
   47.64  140.69   52.61  138.91   54.49  138.45   55.53  138.32   56.57  138.45
   61.52   139.1   66.46  139.94   70.41  141.18    71.4   141.4   82.27  142.25
   84.25  142.49    88.2  143.46   94.13  144.55   99.08  145.77  104.02   146.8
  106.98  147.26  110.94  147.57  112.92  147.87  115.88  148.75  119.83   150.4
#Mann= 3 , 0 , 0
       0     .07       0   54.49     .04       0   56.57     .07       0
Bank Sta=54.49,56.57
XS Rating Curve= 0 ,0
Exp/Cntr=0.3,0.1

Type RM Length L Ch R = 1 ,31.52   ,31.52,31.52,31.52
XS GIS Cut Line= 3
340150.9263305665422670.14807129340157.0886840825422725.39031982
340221.0496826175422731.47351074
#Sta/Elev= 30
       0   146.2   10.92  145.48   14.89  145.04   19.85   144.3   22.83  143.66
   31.76   141.2   34.74  140.74   36.73  140.28   41.69  138.46   45.66  137.85
   46.65   137.6   50.62  136.22   52.61  135.99   58.55  135.76   59.99  135.51
   60.99  135.35   61.99  135.39   65.47     136   66.46  136.35    71.4   138.8
   74.37  139.84   76.34  140.32   78.32  140.52    88.2  140.74   92.16  141.41
   96.11  141.86  100.07  142.55     106  143.97  111.93  145.17  119.83  146.11
#Mann= 3 , 0 , 0
       0     .07       0   59.99     .04       0   61.99     .07       0
Bank Sta=59.99,61.99
XS Rating Curve= 0 ,0
Exp/Cntr=0.3,0.1

River Reach=PetriesB        ,M002

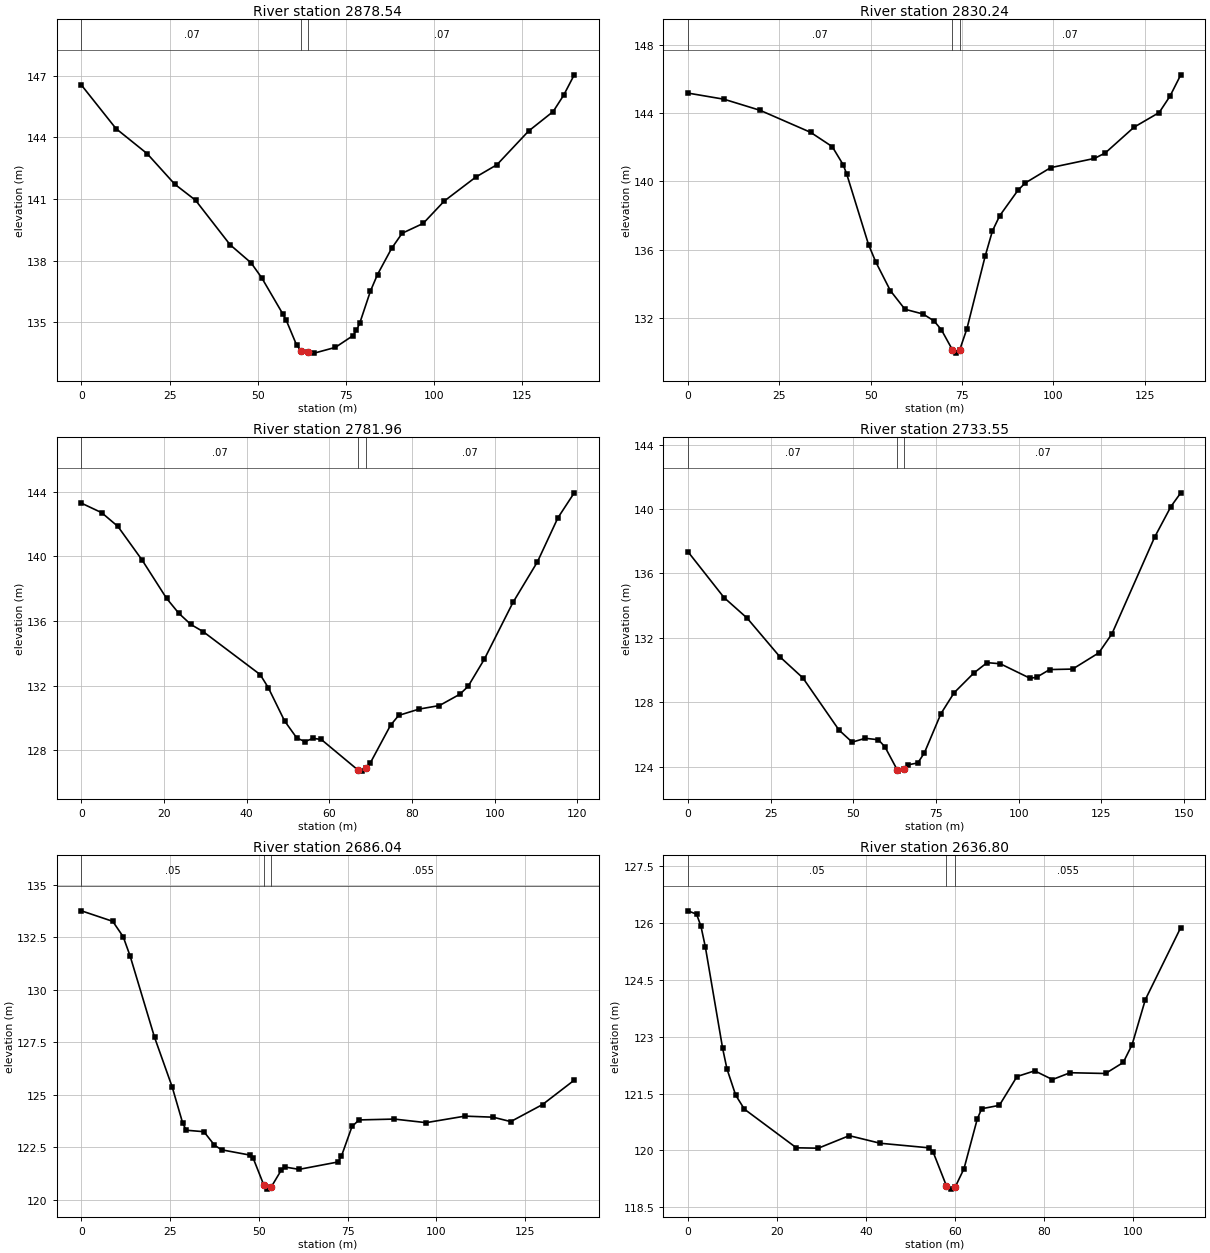
Type RM Length L Ch R = 1 ,2878.54 ,50.79,48.29,38.58
XS GIS Cut Line= 3
340090.1920776375422759.60351563340134.0516967775422764.35968018
340228.7479248055422751.03912354
#Sta/Elev= 30
       0  146.55     9.8  144.43   18.63  143.21   26.47  141.72   32.35  140.94
   42.16  138.77    48.1  137.89   51.09  137.17   57.07  135.41   58.06   135.1
   61.05  133.87   62.35   133.6   64.39  133.54   66.03  133.49   72.01  133.77
   76.99  134.34   77.99   134.6   78.98  134.98   81.97  136.52   83.96  137.32
   87.95  138.59   90.94  139.33   96.91  139.81  102.89   140.9  111.85  142.07
  117.83  142.67   126.8  144.31  133.77  145.26  136.76  146.06  139.75  147.05
#Mann= 3 , 0 , 0
       0     .07       0   62.35     .04       0   64.39     .07       0
Bank Sta=62.35,64.39
XS Rating Curve= 0 ,0
Exp/Cntr=0.3,0.1

Type RM Length L Ch R = 1 ,2830.24 ,43.24,48.28,50.69
XS GIS Cut Line= 4
340130.4509277345422845.89892578340164.290283203 5422818.6519165
340203.3007202155422761.96508789340225.6536865235422758.36230469
#Sta/Elev= 30
       0  145.18    9.87  144.82   19.75  144.17   33.57  142.88    39.5  142.04
   42.46  140.99   43.45  140.44   49.43   136.3   51.42  135.28   55.41   133.6
    59.4  132.51   64.39  132.23   67.38  131.82   69.37  131.31   72.37  130.14
   73.36  129.94   74.37  130.12   76.36  131.37   81.34  135.61   83.34   137.1
   85.33  137.99   90.32  139.48   92.31  139.91   99.29  140.81  111.26  141.35
  114.23  141.67   122.1  143.18  128.99  144.04  131.95     145   134.9  146.25
#Mann= 3 , 0 , 0
       0     .07       0   72.37     .04       0   74.37     .07       0
Bank Sta=72.37,74.37
XS Rating Curve= 0 ,0
Exp/Cntr=0.3,0.1

Type RM Length L Ch R = 1 ,2781.96 ,40.62,48.4,49.83
XS GIS Cut Line= 4
340147.6715087895422850.89367676340174.0516967775422853.05609131
340227.6585083015422819.77868652340242.3358764655422794.01208496
#Sta/Elev= 30
       0  143.29     4.9   142.7    8.82  141.85    14.7  139.76   20.59   137.4
   23.53  136.48   26.47  135.78   29.43  135.34   43.23  132.68    45.2  131.87
   49.14  129.81    52.1  128.75   54.07  128.53   56.04  128.73   58.02  128.66
   66.89  126.77   67.88   126.7   68.89  126.87   69.85  127.19   74.78  129.54
   76.75  130.15   81.68  130.54   86.61  130.76   91.54  131.46   93.52  131.94
   97.47  133.63  104.39  137.14  110.32  139.66  115.26  142.38  119.22  143.93
#Mann= 3 , 0 , 0
       0     .07       0   66.89     .04       0   68.89     .07       0
Bank Sta=66.89,68.89
XS Rating Curve= 0 ,0
Exp/Cntr=0.3,0.1

Type RM Length L Ch R = 1 ,2733.55 ,29.65,21.58,18.67
XS GIS Cut Line= 4
340151.7285156255422874.21551514340221.1448974615422877.53051758
340231.3322753915422844.14208984340250.9962768555422804.12329102
#Sta/Elev= 30
       0  137.35   10.92   134.5   17.87  133.23    27.8  130.82   34.75  129.51
   45.67  126.27   49.64  125.52   53.61  125.76   57.58  125.67   59.57  125.22
   63.29  123.79   63.54  123.72    65.3  123.88   66.52  124.11    69.5  124.23
   71.49  124.86   76.48  127.29   80.47  128.59   86.45  129.82   90.44  130.46
   94.43  130.39  103.41  129.49  105.39  129.55  109.36  130.03  116.29  130.06
  124.22  131.07  128.18  132.25  141.07  138.25  146.02  140.16  148.99  141.01
#Mann= 3 , 0 , 0
       0     .07       0   63.29     .04       0    65.3     .07       0
Bank Sta=63.29,65.3
XS Rating Curve= 0 ,0
Exp/Cntr=0.3,0.1

Type RM Length L Ch R = 1 ,2686.04 ,53.06,49.24,39.42
XS GIS Cut Line= 3
 340194.697326665422947.84069824340209.2700805665422934.73907471
  340309.80468755422870.63409424
#Sta/Elev= 30
       0  133.75    8.82  133.25   11.76  132.52   13.72   131.6   20.59  127.74
   25.56  125.38   28.54  123.65   29.53  123.32    34.5  123.25   37.48  122.61
   39.47  122.39   47.42  122.14   48.41  121.98   51.39  120.71   52.39  120.52
   53.39   120.6   56.36  121.44   57.35  121.57   61.33  121.46   72.26  121.81
   73.25  122.09   76.23   123.5   78.22  123.81   88.16  123.85    97.1  123.68
  108.03  123.99  115.98  123.94  120.94  123.73  129.89  124.54  138.83   125.7
#Mann= 3 , 0 , 0
       0     .05       0   51.39     .04       0   53.39    .055       0
Bank Sta=51.39,53.39
XS Rating Curve= 0 ,0
Exp/Cntr=0.3,0.1

Type RM Length L Ch R = 1 ,2636.80 ,36.51,50.76,54.8
XS GIS Cut Line= 4
340237.9028930665422972.42828369340262.6873168955422963.65447998
 340287.704895025422919.71350098340318.1688842775422905.08270264
#Sta/Elev= 30
       0  126.32    1.95  126.23    2.92  125.91     3.9  125.37    7.79  122.69
    8.76  122.15   10.71  121.46   12.66  121.09   24.34  120.07   29.27  120.06
   36.21  120.39   43.15  120.19   54.05  120.07   55.04  119.96   58.02  119.07
   59.01  118.98   60.02  119.04   61.98  119.52   64.96  120.83   65.95   121.1
   69.92  121.19   73.88  121.95   77.85   122.1   81.83  121.87    85.8  122.05
   93.75  122.03   97.73  122.32   99.72  122.79   102.7  123.98  110.65  125.88
#Mann= 3 , 0 , 0
       0     .05       0   58.02     .04       0   60.02    .055       0
Bank Sta=58.02,60.02
XS Rating Curve= 0 ,0
Exp/Cntr=0.3,0.1

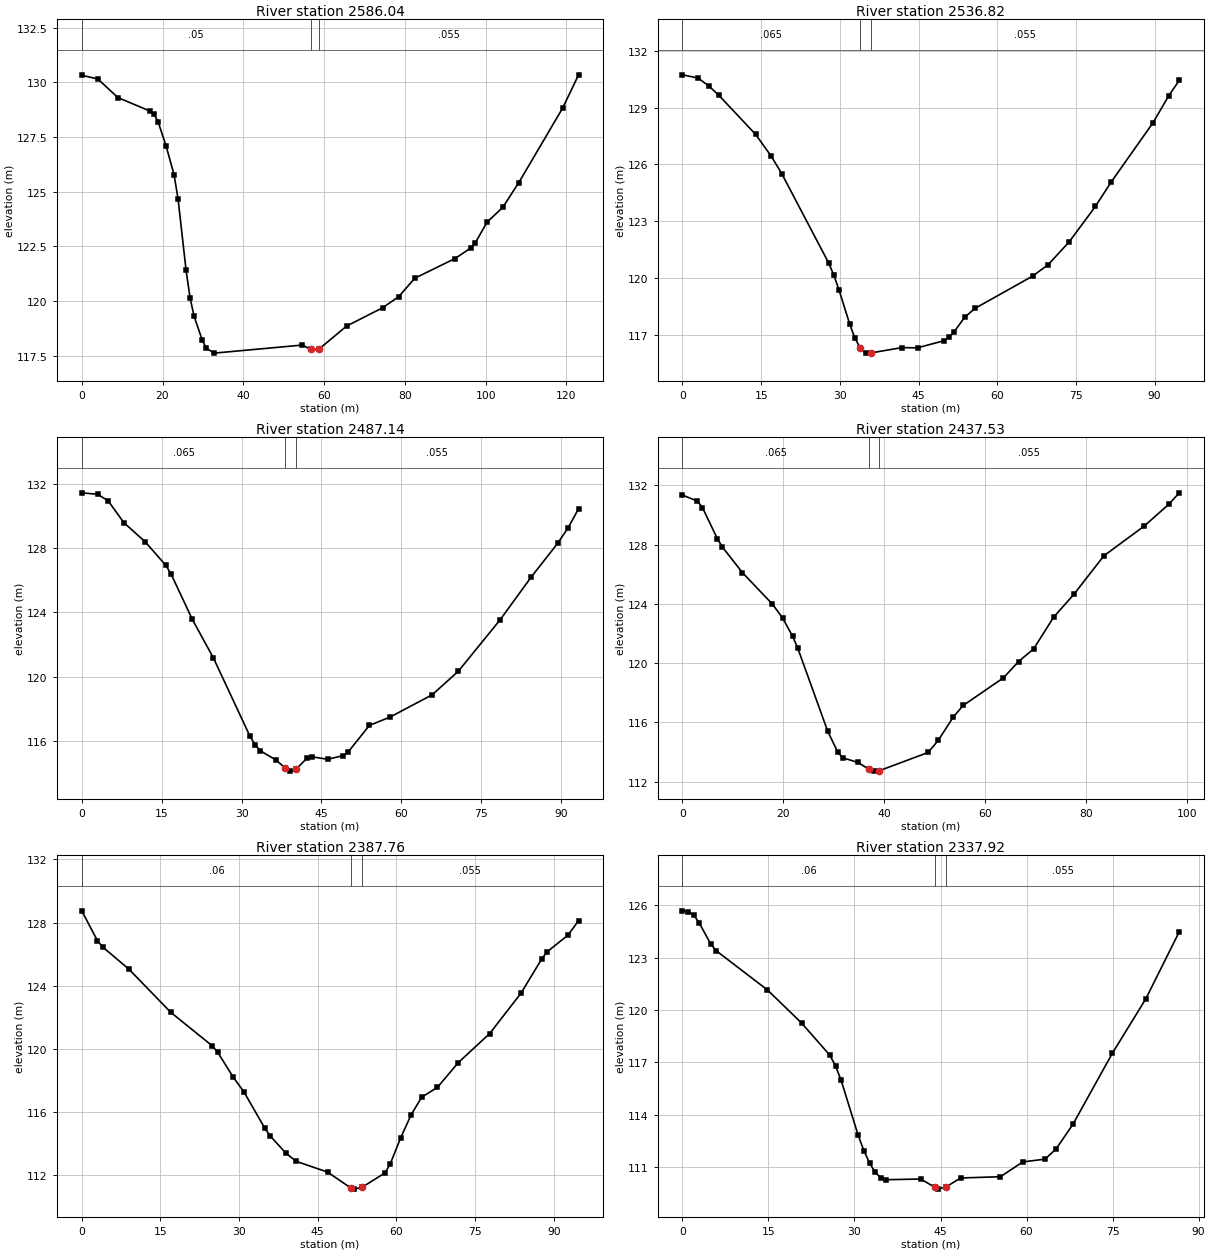
Type RM Length L Ch R = 1 ,2586.04 ,35.46,49.22,44.21
XS GIS Cut Line= 3
340251.1276855475423012.77752686 340329.462707525422956.62487793
340355.900878906 5422953.4440918
#Sta/Elev= 30
       0  130.33    3.97  130.16    8.94  129.31   16.89  128.69   17.89  128.55
   18.88  128.21   20.87   127.1   22.85  125.78   23.85  124.66   25.83   121.4
   26.83  120.13   27.82  119.29   29.81  118.22    30.8  117.84   32.79  117.61
   54.65  117.98   56.64  117.78   58.64  117.78   65.58  118.85   74.52  119.69
    78.5   120.2   82.47  121.04   92.41  121.94   96.38  122.43   97.37  122.64
  100.33   123.6  104.27  124.29  108.22  125.42  119.07  128.83  123.01  130.35
#Mann= 3 , 0 , 0
       0     .05       0   56.64     .04       0   58.64    .055       0
Bank Sta=56.64,58.64
XS Rating Curve= 0 ,0
Exp/Cntr=0.3,0.1

Type RM Length L Ch R = 1 ,2536.82 ,44.82,49.68,52.88
XS GIS Cut Line= 3
340256.894104004 5423031.6060791340315.472900391 5423012.1519165
340348.4030761725423010.62408447
#Sta/Elev= 30
       0  130.73    2.99  130.56    4.98  130.15    6.97  129.64   13.94  127.59
   16.92  126.44   18.92  125.52   27.88   120.8   28.87  120.15   29.87  119.36
   31.86   117.6   32.85  116.85   33.89  116.32   34.89  116.05   35.89  116.06
   41.81  116.34    44.8  116.33   49.78   116.7   50.77  116.88   51.77  117.17
   53.76  117.93   55.75  118.41   66.72  120.11   69.72  120.72   73.71  121.92
   78.71  123.79    81.7  125.07    89.7  128.21   92.69  129.63   94.69  130.44
#Mann= 3 , 0 , 0
       0    .065       0   33.89     .04       0   35.89    .055       0
Bank Sta=33.89,35.89
XS Rating Curve= 0 ,0
Exp/Cntr=0.3,0.1

Type RM Length L Ch R = 1 ,2487.14 ,51.11,49.61,46.45
XS GIS Cut Line= 4
340258.9425048835423063.43048096340286.6007080085423063.98150635
 340308.449096685423068.94232178340351.312927246 5423063.5557251
#Sta/Elev= 30
       0  131.46    2.96  131.37    4.94  130.97     7.9   129.6   11.86  128.42
   15.81  126.93    16.8  126.37   20.75  123.57    24.7  121.17   31.56  116.29
   32.53  115.75   33.51  115.37   36.43   114.8   38.18   114.3   39.18   114.1
   40.18  114.21   42.28   114.9   43.25  114.99   46.17  114.84   49.09  115.07
   50.07  115.32      54  116.95   57.92  117.48   65.78  118.86   70.69  120.33
   78.54  123.54   84.43  126.23   89.34  128.31   91.31  129.28   93.27  130.47
#Mann= 3 , 0 , 0
       0    .065       0   38.18     .04       0   40.18    .055       0
Bank Sta=38.18,40.18
XS Rating Curve= 0 ,0
Exp/Cntr=0.3,0.1

Type RM Length L Ch R = 1 ,2437.53 ,45.79,49.77,51.85
XS GIS Cut Line= 3
340259.7106933595423111.78088379340280.8557128915423117.17089844
340357.0626831055423108.80230713
#Sta/Elev= 30
       0  131.35    2.98  130.94    3.97   130.5    6.94  128.39    7.94  127.83
    11.9  126.11   17.85  123.98   19.84  123.06   21.82  121.83   22.82  121.05
   28.79  115.41   30.78     114   31.78  113.61   34.76   113.3   36.96  112.84
   37.96  112.71   38.96  112.73    48.7  113.97    50.7  114.78   53.68  116.36
   55.67  117.15   63.64  119.01   66.63  120.11   69.61  120.96    73.6  123.11
   77.58  124.64   83.55  127.25   91.52  129.25   96.49  130.75   98.49   131.5
#Mann= 3 , 0 , 0
       0    .065       0   36.96     .04       0   38.96    .055       0
Bank Sta=36.96,38.96
XS Rating Curve= 0 ,0
Exp/Cntr=0.3,0.1

Type RM Length L Ch R = 1 ,2387.76 ,44.11,49.83,53.01
XS GIS Cut Line= 2
340252.7562866215423146.42791748340342.1613159185423177.77490234
#Sta/Elev= 30
       0  128.75    2.99  126.86    3.99  126.46    8.98  125.06   16.95  122.33
   24.93  120.19   25.93  119.79   28.92   118.2   30.92  117.29    34.9  114.99
    35.9  114.51   38.89  113.42   40.89  112.89   46.87  112.21   51.41  111.18
   51.86  111.13   53.41  111.24   57.84  112.16   58.84  112.74   60.83  114.39
   62.83  115.85   64.82  116.95   67.81  117.57    71.8  119.14   77.79  120.98
   83.77  123.54   87.76  125.73   88.76  126.16   92.75  127.22   94.74  128.13
#Mann= 3 , 0 , 0
       0     .06       0   51.41     .04       0   53.41    .055       0
Bank Sta=51.41,53.41
XS Rating Curve= 0 ,0
Exp/Cntr=0.3,0.1

Type RM Length L Ch R = 1 ,2337.92 ,52.32,49.73,33.34
XS GIS Cut Line= 4
340244.5170898445423193.01928711 340279.310485845423200.47088623
340292.0844726565423215.66888428 340323.136718755423218.69268799
#Sta/Elev= 30
       0  125.69     .99  125.65    1.98  125.44    2.97  124.97    4.94  123.78
    5.93  123.39   14.83  121.15   20.76  119.26    25.7  117.41   26.69   116.8
   27.68  115.96   30.64  112.82   31.63  111.94   32.62  111.23   33.61  110.69
   34.59  110.38   35.58  110.27   41.54  110.31      44  109.84   44.52  109.73
      46  109.86   48.49  110.37   55.44  110.44   59.34  111.29   63.24  111.45
   65.19  112.05   68.11  113.46   74.94  117.51   80.79  120.64   86.63  124.49
#Mann= 3 , 0 , 0
       0     .06       0      44     .04       0      46    .055       0
Bank Sta=44,46
XS Rating Curve= 0 ,0
Exp/Cntr=0.3,0.1