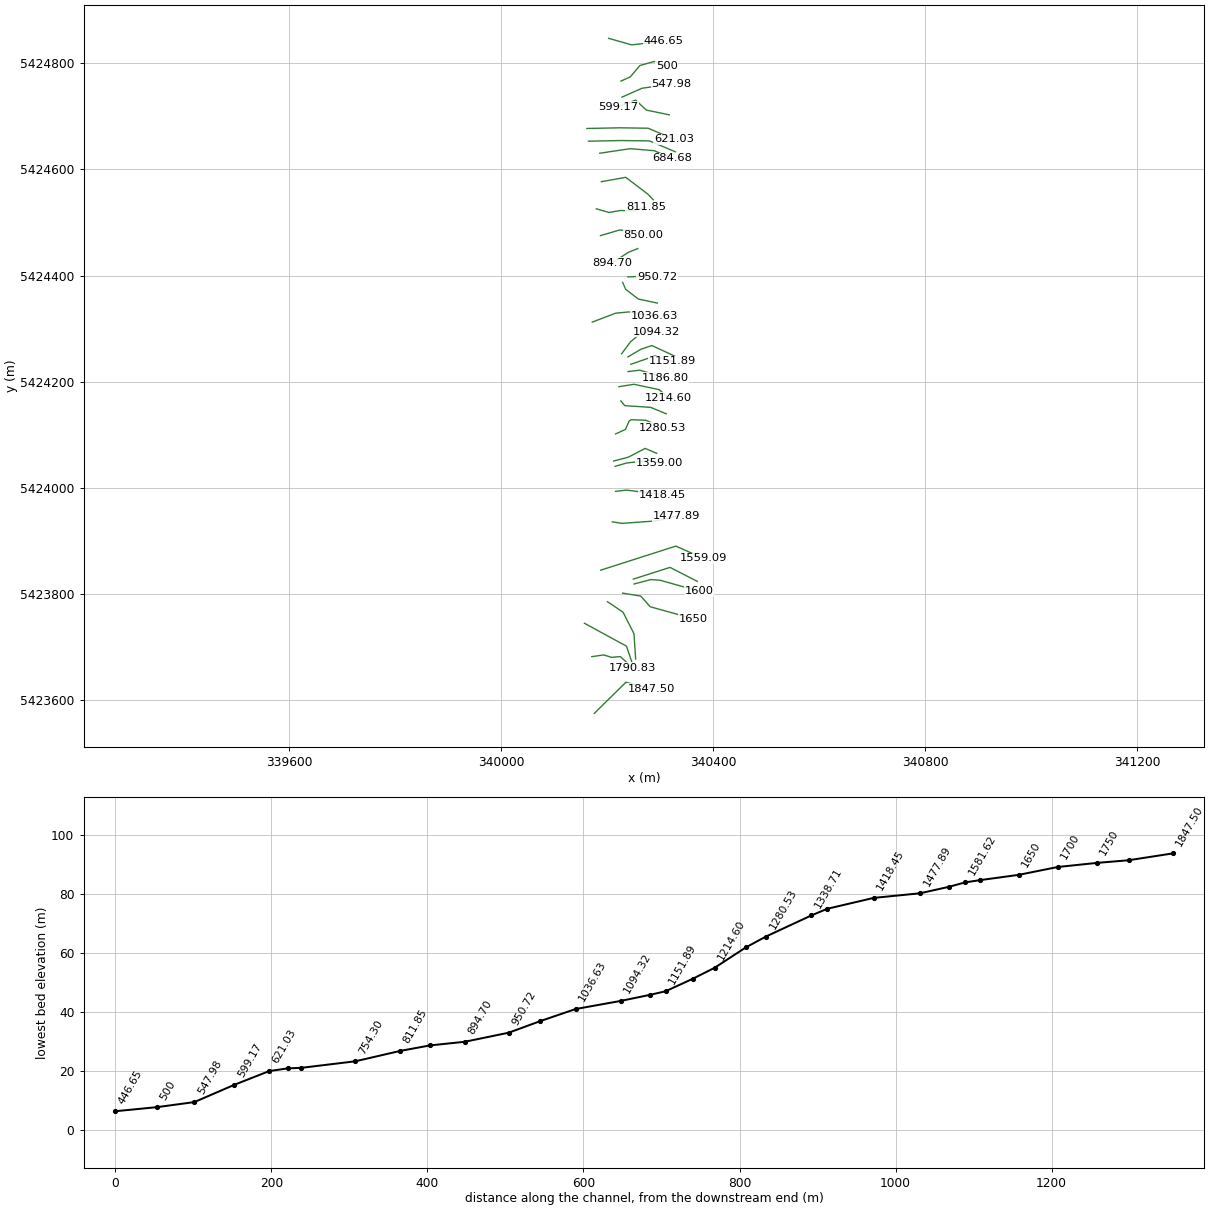
HEC-RAS study PetriesBrk_v001.prj: Petries_Brook

--- PetriesBrk_v001.g02 (geometry) --- (continued)

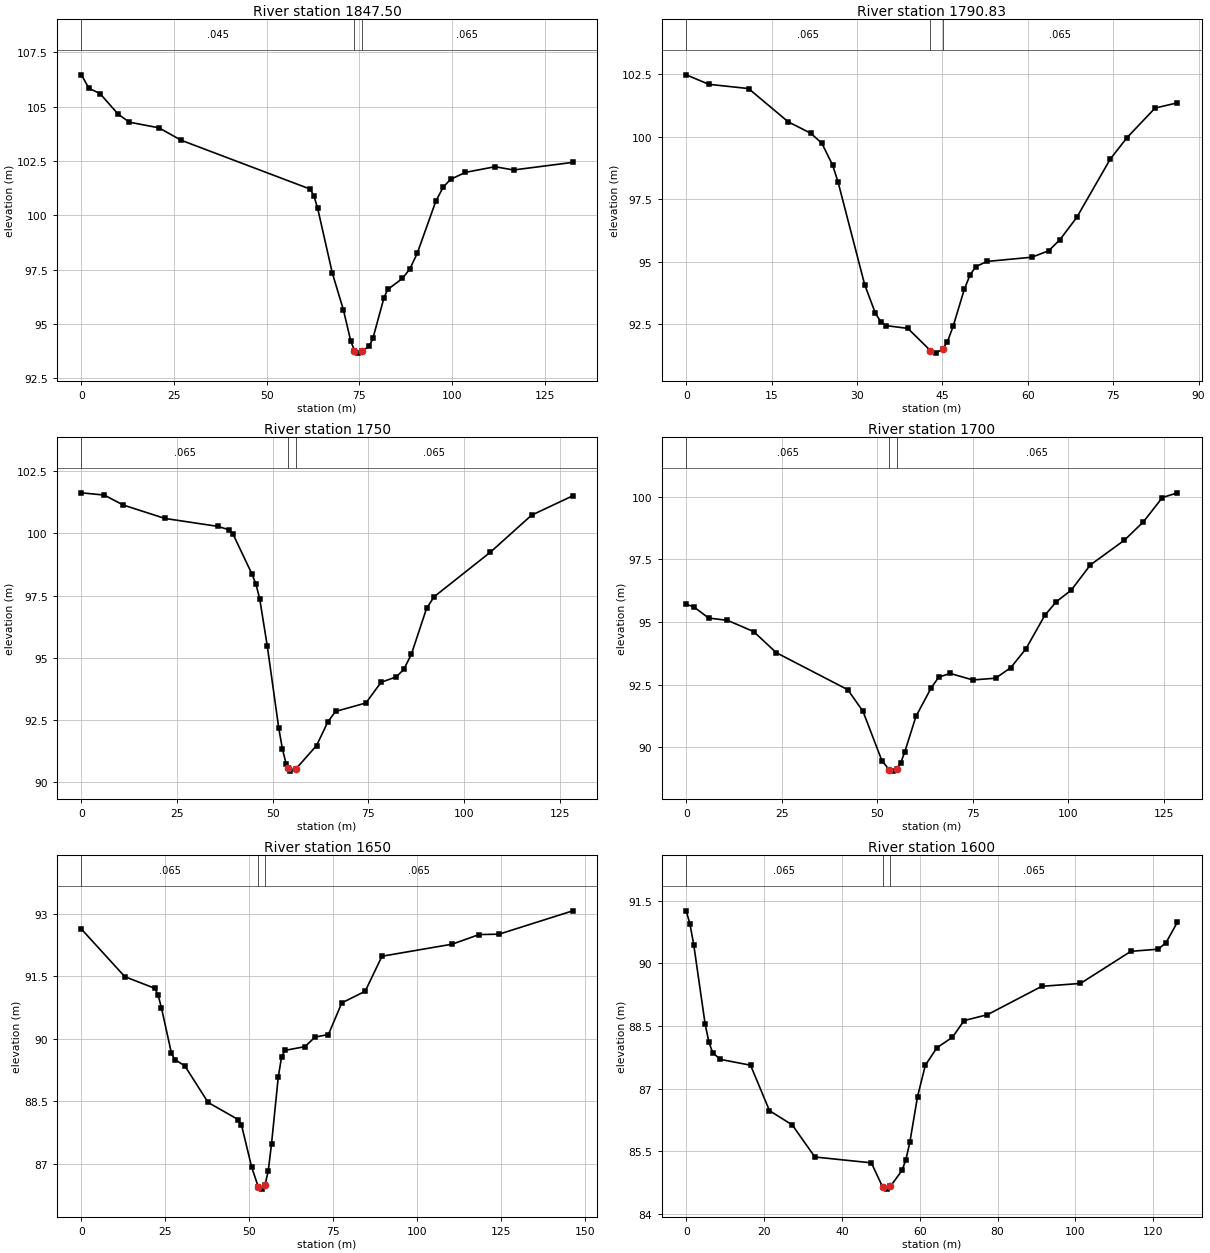
Type RM Length L Ch R = 1 ,1847.50 ,59.8,56.68,53.63
XS GIS Cut Line= 3
340175.8522949225423574.91912842340235.4788818365423633.53289795
340282.9793090825423621.75372314
#Sta/Elev= 30
       0  106.47    1.99  105.85    4.98  105.61    9.95  104.65   12.94  104.29
    20.9  104.03   26.88  103.46   61.71  101.21   62.71   100.9    63.7  100.34
   67.69   97.34   70.67   95.65   72.66   94.21   73.66   93.78   74.65   93.66
   75.66   93.74   77.64   93.98   78.63   94.34   81.62   96.21   82.62   96.59
   86.61    97.1   88.61   97.54    90.6   98.26    95.6  100.65   97.59   101.3
   99.59  101.66  103.59  101.98  111.58  102.24  116.57  102.09  132.55  102.44
#Mann= 3 , 0 , 0
       0    .045       0   73.66     .04       0   75.66    .065       0
Bank Sta=73.66,75.66
XS Rating Curve= 0 ,0
Exp/Cntr=0.3,0.1

Type RM Length L Ch R = 1 ,1790.83 ,41.02,40.83,35.12
XS GIS Cut Line= 5
340171.1350708015423681.87109375340193.806884766 5423685.0123291
340208.1732788095423680.52508545340225.0089111335423681.87109375
340248.3541259775423660.78112793
#Sta/Elev= 30
       0  102.48    3.98   102.1   10.95  101.93   17.91   100.6   21.89  100.14
   23.83   99.74   25.71   98.87   26.65   98.21   31.35   94.08   33.24   92.93
   34.18    92.6   35.12   92.44   38.93   92.33   42.91   91.44    43.9   91.34
   45.05   91.51   45.89    91.8   46.88   92.41   48.87   93.91   49.86   94.47
   50.85    94.8   52.84   95.01   60.73   95.18   63.68   95.44   65.64   95.88
   68.59   96.77   74.49   99.11   77.44   99.97   82.36  101.15   86.29  101.36
#Mann= 3 , 0 , 0
       0    .065       0   42.91     .04       0   45.05    .065       0
Bank Sta=42.91,45.05
XS Rating Curve= 0 ,0
Exp/Cntr=0.3,0.1

Type RM Length L Ch R = 1 ,1750    ,52.18,50,44.17
XS GIS Cut Line= 3
340157.321716309 5423744.6494751340236.5733032235423701.55627441
340248.8344726565423665.35791016
#Sta/Elev= 30
       0  101.63    5.95  101.54    10.9  101.14   21.81   100.6   35.69  100.28
   38.66  100.14   39.65   99.96   44.61   98.35    45.6   97.96   46.59   97.37
   48.57   95.47   51.55   92.19   52.54   91.32   53.53   90.72   54.06   90.57
   54.52   90.44   56.06   90.53   61.46   91.47   64.44   92.43   66.42   92.84
   74.35   93.18   78.31   94.01   82.28   94.23   84.26   94.53   86.24   95.14
   90.21   96.98   92.17   97.45  106.87   99.24  117.65  100.73  128.43  101.51
#Mann= 3 , 0 , 0
       0    .065       0   54.06     .04       0   56.06    .065       0
Bank Sta=54.06,56.06
XS Rating Curve= 0 ,0
Exp/Cntr=0.3,0.1

Type RM Length L Ch R = 1 ,1700    ,48.36,50,51.14
XS GIS Cut Line= 4
340200.7401123055423785.32128906340230.0756835945423765.63391113
340250.7296752935423724.97210693340253.8300781255423677.48730469
#Sta/Elev= 30
       0   95.71    1.96   95.61    5.89   95.16    10.8   95.07   17.66   94.62
   23.55   93.78   42.27    92.3   46.24   91.44   51.19   89.47   53.18   89.09
   54.17   89.05   55.18   89.15   56.15   89.39   57.14    89.8   60.12   91.24
   64.08   92.37   66.06    92.8   69.04   92.95   74.99   92.69   80.94   92.76
    84.9   93.18   88.87   93.93   93.82   95.27    96.8   95.81  100.76   96.28
  105.72   97.28  114.64   98.27   119.6      99  124.56   99.97  128.52  100.16
#Mann= 3 , 0 , 0
       0    .065       0   53.18     .04       0   55.18    .065       0
Bank Sta=53.18,55.18
XS Rating Curve= 0 ,0
Exp/Cntr=0.3,0.1

Type RM Length L Ch R = 1 ,1650    ,36.58,50,59.53
XS GIS Cut Line= 4
340229.2329101565423801.52368164 340263.513488775423795.90209961
340281.3558959965423775.84747314340363.0126953135423753.14709473
#Sta/Elev= 30
       0   92.63    12.9   91.49   21.84   91.21   22.83   91.05   23.82   90.74
    26.8   89.65   27.79    89.5   30.77   89.35   37.72   88.47   46.67   88.06
   47.66   87.93   50.65   86.93   52.63   86.45   53.63   86.39   54.63   86.48
   55.62   86.82   56.61   87.48    58.6   89.07   59.59   89.56   60.59   89.72
   66.57   89.81   69.56   90.04   73.55    90.1   77.53   90.86   84.51   91.14
    89.5   91.98  110.44   92.27  118.42    92.5   124.4   92.51  146.33   93.07
#Mann= 3 , 0 , 0
       0    .065       0   52.63     .04       0   54.63    .065       0
Bank Sta=52.63,54.63
XS Rating Curve= 0 ,0
Exp/Cntr=0.3,0.1

Type RM Length L Ch R = 1 ,1600    ,13.41,18.38,25.54
XS GIS Cut Line= 4
340250.8914794925423818.72668457340282.8820800785423827.11669922
340300.237670898 5423825.7387085340373.1644897465423805.23388672
#Sta/Elev= 30
       0   91.26     .97   90.94    1.95   90.44    4.86   88.55    5.84   88.11
    6.81   87.86    8.75    87.7   16.54   87.56    21.4   86.47   27.24   86.13
   33.07   85.36   47.58   85.22   50.48   84.64   51.48   84.59   52.49   84.66
   55.47   85.04   56.46    85.3   57.46   85.71   59.45   86.81   61.45   87.56
   64.44   87.98   68.42   88.23   71.41   88.63    77.4   88.77   91.35   89.45
  101.32   89.52  114.28   90.29  121.25   90.34  123.25   90.49  126.24   90.99
#Mann= 3 , 0 , 0
       0    .065       0   50.48     .04       0   52.49    .065       0
Bank Sta=50.48,52.49
XS Rating Curve= 0 ,0
Exp/Cntr=0.3,0.1

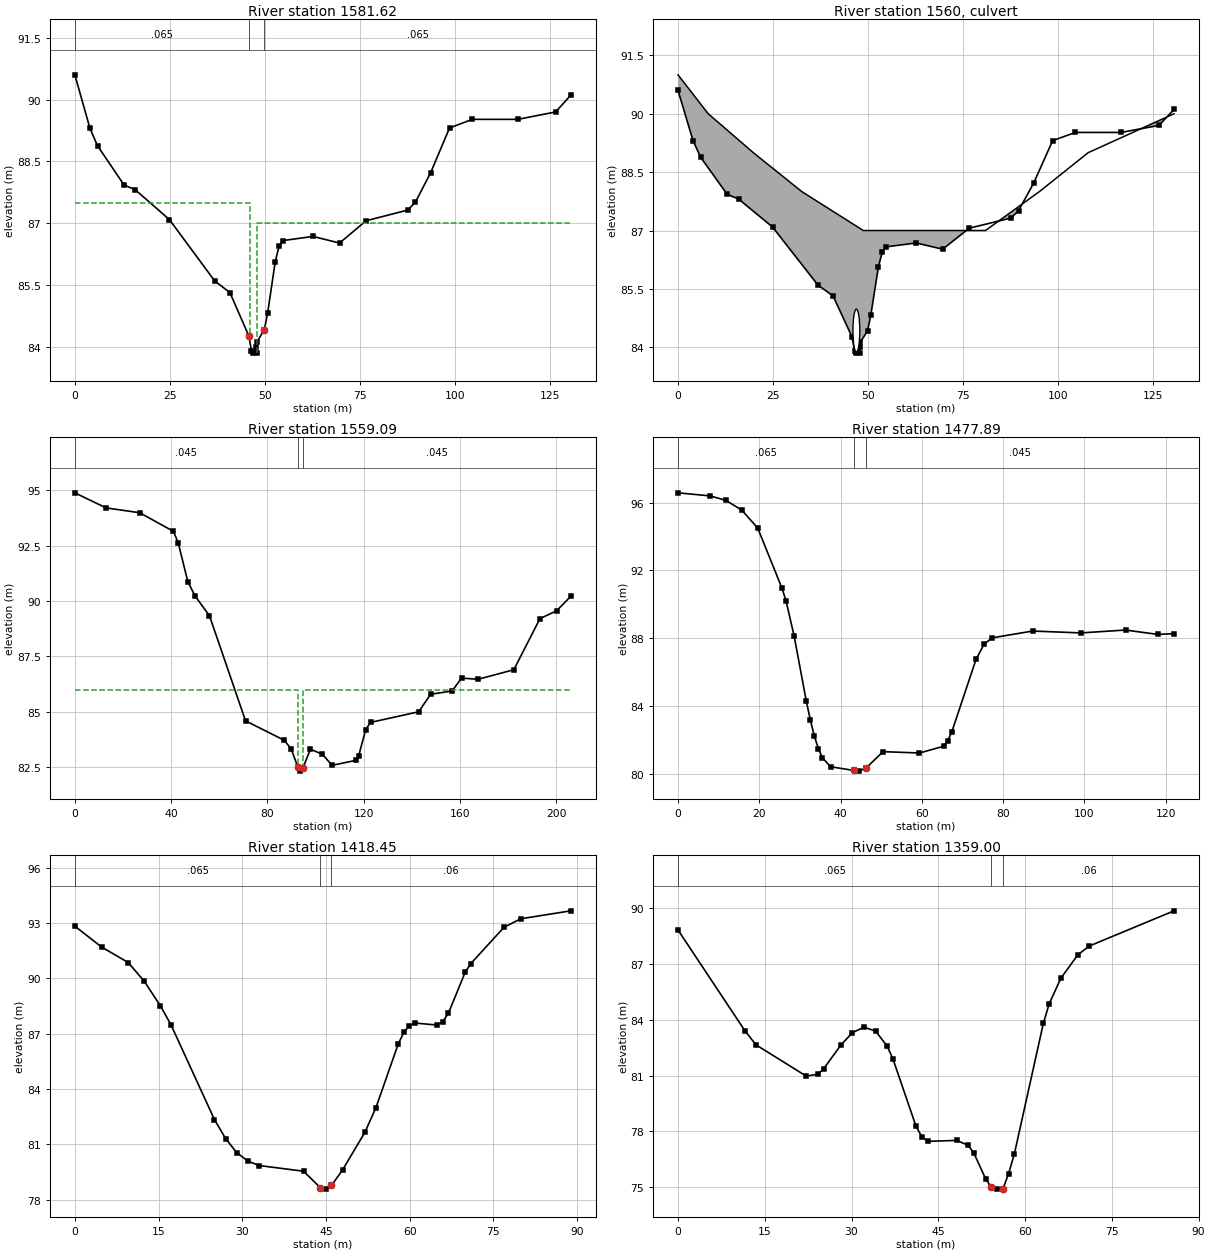
Type RM Length L Ch R = 1 ,1581.62 ,22.3,21.31,24.75
XS GIS Cut Line= 3
340249.5263061525423827.92871094340318.7141113285423850.03131104
340370.2128906255423823.61828613
#Sta/Elev= 30
       0    90.6    3.98    89.3    5.97   88.88   12.93   87.93   15.92   87.81
   24.87   87.09   36.81    85.6   40.79   85.32   45.77   84.27   46.48    83.9
   46.93   83.85   47.76      84   47.82   83.85   47.97   84.13   49.86   84.42
   50.74   84.83   52.73   86.07   53.73   86.44   54.72   86.58   62.68   86.68
   69.65   86.52   76.62   87.06    87.6   87.32    89.6   87.51   93.59   88.22
   98.58   89.31  104.56   89.52  116.54   89.52  126.52    89.7  130.51   90.11
#Mann= 3 , 0 , 0
       0    .065       0   45.77     .04       0   49.86    .065       0
#XS Ineff= 2 , 0
       0   46.03    87.5   47.82       0      87
Permanent Ineff=
       F       F
Bank Sta=45.77,49.86
XS Rating Curve= 0 ,0
Exp/Cntr=0.5,0.3

Type RM Length L Ch R = 2 ,1560    ,,,
BEGIN DESCRIPTION:
Candow Drive (1105)
END DESCRIPTION:
Bridge Culvert--1,0,-1,-1, 0
Deck Dist Width WeirC Skew NumUp NumDn MinLoCord MaxHiCord MaxSubmerge Is_Ogee
6.6,6.2,1.67,0, 9, 16, 87, , 0.98, 0, 1,1,,
       0    7.95   19.82   32.57   48.76   80.91   95.09  107.92  130.51
      91      90      89      88      87      87      88      89      90
                                                                        
       0   11.31   23.09   33.66   43.62   55.14   66.53    79.2   94.74  153.99
  168.75  174.52   182.9  192.47  201.94  206.07
      95      94      93      92      91      90      89      88      87      87
      88      89      90      91      92      93
                                                                                
                                                
BR Coef=-1 , 0 , 0 ,, 0 ,,,0.8,-1,,0,
WSPro=,,,, 1 ,,,, 0 ,,,, 0 ,,,,-1 ,-1 ,-1 , 0 , 0 , 0 , 0 , 0
Culvert=3,1.1,1.8,7.5,0.033,0.9,1,34,3,83.88,46.93,83.19,93.7,Culvert #1  , 0 ,1.8
Culvert Bottom n=0.033
BC Design=,, 0 ,, 0 ,,,,,,
BC Use User HTab Curves=0
BC User HTab FreeFlow(D)= 0

Type RM Length L Ch R = 1 ,1559.09 ,37.77,36.77,37
XS GIS Cut Line= 3
340187.9370727545423844.78692627 340329.685485845423890.12249756
340381.9757080085423866.81750488
#Sta/Elev= 30
       0   94.89   12.98   94.21   26.97   93.99   40.95   93.15   42.95   92.63
   46.94   90.88   49.94   90.23   55.93   89.34   70.92   84.59    86.9   83.72
   89.89   83.33   92.67   82.49   93.71   82.32   94.75   82.46   97.88   83.31
  102.88   83.08  106.87   82.58  116.86   82.81  117.86   82.99  120.86    84.2
  122.85   84.52  142.83      85  147.82   85.79  156.72   85.94  160.67   86.52
  167.58   86.47  182.38    86.9  193.24   89.21  200.15   89.56  206.07   90.22
#Mann= 3 , 0 , 0
       0    .045       0   92.67     .04       0   94.75    .045       0
#XS Ineff= 2 , 0
       0   92.81      86   94.59       0      86
Permanent Ineff=
       F       F
Bank Sta=92.67,94.75
XS Rating Curve= 0 ,0
Exp/Cntr=0.5,0.3

Type RM Length L Ch R = 1 ,1477.89 ,60.04,59.45,57
XS GIS Cut Line= 4
340209.7918701175423935.84832764 340228.18572998 5423932.9664917
340290.6947021485423937.52667236 340330.507690435423946.17767334
#Sta/Elev= 30
       0   96.58    7.84    96.4   11.76   96.14   15.68   95.56   19.61    94.5
   25.58   90.95   26.58    90.2   28.57   88.13   31.55    84.3   32.55   83.18
   33.54   82.22   34.54   81.48   35.53   80.94   37.52   80.41   43.27   80.19
   44.48   80.15   46.25   80.33   50.45    81.3   59.41   81.22   65.38   81.62
   66.37   81.94   67.37   82.47   73.33   86.75   75.32   87.65   77.31   88.02
   87.26   88.42   99.18   88.31  110.11   88.48  118.06   88.22  122.04   88.27
#Mann= 3 , 0 , 0
       0    .065       0   43.27     .04       0   46.25    .045       0
Bank Sta=43.27,46.25
XS Rating Curve= 0 ,0
Exp/Cntr=0.3,0.1

Type RM Length L Ch R = 1 ,1418.45 ,57.65,59.45,59.69
XS GIS Cut Line= 3
340215.7122802735423993.27050781340236.6005249025423995.65368652
340303.918518066  5423987.253479
#Sta/Elev= 30
       0   92.83    4.78    91.7    9.56   90.86   12.42   89.85   15.29   88.53
    17.2    87.5   25.01   82.35   27.01   81.32      29   80.56      31    80.1
      33   79.86   40.98   79.55   43.98   78.66   44.97   78.58   45.98   78.78
   47.96   79.62   51.95   81.65   53.95      83   57.94   86.45   58.93   87.07
   59.93   87.44   60.93   87.58   64.92   87.47   65.92   87.66   66.92   88.11
   69.91   90.32   70.91   90.79   76.89   92.77   79.89   93.23   88.86   93.66
#Mann= 3 , 0 , 0
       0    .065       0   43.98     .04       0   45.98     .06       0
Bank Sta=43.98,45.98
XS Rating Curve= 0 ,0
Exp/Cntr=0.3,0.1

Type RM Length L Ch R = 1 ,1359.00 ,18.95,20.29,21.35
XS GIS Cut Line= 4
340215.0609130865424040.37988281340236.3314819345424046.61627197
340280.0125122075424051.82092285 340298.963073735424046.85308838
#Sta/Elev= 30
       0   88.83   11.56   83.41   13.49   82.65   22.17   80.97   24.17   81.07
   25.17   81.36   28.16   82.64   30.16   83.31   32.16    83.6   34.16   83.39
   36.16   82.58   37.16   81.89   41.16   78.26   42.16   77.71   43.16   77.46
   48.16   77.51   50.16   77.25   51.16   76.82   53.16   75.46   54.16      75
   55.16   74.89   56.16   74.89   57.16   75.73   58.16    76.8   63.16   83.81
   64.16   84.85   66.16   86.22   69.09   87.48   71.05   87.96   85.75   89.86
#Mann= 3 , 0 , 0
       0    .065       0   54.16     .04       0   56.16     .06       0
Bank Sta=54.16,56.16
XS Rating Curve= 0 ,0
Exp/Cntr=0.3,0.1

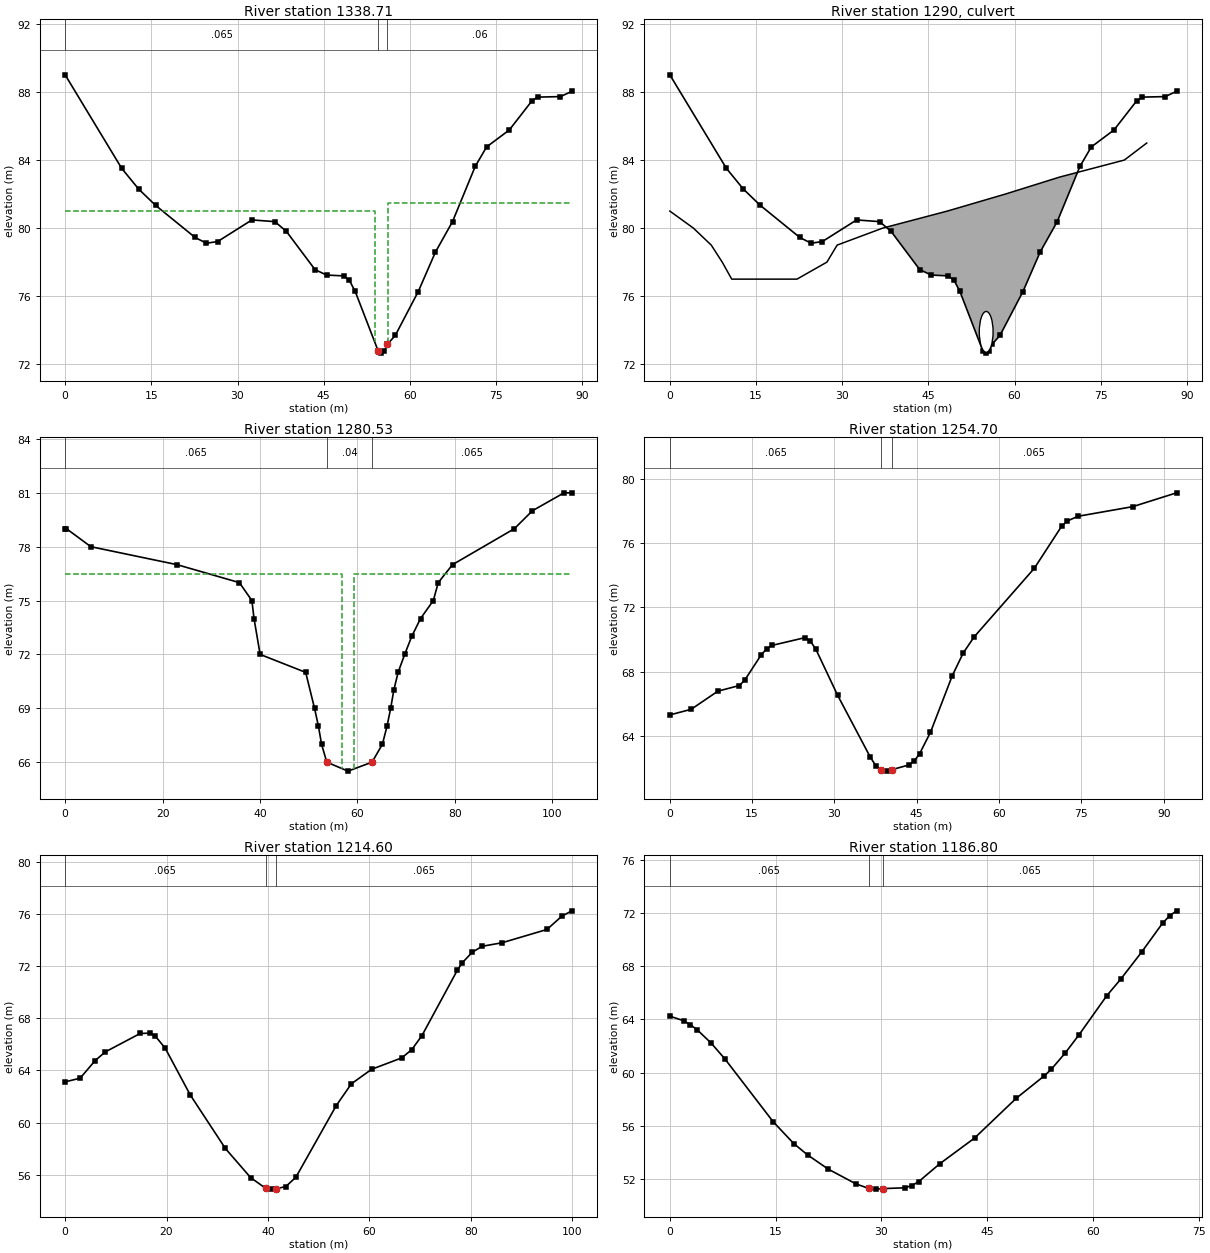
Type RM Length L Ch R = 1 ,1338.71 ,61.19,58.18,56.11
XS GIS Cut Line= 4
340212.2404785165424050.46069336340239.8464965825424057.61907959
340271.7230834965424074.20349121340293.5711059575424064.92449951
#Sta/Elev= 30
       0   89.01    9.83   83.52   12.78    82.3   15.73   81.34   22.62   79.45
   24.59   79.11   26.55   79.21   32.51   80.48    36.5   80.38    38.5   79.81
   43.49   77.56   45.49   77.24   48.48   77.19   49.48   76.92   50.48   76.28
   54.46    72.8   55.06   72.65   55.52   72.75   56.06   73.16   57.46   73.69
   61.46   76.27   64.45   78.59   67.42   80.38   71.38   83.63   73.35   84.77
   77.31   85.77   81.27   87.49   82.25    87.7   86.21   87.73   88.19   88.04
#Mann= 3 , 0 , 0
       0    .065       0   54.46     .04       0   56.06     .06       0
#XS Ineff= 2 , 0
       0   53.86      81   56.26       0    81.5
Permanent Ineff=
       F       F
Bank Sta=54.46,56.06
XS Rating Curve= 0 ,0
Exp/Cntr=0.5,0.3

Type RM Length L Ch R = 2 ,1290    ,,,
BEGIN DESCRIPTION:
O'Conner Drive (1104)
END DESCRIPTION:
Bridge Culvert--1,0,-1,-1, 0
Deck Dist Width WeirC Skew NumUp NumDn MinLoCord MaxHiCord MaxSubmerge Is_Ogee
17.2,7.7,1.67,0, 14, 12, 79.11, , 0.98, 0, 1,1,,
       0     4.1    7.21    9.12   10.77   22.13   27.34   29.12   37.06   48.29
   58.39   67.85   79.11      83
      81      80      79      78      77      77      78      79      80      81
      82      83      84      85
                                                                                
                                
       0    2.58     9.9   23.38   35.14   44.69   53.76   62.43   73.22   84.61
   87.39   104.3
      78      78      78      79      80      81      82      83      84      85
      85    86.5
                                                                                
                
BR Coef=-1 , 0 , 0 ,, 0 ,,,0.8,-1,,0,
WSPro=,,,, 1 ,,,, 0 ,,,, 0 ,,,,-1 ,-1 ,-1 , 0 , 0 , 0 , 0 , 0
Culvert=1,2.4,,43,0.032,0.9,1,2,3,72.7,55.06,70.47,58.06,Culvert #1  , 0 ,2.2
Culvert Bottom n=0.032
BC Design=,, 0 ,, 0 ,,,,,,
BC Use User HTab Curves=0
BC User HTab FreeFlow(D)= 0

Type RM Length L Ch R = 1 ,1280.53 ,25.57,25.83,25.08
XS GIS Cut Line= 6
      340216.083     5424101.519      340234.472     5424109.933
       340241.71     5424125.948      340245.255     5424128.236
      340273.093     5424127.359      340303.914     5424113.364
#Sta/Elev= 30
       0      79     .28      79    5.28      78   22.95      77   35.76      76
   38.33      75   38.77      74   40.02      72   49.37      71   51.19      69
   51.99      68   52.63      67    53.7      66   58.06    65.5      63      66
   65.12      67   66.06      68   66.82      69   67.45      70   68.34      71
   69.69      72   71.13      73   72.95      74   75.57      75   76.58      76
   79.51      77   92.19      79    95.9      80   102.4      81     104      81
#Mann= 3 , 0 , 0
       0    .065       0    53.7     .04       0      63    .065       0
#XS Ineff= 2 , 0
       0   56.86    76.5   59.26       0    76.5
Permanent Ineff=
       F       F
Bank Sta=53.7,63
XS Rating Curve= 0 ,0
Exp/Cntr=0.5,0.3

Type RM Length L Ch R = 1 ,1254.70 ,40.6,40.1,39.23
XS GIS Cut Line= 4
 340225.886718755424163.72808838340233.4039306645424154.79608154
340282.0579223635424151.59912109 340311.568298345424139.45507813
#Sta/Elev= 30
       0   65.31    3.89   65.66    8.76   66.79   12.67   67.14   13.66   67.48
   16.65   69.05   17.64   69.43   18.64   69.64   24.61   70.12   25.61    69.9
    26.6   69.41   30.58   66.53   36.55   62.67   37.55   62.14   38.54   61.85
   39.54   61.81   40.54   61.91   43.52   62.19   44.51   62.43   45.51   62.89
    47.5   64.23   51.48   67.76   53.47   69.17   55.46   70.17   66.42   74.44
    71.4   77.06    72.4   77.38   74.39   77.68   84.37   78.28   92.34   79.14
#Mann= 3 , 0 , 0
       0    .065       0   38.54    .035       0   40.54    .065       0
Bank Sta=38.54,40.54
XS Rating Curve= 0 ,0
Exp/Cntr=0.3,0.1

Type RM Length L Ch R = 1 ,1214.60 ,28.26,27.8,27.43
XS GIS Cut Line= 4
 340222.293090825424190.53369141340250.554077148 5424195.0333252
340298.2213134775424184.99389648340315.2128906255424170.09613037
#Sta/Elev= 30
       0   63.12    2.96    63.4    5.92   64.75    7.89   65.41    14.8   66.83
   16.78   66.86   17.76   66.64   19.74    65.7   24.67   62.12    31.6   58.01
   36.57   55.78   39.55   54.95   40.55   54.89   41.55   54.91   43.53   55.09
   45.52   55.81   53.47    61.3   56.45   62.97   60.43   64.08   66.39   64.96
   68.38    65.6   70.37   66.67   77.33   71.67   78.31   72.25   80.28   73.06
   82.24   73.52   86.17   73.79   95.02   74.81   97.96   75.83   99.93   76.24
#Mann= 3 , 0 , 0
       0    .065       0   39.55    .035       0   41.55    .065       0
Bank Sta=39.55,41.55
XS Rating Curve= 0 ,0
Exp/Cntr=0.3,0.1

Type RM Length L Ch R = 1 ,1186.80 ,25.25,34.92,35.78
XS GIS Cut Line= 3
340239.397521973 5424219.0322876340261.7108764655424221.66650391
340308.9729003915424207.26672363
#Sta/Elev= 30
       0   64.25    1.95   63.91    2.93    63.6    3.91   63.21    5.86   62.22
    7.82   61.02   14.65   56.29   17.58   54.64   19.54   53.78   22.47   52.71
   26.42   51.59   28.24   51.25   29.24    51.2   30.24   51.24   33.34    51.3
   34.33   51.47   35.31   51.77   38.28   53.11   43.22   55.05   49.15   58.06
    53.1   59.74   54.09   60.23   56.07   61.46   58.04   62.84   61.99    65.8
   63.97   67.05   66.93   69.09    69.9   71.27   70.89   71.82   71.88    72.2
#Mann= 3 , 0 , 0
       0    .065       0   28.24    .035       0   30.24    .065       0
Bank Sta=28.24,30.24
XS Rating Curve= 0 ,0
Exp/Cntr=0.3,0.1

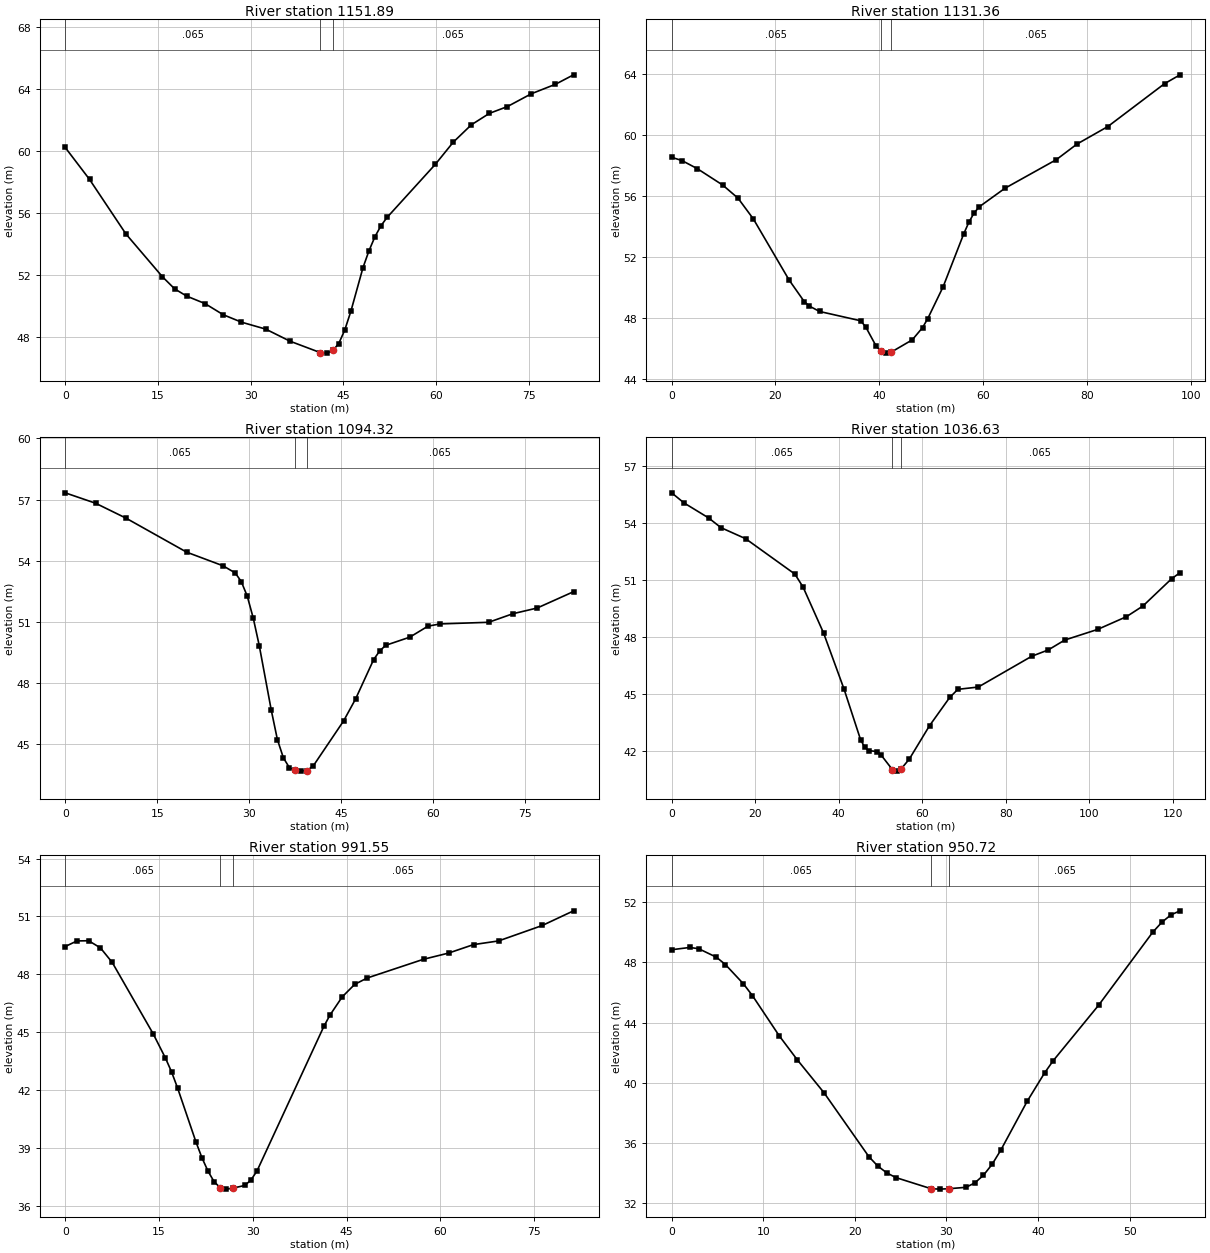
Type RM Length L Ch R = 1 ,1151.89 ,20.73,20.52,20.47
XS GIS Cut Line= 3
340244.8441162115424232.72967529340290.3491210945424248.53430176
340322.8529052735424238.34912109
#Sta/Elev= 30
       0   60.23    3.93   58.17    9.83   54.64   15.73   51.88    17.7    51.1
   19.66   50.63   22.61   50.15   25.56   49.43   28.51   48.95   32.44    48.5
   36.37   47.72   41.29   46.98   42.27   46.95   43.29   47.12   44.24   47.56
   45.22   48.44   46.21   49.65   48.17   52.47   49.14   53.56   50.12   54.48
   51.09   55.18   52.06   55.71   59.85   59.13   62.77   60.57   65.69   61.69
   68.61   62.43   71.53   62.87   75.42    63.7   79.31   64.31   82.23   64.92
#Mann= 3 , 0 , 0
       0    .065       0   41.29    .035       0   43.29    .065       0
Bank Sta=41.29,43.29
XS Rating Curve= 0 ,0
Exp/Cntr=0.3,0.1

Type RM Length L Ch R = 1 ,1131.36 ,25.77,37.05,38
XS GIS Cut Line= 4
340239.2006835945424246.57751465340263.7606811525424261.08288574
340284.4135131845424268.05688477340327.6729125985424248.11169434
#Sta/Elev= 30
       0   58.55    1.97   58.34    4.92   57.81    9.84   56.73   12.79   55.87
   15.74   54.51   22.62   50.51   25.57   49.08   26.56   48.79   28.52   48.44
   36.45   47.83   37.44    47.4   39.42   46.16   40.33   45.84   41.33   45.71
   42.33   45.78   46.36   46.58   48.34   47.38   49.33   47.96   52.31   50.06
   56.28   53.53   57.27   54.29   58.26   54.89   59.25    55.3   64.22   56.52
   74.14    58.4   78.11   59.42   84.06   60.57   94.98   63.38   97.96   63.96
#Mann= 3 , 0 , 0
       0    .065       0   40.33    .035       0   42.33    .065       0
Bank Sta=40.33,42.33
XS Rating Curve= 0 ,0
Exp/Cntr=0.3,0.1

Type RM Length L Ch R = 1 ,1094.32 ,60.38,57.68,53.64
XS GIS Cut Line= 4
 340227.351684575424252.60668945340243.9583129885424274.79992676
340265.6029052735424293.26312256 340292.285278325424294.38208008
#Sta/Elev= 30
       0   57.33    4.95   56.82     9.9   56.09    19.8   54.42   25.74   53.75
   27.72    53.4    28.7   52.98   29.68   52.26   30.66   51.18   31.64   49.83
    33.6   46.66   34.59   45.23   35.57   44.33   36.55   43.85   37.43   43.72
   38.44   43.68   39.44   43.71   40.47   43.95   45.38   46.14   47.34   47.22
   50.28   49.15   51.26   49.57   52.24   49.85   56.17   50.25   59.14   50.79
   61.11    50.9   69.03   50.98   72.98    51.4   76.94   51.68   82.87   52.48
#Mann= 3 , 0 , 0
       0    .065       0   37.43    .035       0   39.44    .065       0
Bank Sta=37.43,39.44
XS Rating Curve= 0 ,0
Exp/Cntr=0.3,0.1

Type RM Length L Ch R = 1 ,1036.63 ,48.92,45.08,39.98
XS GIS Cut Line= 4
340171.9953002935424312.23510742340216.0892944345424329.05828857
340241.2180786135424331.42767334 340289.816284185424323.13470459
#Sta/Elev= 30
       0   55.57    2.95   55.04    8.85   54.25    11.8   53.74    17.7   53.16
    29.5    51.3   31.46   50.62   36.38    48.2    41.3   45.24   45.23    42.6
   46.21    42.2   47.19   42.02   49.14   41.97   50.11    41.8   52.86   41.02
   53.88   40.94   54.89   41.04    56.9   41.57   61.76   43.33   66.61   44.82
   68.55   45.24   73.42   45.36   86.24   46.98   90.18   47.31   94.13   47.83
  102.02   48.39  108.92   49.06  112.86   49.62  119.76   51.06  121.74   51.37
#Mann= 3 , 0 , 0
       0    .065       0   52.86    .035       0   54.89    .065       0
Bank Sta=52.86,54.89
XS Rating Curve= 0 ,0
Exp/Cntr=0.3,0.1

Type RM Length L Ch R = 1 ,991.55  ,37.49,40.83,42.68
XS GIS Cut Line= 4
340229.3386840825424387.13153076340234.8859252935424374.19451904
340258.7916870125424355.71289063340294.9808959965424348.05627441
#Sta/Elev= 30
       0   49.44    1.88   49.73    3.75   49.74    5.63   49.37    7.51   48.62
   14.08   44.91   16.03   43.66      17   42.95   17.98    42.1    20.9   39.32
   21.87   38.49   22.85   37.79   23.82   37.25    24.8   36.94   25.77   36.87
   26.81   36.92    28.7   37.06   29.67   37.33   30.65    37.8   41.37   45.31
   42.34   45.89   44.29   46.83   46.29   47.48   48.29   47.81   57.29   48.78
   61.29    49.1   65.29   49.54   69.29   49.73   76.28   50.53   81.28   51.29
#Mann= 3 , 0 , 0
       0    .065       0    24.8    .035       0   26.81    .065       0
Bank Sta=24.8,26.81
XS Rating Curve= 0 ,0
Exp/Cntr=0.3,0.1

Type RM Length L Ch R = 1 ,950.72  ,51.8,56.02,58.21
XS GIS Cut Line= 4
340239.1104736335424397.36450195340264.5355224615424398.42327881
340280.5437011725424395.83508301340294.3154907235424397.01171875
#Sta/Elev= 30
       0   48.85    1.96      49    2.94   48.92    4.89   48.35    5.87   47.86
    7.83   46.58    8.81    45.8   11.74   43.12    13.7   41.53   16.64   39.32
   21.53   35.07   22.51   34.44   23.49   33.99   24.47   33.68   28.31   32.94
   29.26   32.91   30.31   32.94   32.12   33.03   33.08   33.32   34.03   33.83
   34.99   34.57   35.94   35.52    38.8   38.75   40.71   40.65   41.66   41.47
    46.6   45.15   52.52   50.02   53.51   50.68    54.5   51.17   55.49   51.44
#Mann= 3 , 0 , 0
       0    .065       0   28.31    .035       0   30.31    .065       0
Bank Sta=28.31,30.31
XS Rating Curve= 0 ,0
Exp/Cntr=0.3,0.1

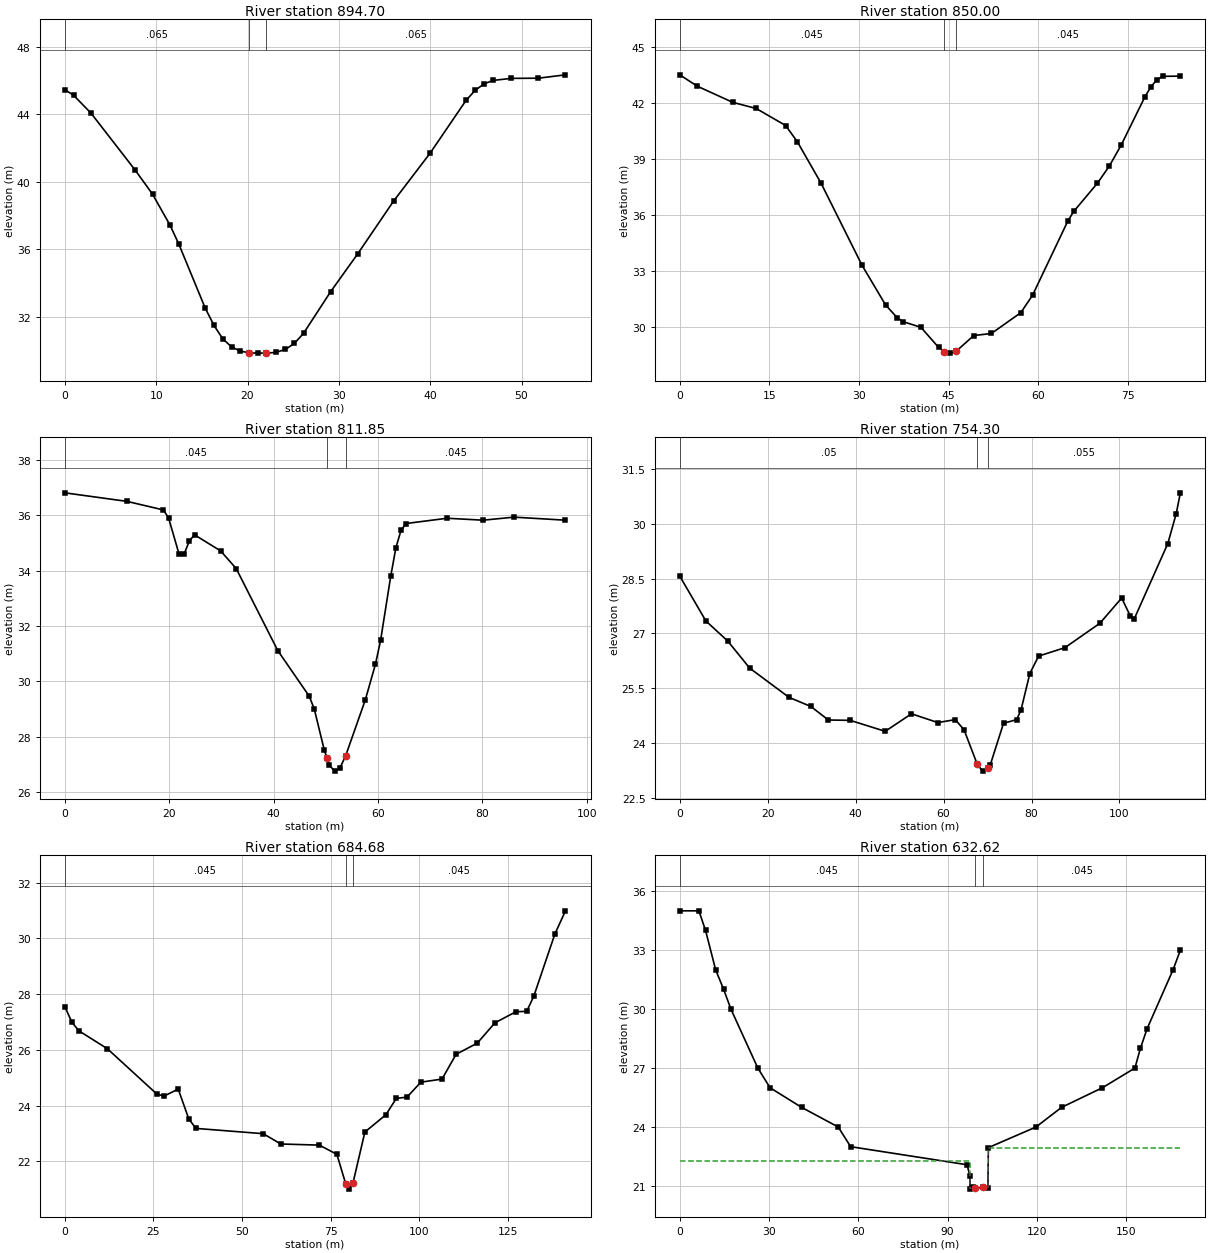
Type RM Length L Ch R = 1 ,894.70  ,47,44.71,42.01
XS GIS Cut Line= 3
340257.9028930665424450.84350586340240.0692749025424443.71368408
340210.2770996095424424.21173096
#Sta/Elev= 30
       0   45.46     .96   45.13    2.88   44.06    7.68   40.71     9.6   39.27
   11.52   37.43   12.48   36.31   15.36   32.53   16.33   31.49   17.29    30.7
   18.25   30.22   19.21   29.97    20.2   29.87   21.11   29.85   22.02   29.85
   23.08   29.89   24.15   30.07   25.14   30.43   26.13   31.02    29.1   33.49
   32.06   35.73   36.02   38.88   39.98   41.69   43.93   44.83   44.92   45.42
   45.91   45.81    46.9   46.01   48.88   46.13   51.85   46.14   54.81   46.34
#Mann= 3 , 0 , 0
       0    .065       0    20.2    .035       0   22.02    .065       0
Bank Sta=20.2,22.02
XS Rating Curve= 0 ,0
Exp/Cntr=0.3,0.1

Type RM Length L Ch R = 1 ,850.00  ,37.6,38.14,38.02
XS GIS Cut Line= 4
340187.4959106455424475.19091797340223.3823242195424485.72192383
340247.9417114265424485.22027588340267.9468994145424476.56628418
#Sta/Elev= 30
       0   43.49    2.95   42.88    8.86   42.02   12.79   41.69   17.72   40.78
   19.68   39.91   23.62   37.71   30.51    33.3   34.45   31.18   36.42   30.49
    37.4   30.29   40.35   29.99    43.3   28.92   44.28   28.68   45.26   28.61
   46.28   28.72   49.19   29.55   52.14   29.66   57.05   30.77   59.02    31.7
   64.94   35.68   65.93   36.19   69.89    37.7   71.87   38.61   73.85   39.73
   77.82   42.31   78.81   42.84    79.8   43.22   80.79   43.41   83.76   43.42
#Mann= 3 , 0 , 0
       0    .045       0   44.28    .035       0   46.28    .045       0
Bank Sta=44.28,46.28
XS Rating Curve= 0 ,0
Exp/Cntr=0.3,0.1

Type RM Length L Ch R = 1 ,811.85  ,66.88,57.56,53.13
XS GIS Cut Line= 5
340179.7424926765424525.77111816340203.6002807625424518.81170654
340225.2055053715424522.59832764340246.7081298835424521.57489014
340273.3305053715424528.84130859
#Sta/Elev= 30
       0   36.82   11.93   36.51   18.89    36.2   19.88   35.91   21.87   34.61
   22.86   34.61   23.86   35.08   24.85    35.3   29.84   34.72   32.83   34.08
    40.8   31.11   46.79   29.47   47.77   29.01   49.72    27.5   50.21   27.23
    50.7   26.96   51.68   26.75   52.66   26.85   53.77   27.29   57.55   29.32
   59.51   30.62   60.49   31.48   62.44   33.81   63.42   34.83    64.4   35.46
   65.38   35.71   73.24    35.9   80.14   35.83   86.05   35.94   95.91   35.83
#Mann= 3 , 0 , 0
       0    .045       0   50.21    .045       0   53.77    .045       0
Bank Sta=50.21,53.77
XS Rating Curve= 0 ,0
Exp/Cntr=0.3,0.1

Type RM Length L Ch R = 1 ,754.30  ,55.1,69.62,72.69
XS GIS Cut Line= 4
340189.1492919925424576.81689453 340235.136718755424585.06170654
340277.2058715825424553.11328125340287.0748901375424542.75292969
#Sta/Elev= 30
       0   28.57    5.96   27.34   10.93   26.79   15.91   26.05   24.85   25.25
   29.82      25    33.8   24.63   38.77   24.62   46.72   24.32    52.7    24.8
   58.68   24.56   62.67   24.64   64.66   24.36   67.65   23.42   68.87   23.23
   70.09   23.31   70.64   23.41   73.63   24.54   76.62   24.64   77.62   24.91
   79.61    25.9   81.61   26.38   87.59   26.61   95.56   27.28   100.5   27.97
  102.41   27.49  103.36    27.4  110.99   29.46   112.9   30.28  113.85   30.85
#Mann= 3 , 0 , 0
       0     .05       0   67.65    .035       0   70.09    .055       0
Bank Sta=67.65,70.09
XS Rating Curve= 0 ,0
Exp/Cntr=0.3,0.1

Type RM Length L Ch R = 1 ,684.68  ,15.33,16.82,17.85
XS GIS Cut Line= 4
340186.1815185555424630.47332764340243.4896850595424639.01428223
340288.7612915045424635.23052979340323.6533203135424620.69268799
#Sta/Elev= 30
       0   27.55       2   26.99       4   26.68   11.99   26.04   25.97   24.41
   27.97   24.34   31.97   24.59   34.96   23.52   36.96   23.18   55.94   22.99
    60.9   22.62   71.77   22.58   76.71   22.25   79.23   21.18   80.24      21
   81.25   21.22   84.61   23.05   90.53   23.67   93.49   24.26   96.46    24.3
  100.41   24.84  106.35   24.95  110.33   25.84   116.3   26.24  121.28   26.97
  127.24   27.37  130.23   27.38  132.22   27.92  138.19   30.16  141.17   30.99
#Mann= 3 , 0 , 0
       0    .045       0   79.23    .035       0   81.25    .045       0
Bank Sta=79.23,81.25
XS Rating Curve= 0 ,0
Exp/Cntr=0.3,0.1

Type RM Length L Ch R = 1 ,632.62  ,25.35,24.01,23.18
XS GIS Cut Line= 4
      340164.761      5424653.17      340226.992     5424654.375
      340280.058     5424653.652      340328.782     5424633.164
#Sta/Elev= 27
       0      35    6.43      35    8.68      34   12.06      32   14.76      31
   17.19      30   26.23      27   30.33      26   40.94      25   53.24      24
   57.41      23   96.53   22.08   97.47   21.51   97.48   20.84   98.54   20.97
   99.13   20.88  101.96   20.93  103.53   20.88  103.66   22.95  119.66      24
  128.26      25     142      26   152.9      27  154.73      28  156.98      29
  165.71      32  168.17      33
#Mann= 3 , 0 , 0
       0    .045       0   99.13    .035       0  101.96    .045       0
#XS Ineff= 2 , 0
       0   97.48   22.25  103.53       0   22.95
Permanent Ineff=
       F       F
Bank Sta=99.13,101.96
XS Rating Curve= 0 ,0
Exp/Cntr=0.5,0.3

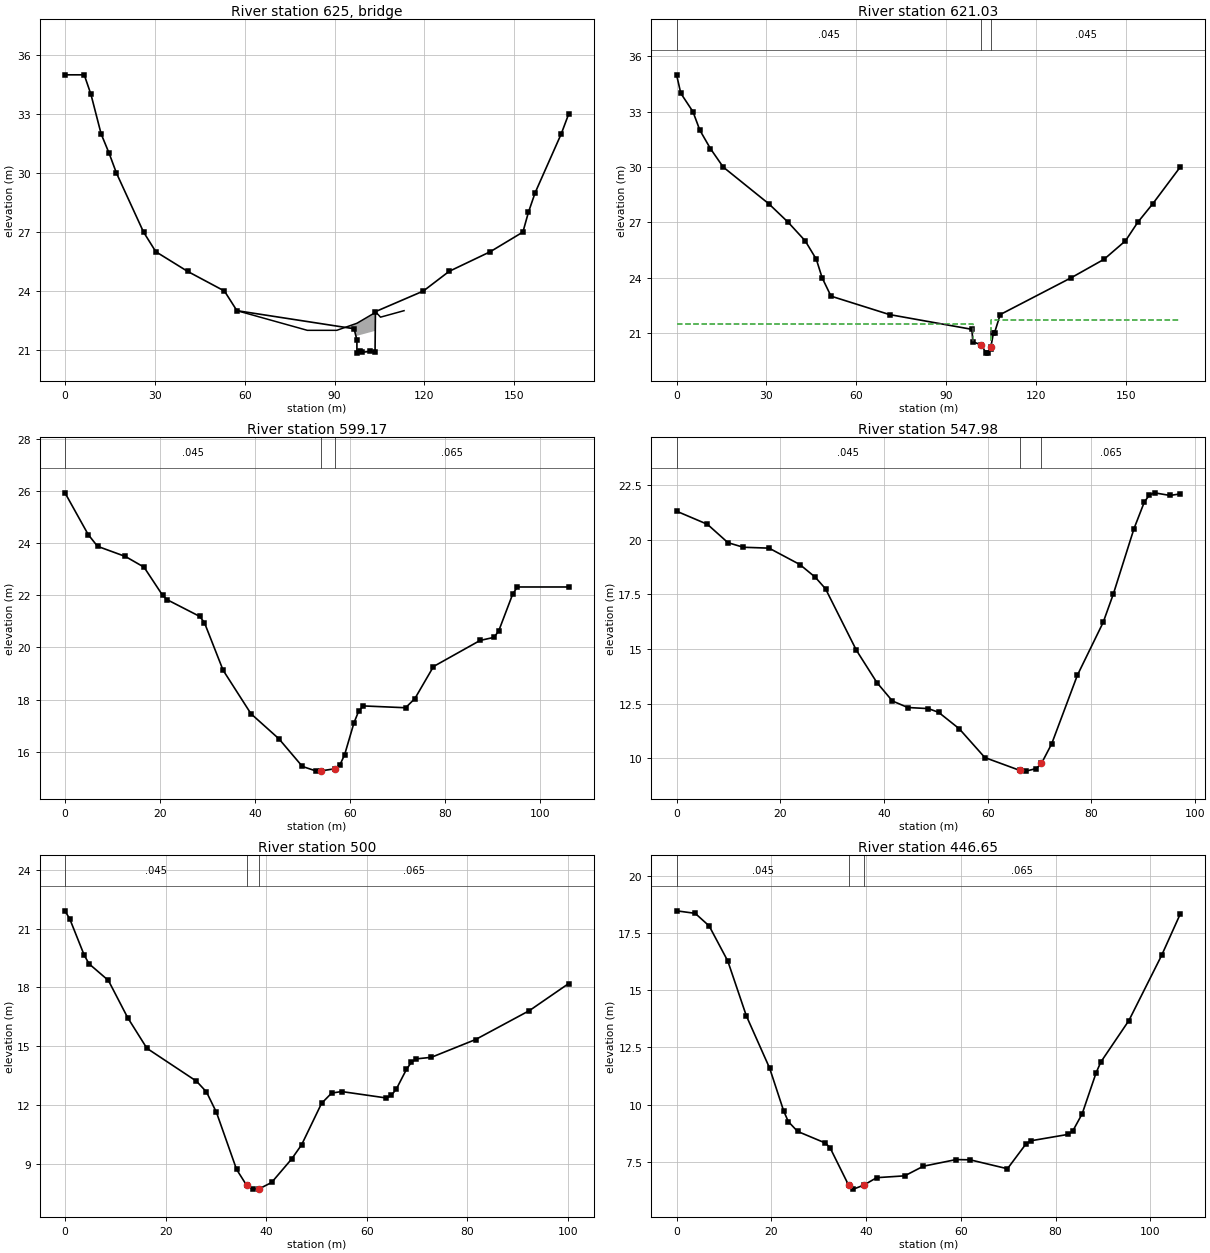
Type RM Length L Ch R = 3 ,625     ,,,
BEGIN DESCRIPTION:
Petrie's Street (1102)
END DESCRIPTION:
Bridge Culvert--1,0,-1,-1, 0
Deck Dist Width WeirC Skew NumUp NumDn MinLoCord MaxHiCord MaxSubmerge Is_Ogee
6.47,10.6,1.67,0, 8, 8, 22.36, , 0.98, 0, 0,0,,
   57.42   80.93   90.75   97.48  103.53  103.66  105.36  113.21
      23      22      22   22.36    22.9   22.95   22.67      23
                           21.72   21.97
   51.56   90.75   95.79   98.93  104.94  105.01  113.21   131.8
      23   22.22   21.87   21.82   22.07   22.07      23      24
                           21.19    21.4
BR Coef=-1 , 0 , 0 ,, 0 ,,,0.8,-1,,0,
WSPro=,,,, 1 ,,,, 0 ,,,, 0 ,,,,-1 ,-1 ,-1 , 0 , 0 , 0 , 0 , 0
BC Design=,, 0 ,, 0 ,,,,,,
BC Use User HTab Curves=0
BC User HTab FreeFlow(D)= 0

Type RM Length L Ch R = 1 ,621.03  ,63.06,44.67,36.85
XS GIS Cut Line= 4
340161.8344726565424677.12811279340224.0656738285424678.33331299
340277.1311035165424677.61010742340325.854919434 5424657.1217041
#Sta/Elev= 29
       0      35    1.41      34    5.47      33    7.77      32    11.3      31
   15.57      30   30.85      28   37.29      27   42.94      26   46.66      25
   48.59      24   51.56      23   71.11      22    98.6    21.2   98.93   20.53
  101.78   20.35  103.37   19.91  103.83   19.91  104.94   20.11  104.96   20.26
   105.8      21  106.16   21.01  108.06      22   131.8      24  142.75      25
  149.89      26  153.97      27  158.96      28  168.17      30
#Mann= 3 , 0 , 0
       0    .045       0  101.78    .035       0  104.96    .045       0
#XS Ineff= 2 , 0
       0   98.93    21.5  104.94       0    21.7
Permanent Ineff=
       F       F
Bank Sta=101.78,104.96
XS Rating Curve= 0 ,0
Exp/Cntr=0.5,0.3

Type RM Length L Ch R = 1 ,599.17  ,42.47,51.19,56.77
XS GIS Cut Line= 4
340317.2623291025424702.84130859340274.1273193365424711.74090576
340253.8461303715424730.52868652340221.7706909185424718.29608154
#Sta/Elev= 30
       0   25.93    4.89   24.33    6.85   23.88   12.72   23.49   16.64   23.08
   20.55      22   21.53   21.83   28.38   21.19   29.36   20.95   33.28   19.13
   39.15   17.46   45.03    16.5   49.97   15.44   52.93   15.26   53.92   15.27
   56.77   15.35   57.87    15.5   58.85   15.88   60.83   17.11   61.82   17.56
    62.8   17.76   71.69   17.69   73.65   18.04   77.57   19.27   87.38   20.27
   90.33   20.39   91.31   20.64   94.25   22.05   95.23   22.32  106.02   22.32
#Mann= 3 , 0 , 0
       0    .045       0   53.92    .035       0   56.77    .065       0
Bank Sta=53.92,56.77
XS Rating Curve= 0 ,0
Exp/Cntr=0.3,0.1

Type RM Length L Ch R = 1 ,547.98  ,42.14,47.99,52.35
XS GIS Cut Line= 3
340227.9702758795424736.13427734340266.0335083015424752.95751953
340321.0383300785424760.54431152
#Sta/Elev= 30
       0    21.3    5.95    20.7    9.91   19.86   12.88   19.65   17.84   19.61
   23.78   18.86   26.75   18.28   28.73   17.75   34.68   14.94   38.64   13.46
   41.62   12.62   44.59   12.32   48.56   12.27   50.54    12.1   54.51   11.35
   59.46   10.03   66.24    9.44    67.4    9.41   69.38    9.53   70.37    9.76
   72.35   10.66   77.31    13.8   82.27   16.21   84.25   17.52   88.22    20.5
    90.2   21.71   91.19   22.04   92.18   22.14   95.16   22.02   97.14   22.09
#Mann= 3 , 0 , 0
       0    .045       0   66.24    .035       0   70.37    .065       0
Bank Sta=66.24,70.37
XS Rating Curve= 0 ,0
Exp/Cntr=0.3,0.1

Type RM Length L Ch R = 1 ,500     ,60.5,53.35,49.24
XS GIS Cut Line= 5
340226.2656860355424766.46551514340243.7484741215424774.32269287
340261.7570800785424795.61627197340288.4268798835424803.34887695
340312.2490844735424794.80908203
#Sta/Elev= 30
       0   21.92     .96    21.5    3.83   19.65    4.79   19.21    8.63   18.36
   12.46   16.46   16.29   14.89   26.14   13.21   28.13   12.66   30.12   11.61
   34.11     8.7    36.1    7.89   37.37    7.69   38.64    7.71   41.08    8.03
   45.06    9.23   47.05    9.96   51.02   12.08   53.01    12.6   54.99   12.68
   63.91   12.35   64.91   12.49    65.9   12.82   67.88   13.81   68.87   14.18
   69.86   14.35   72.84   14.43   81.64   15.34   92.34   16.82  100.13    18.2
#Mann= 3 , 0 , 0
       0    .045       0    36.1    .035       0   38.64    .065       0
Bank Sta=36.1,38.64
XS Rating Curve= 0 ,0
Exp/Cntr=0.3,0.1

Type RM Length L Ch R = 1 ,446.65  ,40.57,46.68,45.89
XS GIS Cut Line= 3
340202.8817138675424846.96569824340246.3759155275424834.67572021
340307.1436767585424841.38751221
#Sta/Elev= 30
       0   18.46    3.93   18.35    6.88    17.8   10.81   16.27   14.74   13.87
   19.65   11.59    22.6    9.73   23.58    9.26   25.55    8.83   31.44    8.32
   32.42    8.11   36.35    6.47   37.34    6.31   39.47    6.48   42.25    6.81
   48.16    6.89    52.1    7.31      59     7.6   61.96    7.59   69.85     7.2
   73.79    8.29   74.78    8.42   82.67     8.7   83.65    8.85   85.63     9.6
   88.59    11.4   89.57   11.86   95.49   13.67  102.39   16.51  106.33   18.32
#Mann= 3 , 0 , 0
       0    .045       0   36.35    .035       0   39.47    .065       0
Bank Sta=36.35,39.47
XS Rating Curve= 0 ,0
Exp/Cntr=0.3,0.1