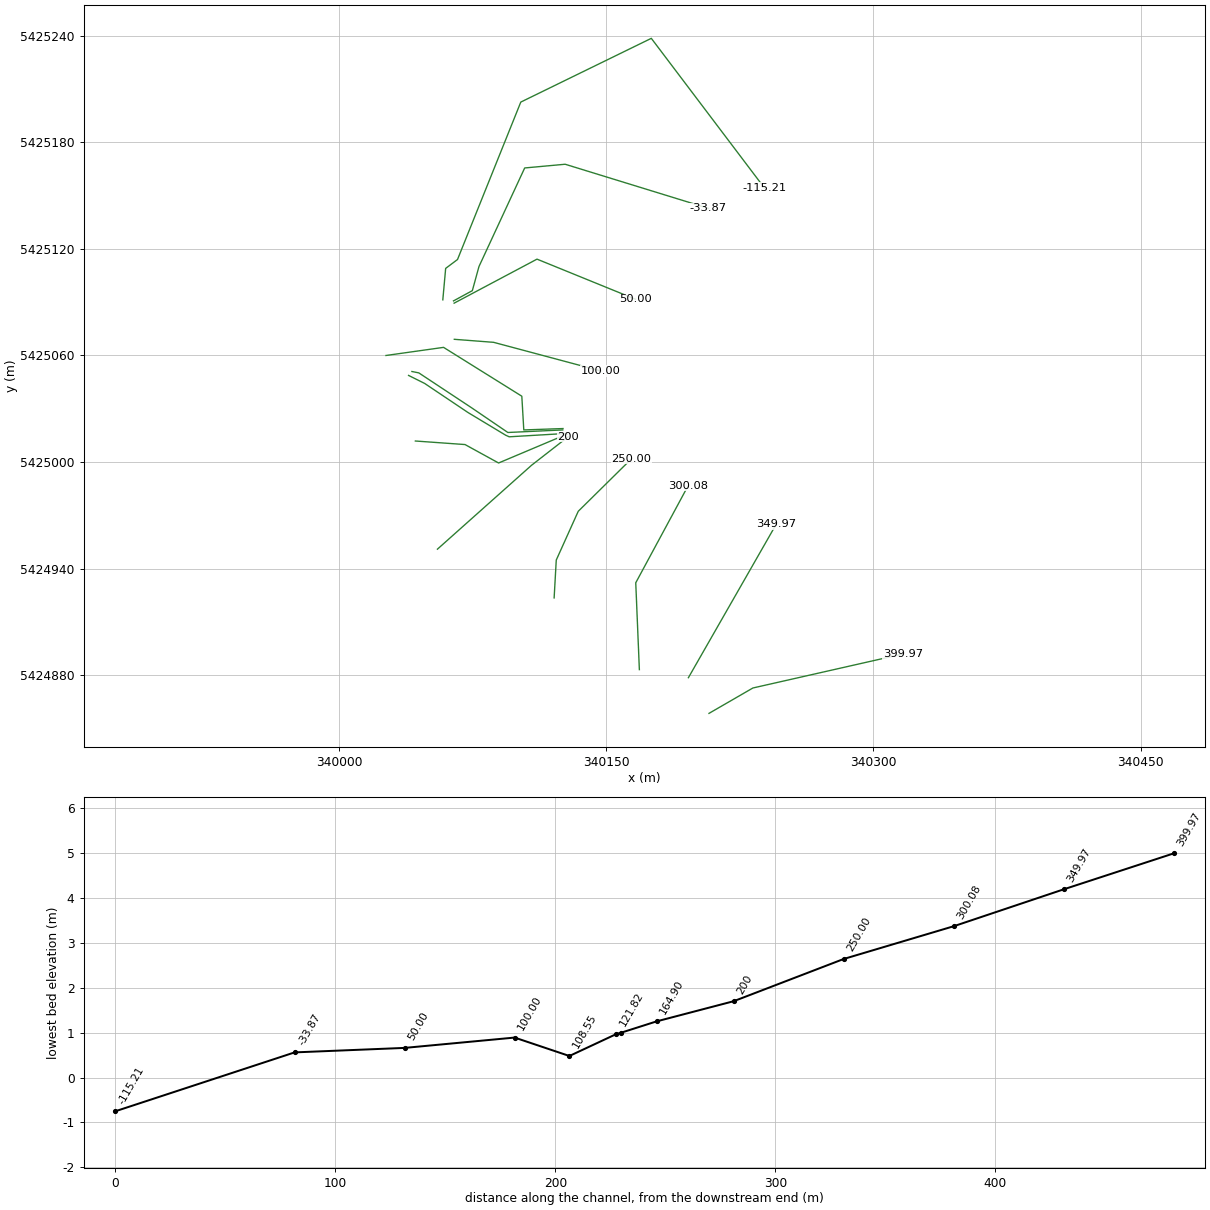
HEC-RAS study PetriesBrk_v001.prj: Petries_Brook

--- PetriesBrk_v001.g02 (geometry) --- (continued)

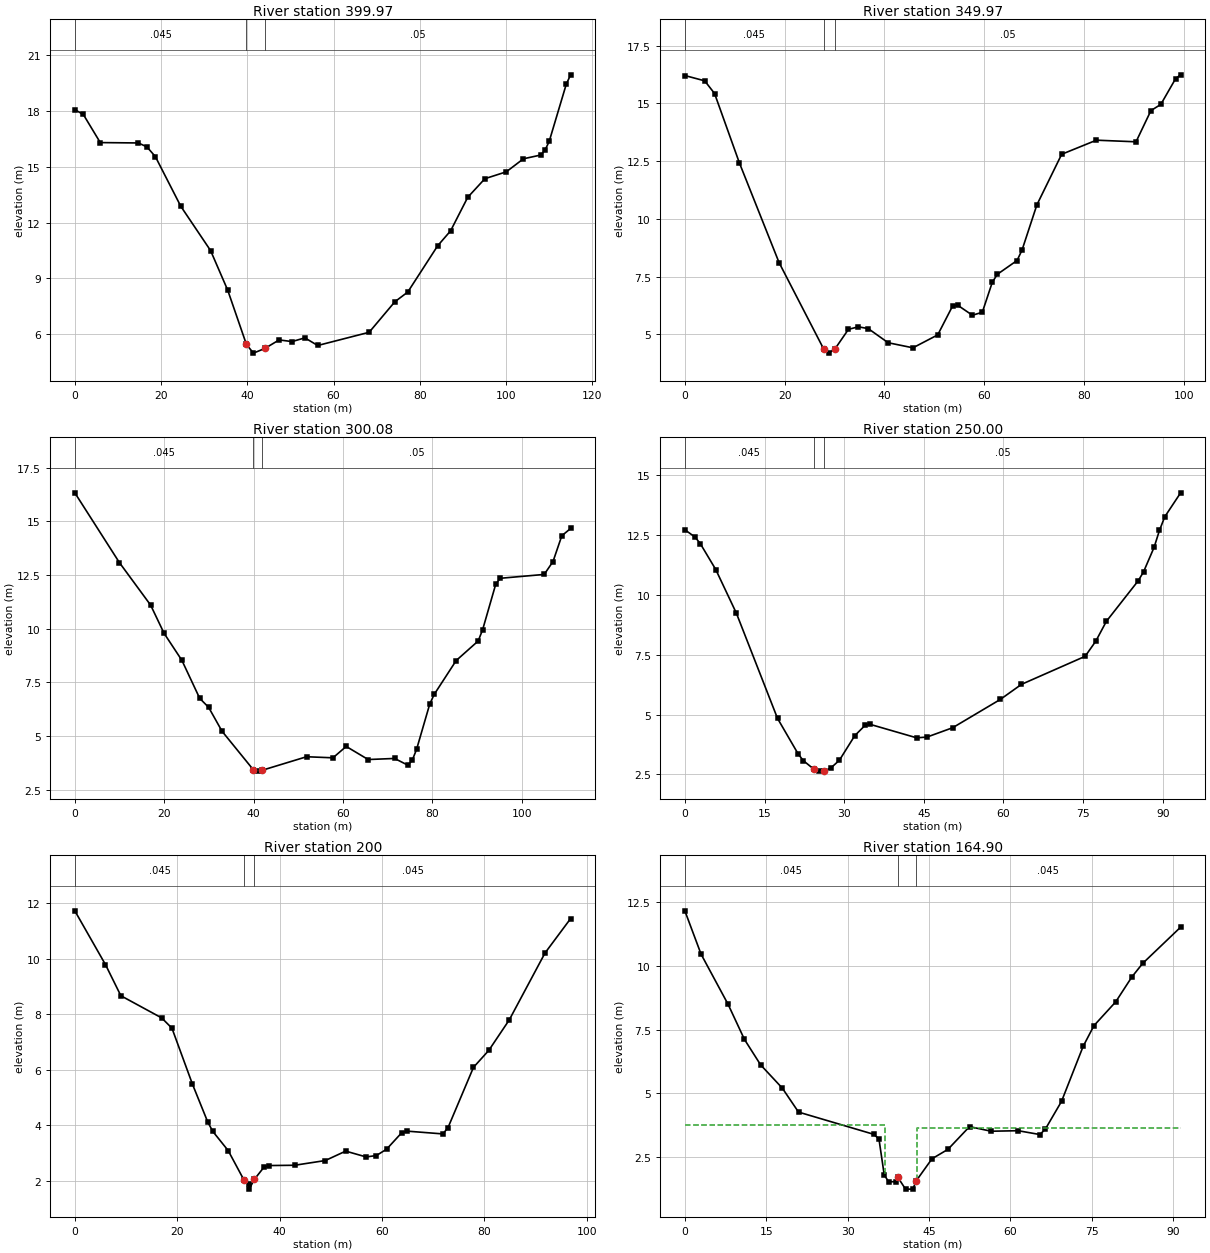
Type RM Length L Ch R = 1 ,399.97  ,43.09,50,61.08
XS GIS Cut Line= 3
340207.7009277345424858.61791992 340232.363281255424872.90429688
340316.6909179695424892.06091309
#Sta/Elev= 30
       0   18.07    1.97   17.81     5.9    16.3   14.74   16.28   16.71   16.07
   18.67   15.55   24.57   12.88   31.48    10.5   35.46    8.37   39.79    5.46
   41.42    4.99   44.06    5.24   47.39     5.7   50.37    5.61   53.35    5.81
   56.33     5.4   68.26    6.11   74.22    7.75   77.21    8.27   84.16   10.76
   87.15   11.56   91.12   13.36    95.1   14.36  100.07   14.73  104.04   15.43
  108.02   15.63  109.01   15.88  110.01   16.36  113.98   19.44  114.98   19.94
#Mann= 3 , 0 , 0
       0    .045       0   39.79    .035       0   44.06     .05       0
Bank Sta=39.79,44.06
XS Rating Curve= 0 ,0
Exp/Cntr=0.3,0.1

Type RM Length L Ch R = 1 ,349.97  ,46.29,49.89,52.66
XS GIS Cut Line= 2
340196.1428833015424878.69488525340245.4359130865424965.01690674
#Sta/Elev= 30
       0   16.21    3.98   15.98    5.96   15.43   10.93   12.43   18.89    8.11
   27.83    4.37   28.83    4.19   30.09    4.37    32.8    5.22   34.79    5.33
   36.78    5.25   40.76    4.64   45.73    4.42    50.7    4.98   53.68    6.23
   54.67    6.27   57.65    5.83   59.64    5.96   61.63    7.25   62.63     7.6
    66.6     8.2    67.6    8.65   70.58   10.61   75.55    12.8   82.51   13.41
   90.46   13.34   93.44   14.69   95.43   14.96   98.41   16.08    99.4   16.24
#Mann= 3 , 0 , 0
       0    .045       0   27.83    .035       0   30.09     .05       0
Bank Sta=27.83,30.09
XS Rating Curve= 0 ,0
Exp/Cntr=0.3,0.1

Type RM Length L Ch R = 1 ,300.08  ,52.99,50.08,47.27
XS GIS Cut Line= 3
340168.6113281255424883.23352051340166.5836791995424932.10668945
340196.0034790045424986.74291992
#Sta/Elev= 30
       0   16.33    9.98   13.08   16.97    11.1   19.97    9.79   23.96    8.53
   27.95    6.76   29.95    6.34   32.94    5.23   39.93    3.44   40.93    3.37
   41.93    3.41   51.87    4.04   57.78    3.99   60.74    4.52   65.66    3.91
   71.57    3.96   74.52    3.65   75.51    3.87   76.49    4.38   79.45     6.5
   80.43    6.94   85.36    8.52   90.28    9.43   91.27    9.95   94.22   12.08
   95.21   12.35  105.06   12.53  107.03   13.13     109   14.33  110.97   14.67
#Mann= 3 , 0 , 0
       0    .045       0   39.93    .035       0   41.93     .05       0
Bank Sta=39.93,41.93
XS Rating Curve= 0 ,0
Exp/Cntr=0.3,0.1

Type RM Length L Ch R = 1 ,250.00  ,53.02,50,43.41
XS GIS Cut Line= 4
340120.7506713875424923.58831787 340121.947082525424944.88812256
340134.2816772465424972.31207275340164.1124877935425001.82128906
#Sta/Elev= 30
       0   12.71    1.94    12.4    2.91   12.13    5.82   11.05     9.7    9.23
   17.45    4.84   21.33    3.36    22.3    3.08   24.24    2.73   25.24    2.64
   26.24    2.65   27.48    2.77   29.09    3.09      32    4.12   33.94    4.55
   34.91    4.59   43.64    4.03   45.58    4.06   50.43    4.45    59.4    5.63
   63.39    6.26   75.38    7.43   77.38    8.06   79.38    8.89   85.37   10.58
   86.37   10.95   88.37   11.98   89.37   12.68   90.37   13.25   93.36   14.25
#Mann= 3 , 0 , 0
       0    .045       0   24.24    .035       0   26.24     .05       0
Bank Sta=24.24,26.24
XS Rating Curve= 0 ,0
Exp/Cntr=0.3,0.1

Type RM Length L Ch R = 1 ,200     ,41.59,35.1,14.44
XS GIS Cut Line= 3
340055.2227172855424951.01568604340108.0842895515424998.23651123
340128.5507202155425014.19708252
#Sta/Elev= 30
       0   11.73    5.99    9.79    8.99    8.67   16.97    7.87   18.97     7.5
   22.96    5.49   25.96    4.12   26.95    3.78   29.95    3.09   33.06    2.02
   33.94     1.9   34.06     1.7   35.06    2.05   36.94    2.49   37.94    2.55
   42.93    2.56   48.92    2.73   52.91    3.07    56.9    2.86    58.9    2.91
    60.9    3.14   63.89    3.74   64.89    3.79   71.88    3.69   72.88    3.91
   77.87    6.09   80.86     6.7   84.86     7.8   91.84   10.21   96.84   11.45
#Mann= 3 , 0 , 0
       0    .045       0   33.06    .035       0   35.06    .045       0
Bank Sta=33.06,35.06
XS Rating Curve= 0 ,0
Exp/Cntr=0.3,0.1

Type RM Length L Ch R = 1 ,164.90  ,16.7,16,13.4
XS GIS Cut Line= 4
340042.8353271485425011.87188721340070.7041015635425009.88110352
340089.5620727545424999.50390625340128.1572875985425015.82373047
#Sta/Elev= 30
       0   12.16    2.99   10.46    7.98    8.49   10.98    7.12   13.97    6.12
   17.96    5.21   20.95    4.27   34.79     3.4   35.77    3.22   36.75     1.8
   37.57    1.54   38.92    1.54    39.2    1.73   40.67    1.25   42.02    1.25
   42.62    1.57   45.55    2.44   48.49    2.81   52.46     3.7   56.45    3.52
   61.44    3.54   65.43    3.39   66.43     3.6   69.42    4.69   73.41    6.85
    75.4    7.66    79.4    8.59   82.39    9.57   84.38    10.1   91.37   11.52
#Mann= 3 , 0 , 0
       0    .045       0    39.2    .035       0   42.62    .045       0
#XS Ineff= 2 , 0
       0    36.9    3.75    42.7       0    3.65
Permanent Ineff=
       F       F
Bank Sta=39.2,42.62
XS Rating Curve= 0 ,0
Exp/Cntr=0.5,0.3

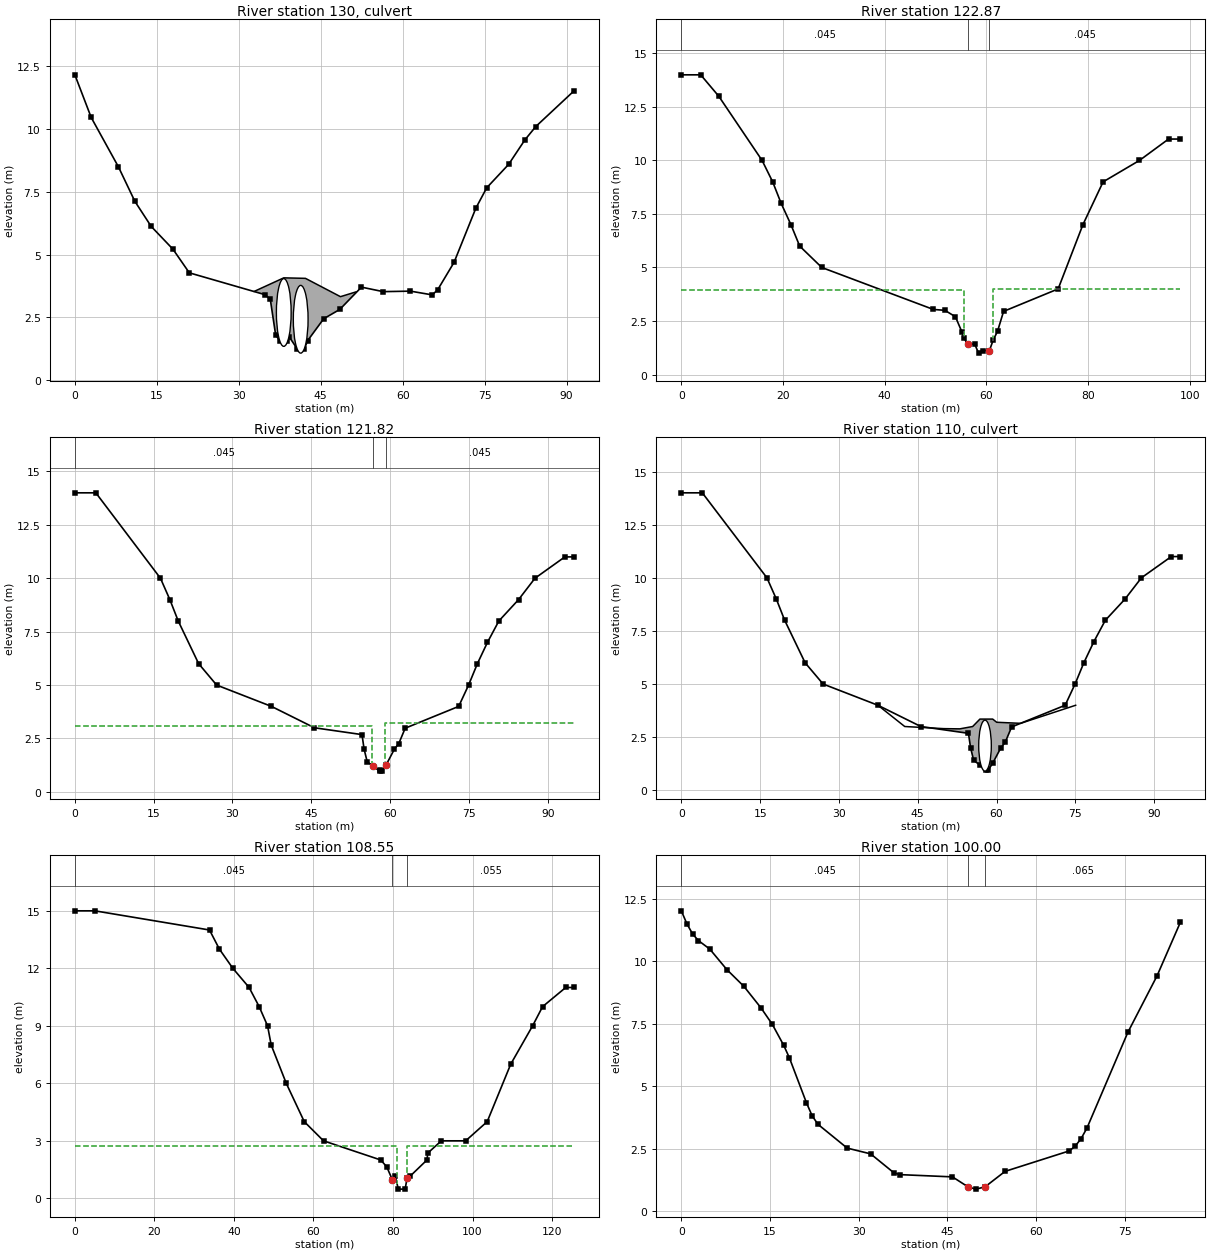
Type RM Length L Ch R = 2 ,130     ,,,
BEGIN DESCRIPTION:
Bartlett's Avenue(1101-1)
END DESCRIPTION:
Bridge Culvert--1,0,-1,-1, 0
Deck Dist Width WeirC Skew NumUp NumDn MinLoCord MaxHiCord MaxSubmerge Is_Ogee
4.3,9,1.57,0, 5, 11, 3.62, , 0.98, 0, 1,1,,
   32.83   38.24   42.21   48.62   51.46
    3.53    4.07    4.05    3.32    3.51
                                        
   21.62   23.63   29.41    34.5   37.15   38.55   39.57    42.4   45.81   63.75
   74.09
       4    3.86    3.62    3.66    4.12       4       4    3.93    3.95       4
       4
                                                                                
        
BR Coef=-1 , 0 , 0 ,, 0 ,,,0.8,-1,,0,
WSPro=,,,, 1 ,,,, 0 ,,,, 0 ,,,,-1 ,-1 ,-1 , 0 , 0 , 0 , 0 , 0
Culvert=1,2.7,,11.6,0.032,0.9,1,2,3,1.34,38.24,1.24,57,Culvert #1  , 0 ,2.4
Culvert Bottom n=0.035
Culvert Bottom Depth=0.2
Culvert Depth Blocked=0.2
Culvert=1,2.7,,11.6,0.032,0.9,1,2,3,1.07,41.34,0.94,59.9,Culvert #2  , 0 ,2.4
Culvert Bottom n=0.035
Culvert Bottom Depth=0.17
Culvert Depth Blocked=0.17
BC Design=,, 0 ,, 0 ,,,,,,
BC Use User HTab Curves=0
BC User HTab FreeFlow(D)= 0

Type RM Length L Ch R = 1 ,122.87  ,3.2,2.2,2.7
XS GIS Cut Line= 6
      340039.015     5425048.775      340048.069     5425044.251
      340072.358     5425027.922      340093.557     5425015.123
      340095.544     5425014.241      340127.303     5425016.112
#Sta/Elev= 28
       0      14    3.81      14    7.36      13   15.88      10   17.96       9
   19.62       8   21.55       7   23.27       6   27.62       5   49.56    3.04
   51.81       3   53.89     2.7   55.15       2   55.55    1.71   56.32    1.42
   57.68    1.42   58.45       1   59.23    1.12   60.58    1.12    61.3     1.6
   62.17    2.02   63.36    2.95   74.09       4   78.96       7   82.93       9
   90.07      10    95.8      11   98.14      11
#Mann= 3 , 0 , 0
       0    .045       0   56.32    .035       0   60.58    .045       0
#XS Ineff= 2 , 0
       0   55.65    3.95   61.25       0       4
Permanent Ineff=
       F       F
Bank Sta=56.32,60.58
XS Rating Curve= 0 ,0
Exp/Cntr=0.5,0.3

Type RM Length L Ch R = 1 ,121.82  ,20.4,21.4,13
XS GIS Cut Line= 6
      340040.892     5425050.981      340044.756     5425050.209
      340074.235      5425030.68      340094.771     5425016.668
      340094.771     5425016.668      340125.575     5425018.102
#Sta/Elev= 29
       0      14    3.99      14   16.29      10   18.08       9   19.67       8
   23.56       6   26.98       5   37.42       4   45.59       3   54.65    2.68
   55.05       2   55.64    1.41   56.79    1.19   58.03     .97    58.1    1.02
   58.46     .97   59.26    1.27   60.82       2   61.65    2.26   62.87    2.98
   73.05       4   74.94       5   76.61       6   78.53       7    80.7       8
   84.45       9   87.57      10   93.26      11      95      11
#Mann= 3 , 0 , 0
       0    .045       0   56.79    .035       0   59.26    .045       0
#XS Ineff= 2 , 0
       0    56.6     3.1      59       0     3.2
Permanent Ineff=
       F       F
Bank Sta=56.79,59.26
XS Rating Curve= 0 ,0
Exp/Cntr=0.5,0.3

Type RM Length L Ch R = 2 ,110     ,,,
BEGIN DESCRIPTION:
Bartlett's Avenue (1101)
END DESCRIPTION:
Bridge Culvert--1,0,-1,-1, 0
Deck Dist Width WeirC Skew NumUp NumDn MinLoCord MaxHiCord MaxSubmerge Is_Ogee
5.7,7.6,1.67,0, 10, 10, 2.89, , 0.98, 0, 1,1,,
   37.42   42.52   49.94      53   55.45   56.83   59.26   60.02   64.58   75.05
       4       3     2.9    2.89       3    3.35    3.35     3.2    3.15       4
                                                                                
   62.53   70.12   72.28   74.03   74.82    77.1    79.1   81.07   87.02   92.16
       3    2.64    2.88       3    3.02    3.06     3.2    3.12    3.15       3
                                                                                
BR Coef=-1 , 0 , 0 ,, 0 ,,,0.8,-1,,0,
WSPro=,,,, 1 ,,,, 0 ,,,, 0 ,,,,-1 ,-1 ,-1 , 0 , 0 , 0 , 0 , 0
Culvert=1,2.4,,15.4,0.032,0.9,1,1,1,0.9,57.8,0.13,82.2,Culvert #1  , 0 ,2.2
Culvert Bottom n=0.035
Culvert Bottom Depth=0.35
BC Design=,, 0 ,, 0 ,,,,,,
BC Use User HTab Curves=0
BC User HTab FreeFlow(D)= 0

Type RM Length L Ch R = 1 ,108.55  ,21.3,24.9,35.5
XS GIS Cut Line= 5
       340026.34     5425059.998      340058.661      5425064.56
       340102.61      5425037.08      340103.714     5425018.102
      340125.735     5425018.884
#Sta/Elev= 30
       0      15    5.02      15   33.86      14   36.35      13   39.73      12
   43.82      11   46.35      10   48.46       9   49.37       8   53.16       6
   57.69       4   62.53       3   76.93       2   78.44    1.64   79.84     .97
   80.56    1.14   81.35     .48   83.05     .48   83.56    1.07   84.28    1.15
   88.54       2   88.75    2.36   92.16       3   98.28       3  103.69       4
  109.61       7  115.11       9  117.62      10  123.44      11  125.52      11
#Mann= 3 , 0 , 0
       0    .045       0   79.84    .035       0   83.56    .055       0
#XS Ineff= 2 , 0
       0      81    2.75    83.4       0    2.75
Permanent Ineff=
       F       F
Bank Sta=79.84,83.56
XS Rating Curve= 0 ,0
Exp/Cntr=0.5,0.3

Type RM Length L Ch R = 1 ,100.00  ,51.01,50,48.15
XS GIS Cut Line= 3
340064.700927734 5425069.0994873340086.762878418 5425067.3994751
340146.9454956055425051.29589844
#Sta/Elev= 30
       0   12.02     .96   11.49    1.92   11.09    2.89   10.83    4.81   10.49
     7.7    9.67   10.58       9   13.47    8.14   15.39    7.48   17.32    6.64
   18.28    6.14   21.17    4.34   22.13    3.82   23.12    3.48   28.06    2.53
   32.02     2.3   35.97    1.54   36.96    1.47   45.86    1.38    48.5     .98
   49.82     .89   51.37     .98   54.76     1.6   65.64    2.42   66.63    2.61
   67.62    2.91   68.61    3.33   75.53    7.16   80.47    9.42   84.43   11.57
#Mann= 3 , 0 , 0
       0    .045       0    48.5    .035       0   51.37    .065       0
Bank Sta=48.5,51.37
XS Rating Curve= 0 ,0
Exp/Cntr=0.3,0.1

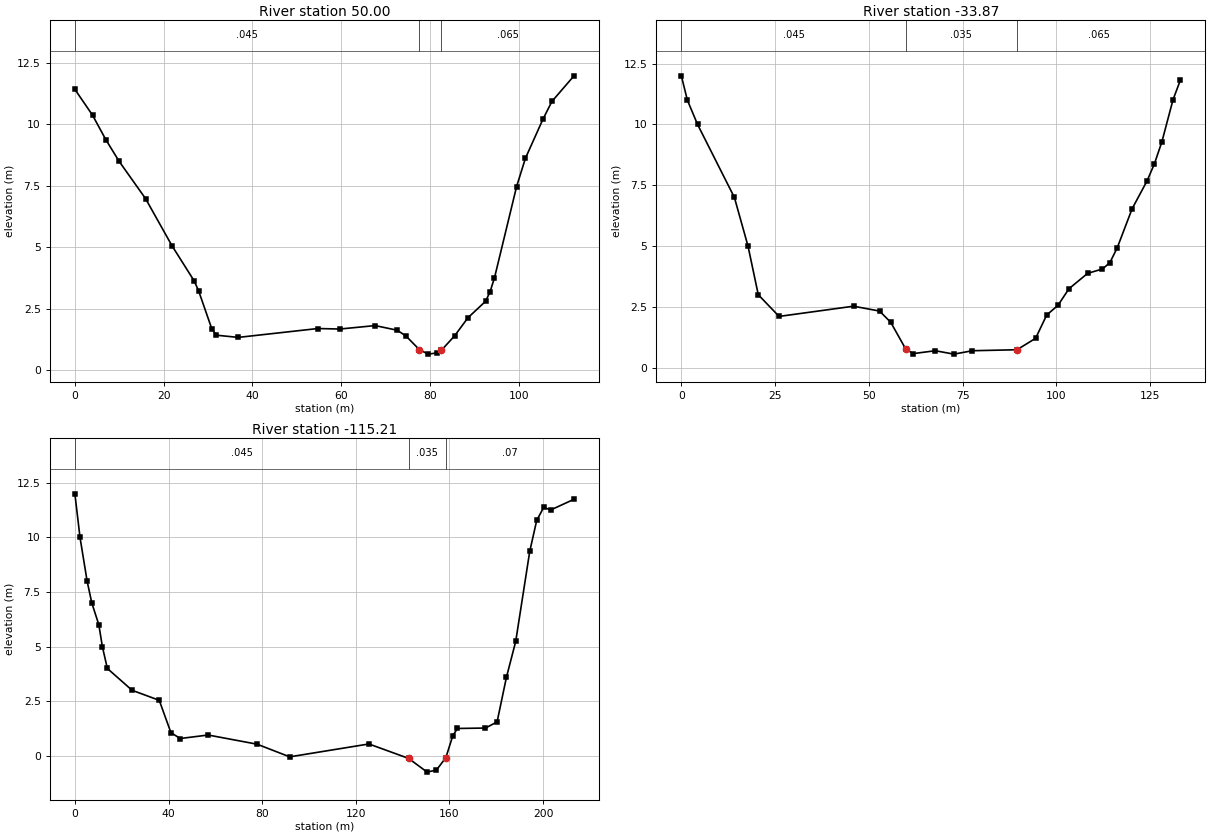
Type RM Length L Ch R = 1 ,50.00   ,42.7,50,62.04
XS GIS Cut Line= 3
 340064.588073735425089.43432617340111.1361083985425114.20391846
340166.4172973635425091.65087891
#Sta/Elev= 30
       0   11.42    3.98   10.37    6.96    9.38    9.95     8.5   15.92    6.98
   21.89    5.06   26.86    3.64   27.86    3.24   30.84    1.69   31.84    1.43
   36.81    1.34   54.72     1.7   59.69    1.68   67.65    1.82   72.63    1.63
   74.62    1.39   77.61     .84    79.6     .66   81.61     .71   82.58     .82
   85.57    1.41   88.55    2.14   92.53    2.81   93.53     3.2   94.52    3.76
    99.5    7.47  101.49    8.62  105.47   10.22  107.46   10.93  112.43   11.97
#Mann= 3 , 0 , 0
       0    .045       0   77.61    .035       0   82.58    .065       0
Bank Sta=77.61,82.58
XS Rating Curve= 0 ,0
Exp/Cntr=0.3,0.1

Type RM Length L Ch R = 1 ,-33.87  ,47.21,81.46,53.88
XS GIS Cut Line= 6
      340064.244     5425090.711      340074.824     5425096.472
      340078.531        5425110.      340104.217     5425165.507
       340126.95     5425167.599      340207.414     5425142.789
#Sta/Elev= 30
       0      12    1.61      11    4.33      10   14.15       7   17.78       5
   20.52       3   26.07    2.11   45.92    2.53   52.86    2.33   55.83    1.87
    59.8     .78   61.78     .58   67.72      .7   72.67     .56   77.63      .7
   89.51     .74   94.47    1.21   97.44    2.17  100.41    2.56  103.38    3.25
  108.34    3.88   112.3    4.06  114.28    4.32  116.26    4.94  120.22    6.54
  124.19    7.68  126.17    8.39  128.15    9.29  131.12   11.02   133.1   11.83
#Mann= 3 , 0 , 0
       0    .045       0    59.8    .035       0   89.51    .065       0
Bank Sta=59.8,89.51
XS Rating Curve= 0 ,0
Exp/Cntr=0.3,0.1

Type RM Length L Ch R = 1 ,-115.21 ,0,0,0
XS GIS Cut Line= 6
      340058.242     5425091.305      340059.846     5425109.004
        340066.5        5425114.       340102.03     5425202.577
      340175.315     5425238.447      340238.857     5425154.222
#Sta/Elev= 30
       0      12     2.2      10    5.23       8    7.23       7   10.24       6
   11.74       5   13.87       4   24.43       3   36.04    2.54   41.02    1.06
      45     .79   56.94     .95   77.83     .53   91.76    -.05   125.6     .54
  142.52    -.12  150.48    -.75  154.46    -.65  158.44    -.09  161.43     .92
  163.42    1.25  175.37    1.27  180.34    1.55  184.32    3.59   188.3    5.24
  194.28    9.36  197.26   10.78  200.25   11.38  203.23   11.26  213.19   11.75
#Mann= 3 , 0 , 0
       0    .045       0  142.52    .035       0  158.44     .07       0
Bank Sta=142.52,158.44
XS Rating Curve= 0 ,0
Exp/Cntr=0.3,0.1